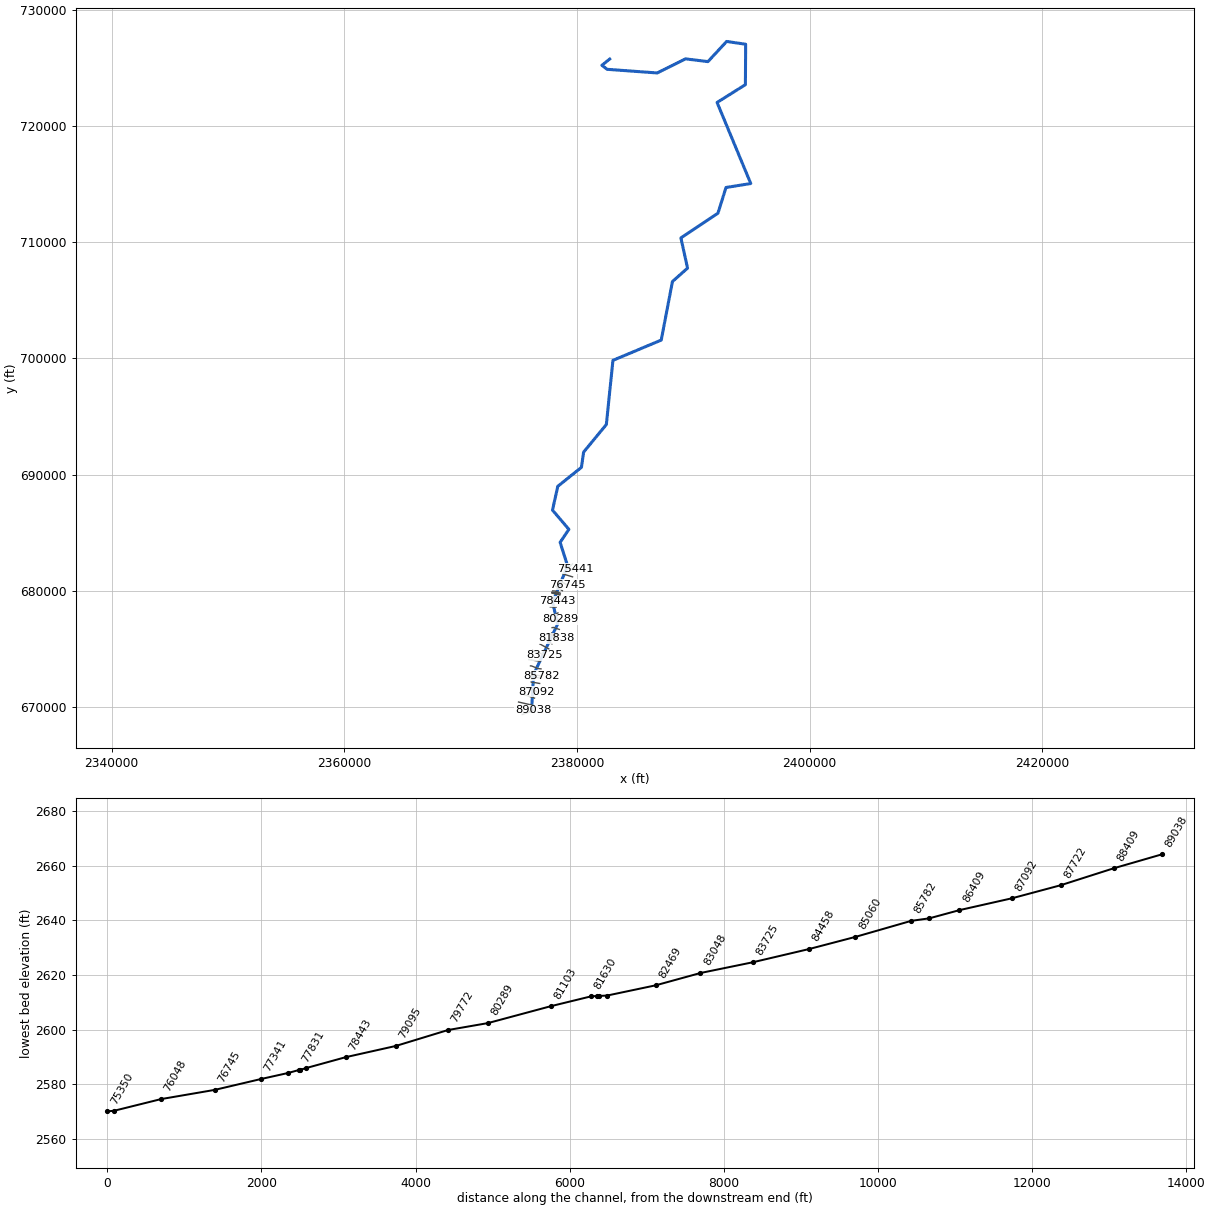
--- DRKFK_2.prj (project) ---

Proj Title=DRKFK_2
Current Plan=p01
Default Exp/Contr=0,0
English Units
Geom File=g01
Flow File=f01
Plan File=p01
BEGIN DESCRIPTION:
----------MODEL BY WOOD PLC 2022----------
AFH study
Randolph County, WV
HEC-RAS Version: RAS 6.2
Vertical Datum: NAVD88
Projection: NAD 1983 StatePlane West Virginia S FIPS 4702 (US Feet)
Terrain: 1-meter LIDAR (FEMA Region III 3DEP collected 2016-2018)
Land Use: 2019 NLCD
Hydrologic Method:
WV SIR2010-5033 regression equations
Additional Model Notes:
None
END DESCRIPTION:
DSS File=dss
DSS Export Rating Curves= 0
DSS Export Rating Curve Sorted= 0
DSS Export Volume Flow Curves= 0
DXF OffsetX= 0
DXF OffsetY= 0
DXF ScaleX= 0
DXF ScaleY= 0

--- DRKFK_2.p01 (plan) ---

Plan Title=Floodplain
Program Version=6.20
Short Identifier=Floodplain
Geom File=g01
Flow File=f01
Subcritical Flow
K Sum by GR= 0
Std Step Tol= 0.01
Critical Tol= 0.01
Num of Std Step Trials= 20
Max Error Tol= 0.3
Flow Tol Ratio= 0.001
Split Flow NTrial= 30
Split Flow Tol= 0.02
Split Flow Ratio= 0.02
Log Output Level= 0
Friction Slope Method= 1
Unsteady Friction Slope Method= 2
Unsteady Bridges Friction Slope Method= 1
Parabolic Critical Depth
Global Vel Dist= 0 , 0 , 0
Global Log Level= 0
CheckData=True
Encroach Param=-1 ,0,0, 0
Computation Interval=0.1SEC
Output Interval=1SEC
Instantaneous Interval=Max Profile
Mapping Interval=1HOUR
Computation Time Step Use Courant=        0
Computation Time Step Use Time Series=    0
Computation Time Step Count To Double=0
Computation Time Step Max Doubling=0
Computation Time Step Max Halving=0
Computation Time Step Residence Courant=0
Run HTab= 0
Run UNet= 0
Run Sediment= 0
Run PostProcess= 0
Run WQNet= 0
Run RASMapper=-1
UNET Theta= 0
UNET Theta Warmup= 0
UNET ZTol= 0
UNET ZSATol= 0
UNET MxIter= 0
UNET Max Iter WO Improvement= 0
UNET MaxInSteps= 0
UNET DtIC= 0
UNET DtMin= 0
UNET MaxCRTS= 0
UNET WFStab= 0
UNET SFStab= 0
UNET WFX= 1
UNET SFX= 1
UNET Gravity=32.174
UNET 1D Methodology=Finite Difference
UNET DSS MLevel= 1
UNET Pardiso=0
UNET DZMax Abort= 0
UNET Use Existing IB Tables= 0
UNET Froude Reduction=False
UNET Froude Limit= 0
UNET Froude Power= 0
UNET D1 Cores= 0
UNET WindReference=Eulerian
UNET WindDragFormulation=Hsu (1988)
UNET D2 Coriolis=0
UNET D2 Cores= 0
UNET D2 Theta= 1
UNET D2 Theta Warmup= 1
UNET D2 Z Tol= 0.01
UNET D2 Volume Tol= 0.01
UNET D2 Max Iterations= 20
UNET D2 Equation= 0
UNET D2 RampUpFraction=0.1
UNET D2 TimeSlices= 1
UNET D2 Turbulence Formulation=Non-Conservative (original)
UNET D2 Eddy Viscosity=0.3
UNET D2 Transverse Eddy Viscosity=0.1
UNET D2 Smagorinsky Mixing=0
UNET D2 BCVolumeCheck=0
UNET D2 Cores=0
UNET D2 SolverType=PARDISO (Direct)
UNET D2 Minimum Iterations= 2147483647
UNET D2 Maximum Iterations= 2147483647
UNET D2 Restart Number= 10
UNET D2 Relaxation Coeff=1.3
UNET D2 SOR Precondition Iterations= 10
UNET D2 ILUT Maximum Fill= 8
UNET D2 ILUT Tolerance=1E-08
UNET D1D2 MaxIter= 0
UNET D1D2 ZTol=0.01
UNET D1D2 QTol=0.1
UNET D1D2 MinQTol=1
DSS File=dss
Write IC File= 0
Write IC File at Fixed DateTime=0
Write IC File at Sim End=0
Echo Input=False
Echo Parameters=False
Echo Output=False
Write Detailed= 0
HDF Write Warmup=0
HDF Write Time Slices=0
HDF Flush=0
HDF Compression= 1
HDF Chunk Size= 1
HDF Spatial Parts= 1
HDF Use Max Rows=0
HDF Fixed Rows= 1
Calibration Method= 0
Calibration Iterations= 20
Calibration Max Change=0.05
Calibration Tolerance=0.2
Calibration Maximum=1.5
Calibration Minimum=0.5
Calibration Optimization Method= 1
WQ AD Non Conservative
WQ ULTIMATE=-1
WQ Max Comp Step=1HOUR
WQ Output Interval=15MIN
WQ Output Selected Increments= 0
WQ Output face flow=0
WQ Output face velocity=0
WQ Output face area=0
WQ Output face dispersion=0
WQ Output cell volume=0
WQ Output cell surface area=0
WQ Output cell continuity=0
WQ Output cumulative cell continuity=0
WQ Output face conc=0
WQ Output face dconc_dx=0
WQ Output face courant=0
WQ Output face peclet=0
WQ Output face adv mass=0
WQ Output face disp mass=0
WQ Output cell mass=0
WQ Output cell source sink temp=0
WQ Output nsm pathways=0
WQ Output nsm derived pathways=0
WQ Create Restart=0
WQ Fixed Restart=0
WQ System Summary=0
WQ Write To DSS=0
Sorting and Armoring Iterations= 10
XS Update Threshold= 0.02
Bed Roughness Predictor= 0
Hydraulics Update Threshold= 0.02
Energy Slope Method= 1
Volume Change Method= 1
Sediment Retention Method= 0
Sediment TS Multiplier= 1
Warm Up Method= 0
XS Weighting Method= 0
Number of US Weighted Cross Sections= 1
Number of DS Weighted Cross Sections= 1
Upstream XS Weight=0
Main XS Weight=1
Downstream XS Weight=0
Number of DS XS's Weighted with US Boundary= 1
Upstream Boundary Weight= 1
Weight of XSs Associated with US Boundary= 0
Number of US XS's Weighted with DS Boundary= 1
Downstream Boundary Weight= 0.5
Weight of XSs Associated with DS Boundary= 0.5
Percentile Method= 0
Sediment Output Level= 3
Mass or Volume Output= 0
Output Increment Type= 1
Profile and TS Output Increment= 1
Transport Output Increment 1
XS Output Flag= 0
XS Output Increment= 10
Read HDF5 Sediment Hotstart= 0
Sediment Hotstart Type= 0
Write Gradation File= 0
Read Gradation Hotstart= 0
Write HDF5 File= 1
Write Binary Output= 1
Write DSS Sediment File= 0
DSS Sediment Output Type= 1
SV Curve= 0
Specific Gage Flag= 0
Subcell Erosion Methods= 0
Subcell Deposition Methods= 0
Advection Scheme= 1
Matrix Solver= 0
Implicit Weighting Factor= 1
Maximum Outer Loop Convergence Iterations= 5
Convergence Maximum Absolute= 0.001
Convergence RMSE= 0.0001
Grain Fractions Max Abs Error= 0.001
Max Subgrid Regions= 1
Max Subgrid Length Scale= 3.402823E+38
Initial Layer Thickness= 3.402823E+38
Min Layer Thickness= 3.402823E+38
Max Layer Thickness= 3.402823E+38
Number of Layers= 5

--- DRKFK_2.f01 (steady flow) ---

Flow Title=Flow
Program Version=6.20
Number of Profiles= 1
Profile Names=P100yr
River Rch & RM=DRKFK_2,Main,89038
    8270
River Rch & RM=DRKFK_2,Main,67168
    9190
River Rch & RM=DRKFK_2,Main,48104
   11000
River Rch & RM=DRKFK_2,Main,21909
   32300
River Rch & RM=DRKFK_2,Main,1249
   40500
Boundary for River Rch & Prof#=DRKFK_2,Main            , 1
Up Type= 0
Dn Type= 3
Dn Slope=0.00489
DSS Import GetInterval= 0
DSS Import GetPeak= 0
DSS Import FillOption= 0

--- DRKFK_2.g01 (geometry) ---

Geom Title=Geometry
Program Version=6.20

River Reach=DRKFK_2         ,Main
Reach XY= 30
     2376104.902      669631.791     2376277.594       672796.32
     2378346.952      677142.457     2377915.615      679017.675
     2379205.293      682137.614     2378561.738      684170.771
     2379314.267      685287.163     2377904.829      686941.682
     2378362.123      688989.803     2380393.094      690619.708
      2380579.93      691929.429     2382534.553      694303.456
     2383102.342      699824.322     2387254.004      701568.653
     2388217.088      706604.995     2389515.613      707756.828
     2388943.974      710357.548     2392129.208      712483.423
     2392823.481      714696.134     2394951.048      715035.549
2392053.81685711722009.3387620842394488.42171445723540.911380807
     2394511.778       727019.51     2392874.444      727258.248
     2391270.174      725523.569     2389344.557      725761.238
     2386909.064      724548.744     2382604.689      724861.493
     2382154.117      725207.953     2382825.519      725746.331

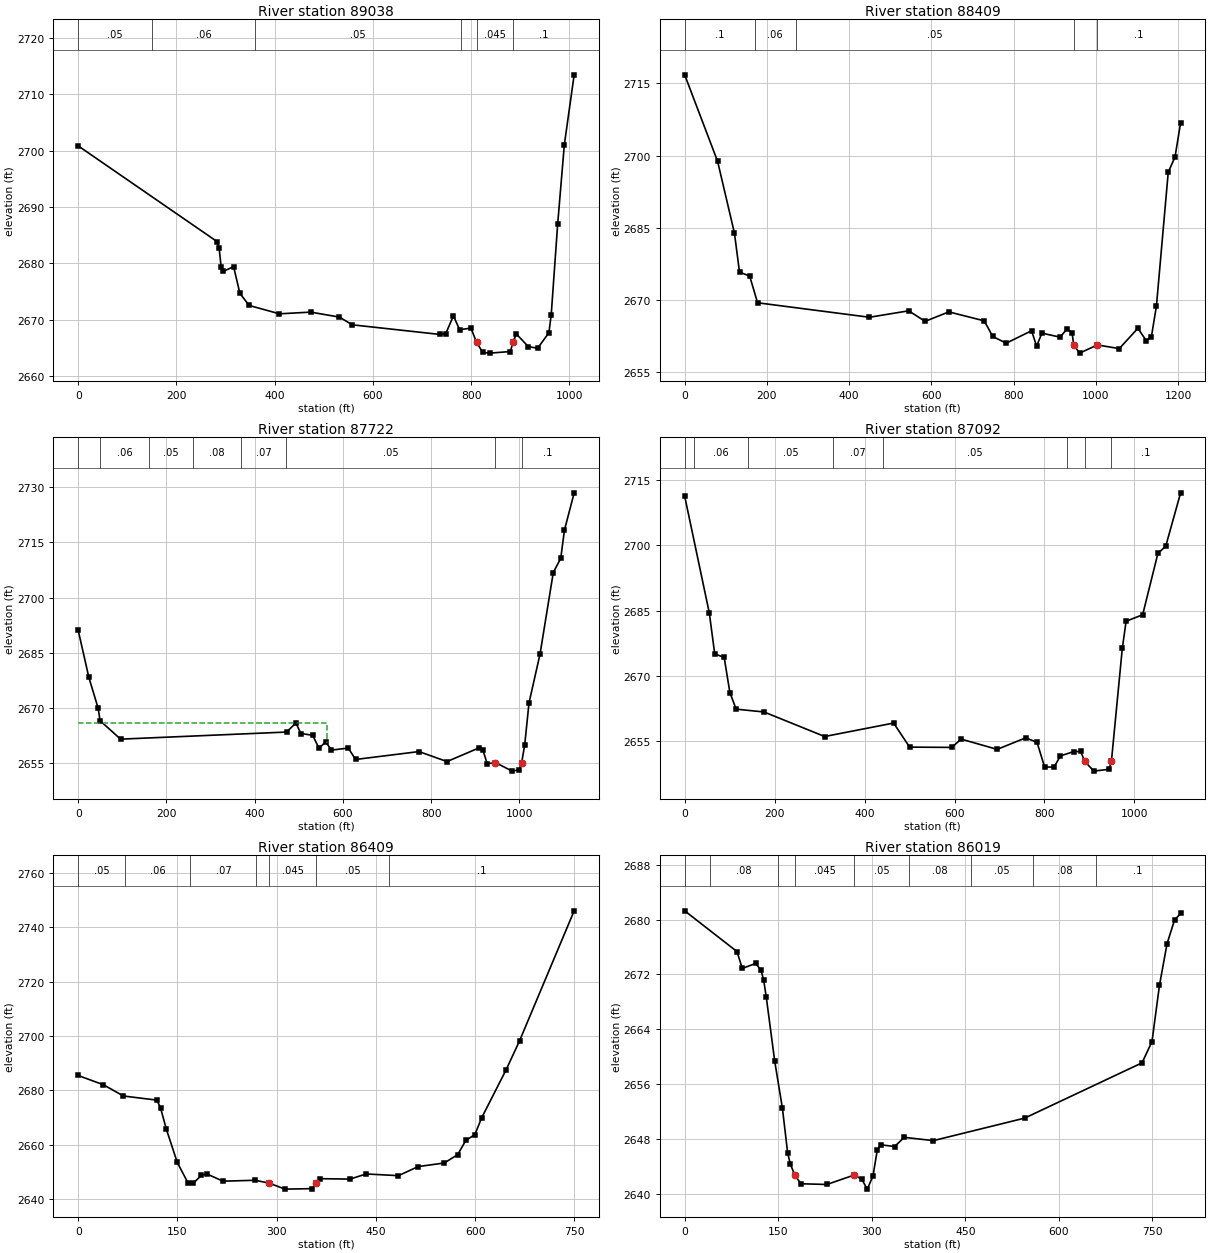
Type RM Length L Ch R = 1 ,89038   ,628.6,628.6,628.6
XS GIS Cut Line= 3
2375305.56187368669354.0030577182376208.27295452669670.525066078
2376240.35122262669712.972548781
#Sta/Elev= 30
       0 2700.83   282.5 2683.88   286.8 2682.81     291 2679.38   295.2 2678.57
   316.4 2679.43   329.2 2674.68   348.1 2672.54   409.7 2671.06   473.3 2671.36
   531.8 2670.48     558 2669.11   735.8 2667.41   748.3 2667.55     764 2670.69
   776.6 2668.25   799.7 2668.52   811.1 2665.99   823.7 2664.22   837.8 2664.09
     880 2664.37   885.1    2666   892.1 2667.49   916.3 2665.26   935.3 2664.95
   958.4  2667.7   963.1  2670.9   976.3 2687.04   989.8 2701.03  1009.8 2713.43
#Mann= 6 ,-1,0
       0     .05       0     150     .06       0     360     .05       0
     780      .1       0   811.1    .045       0   885.1      .1       0
Bank Sta=811.1,885.1
XS Rating Curve= 0 ,0
Exp/Cntr=0.3,0.1

Type RM Length L Ch R = 1 ,88409   ,687.6,687.6,687.6
XS GIS Cut Line= 2
2374986.19892302670431.5147420282376161.50098076 670162.35043507
#Sta/Elev= 30
       0 2716.78      80 2698.82     121 2683.89   133.3 2675.79     158 2674.98
   177.2 2669.43   449.3 2666.42   544.5 2667.76   584.6 2665.57   642.2 2667.54
   728.4 2665.67   748.9 2662.43   781.7 2661.03   843.3 2663.62   855.6 2660.42
   868.4 2663.12     913 2662.28   929.4 2664.02   941.7 2663.24  945.73 2660.71
   960.1 2658.97  1003.3 2660.67  1056.6 2659.91  1101.8 2664.13  1122.3 2661.55
  1134.6 2662.34  1146.9 2668.75  1175.6 2696.54  1192.1 2699.73  1205.7 2706.83
#Mann= 5 ,-1,0
       0      .1       0     170     .06       0     270     .05       0
  945.73    .045       0  1003.3      .1       0
Bank Sta=945.73,1003.3
XS Rating Curve= 0 ,0
Exp/Cntr=0.3,0.1

Type RM Length L Ch R = 1 ,87722   ,629.7,629.7,629.7
XS GIS Cut Line= 2
2375297.33738517671130.9176352342376360.99161326670767.746250719
#Sta/Elev= 30
       0 2691.07    24.1  2678.3    45.3 2669.83    49.5  2666.5      96 2661.48
   472.2 2663.41   493.3 2665.88   504.6 2663.01   531.3 2662.54   545.6 2659.01
   560.9 2660.74   573.9  2658.5     612 2659.05   628.6 2655.95   772.3  2658.1
   835.7 2655.38   909.1 2659.14   917.4 2658.43   926.8  2654.8   945.6  2655.1
   983.5 2652.78   999.3 2653.16 1005.02 2655.12  1011.9    2660  1021.6 2671.35
  1046.6 2684.64  1076.6 2706.81  1093.5 2710.67  1101.9 2718.33  1123.9 2728.49
#Mann= 8 ,-1,0
       0      .1       0      50     .06       0     160     .05       0
     260     .08       0     370     .07       0     470     .05       0
   945.6    .045       0 1005.02      .1       0
#XS Ineff= 2 , 0
          563.18 2665.89
Permanent Ineff=
       F       F
Bank Sta=945.6,1005.02
XS Rating Curve= 0 ,0
Exp/Cntr=0.3,0.1

Type RM Length L Ch R = 1 ,87092   ,683.1,683.1,683.1
XS GIS Cut Line= 3
2375524.84035077671710.4914737112376460.16878981671399.008000312
2376551.70512935671326.110992676
#Sta/Elev= 30
       0 2711.33    54.8 2684.43    66.8 2675.01    87.8 2674.23   100.5 2666.13
   114.4  2662.3   176.4 2661.65   311.3    2656   464.6  2659.1   500.2 2653.56
   593.8 2653.49   614.8  2655.4   694.9 2653.04   758.2 2655.69   783.5 2654.67
   800.3 2648.99   821.4 2648.95   835.5 2651.54     865 2652.52   880.4 2652.55
  889.74 2650.26   909.9 2648.03   943.7 2648.46  948.89 2650.26   973.2 2676.39
   981.6 2682.54  1018.4 2684.04  1052.3 2698.17  1069.7 2699.82  1102.8 2712.11
#Mann= 8 ,-1,0
       0      .1       0      20     .06       0     140     .05       0
     330     .07       0     440     .05       0     850      .1       0
  889.74    .045       0  948.89      .1       0
Bank Sta=889.74,948.89
XS Rating Curve= 0 ,0
Exp/Cntr=0.3,0.1

Type RM Length L Ch R = 1 ,86409   ,390.2,390.2,390.2
XS GIS Cut Line= 5
2376072.78973728672157.6051873022376202.17470369672105.463275627
2376340.95392215 672079.831325662376418.04181148672098.438747222
2376801.28532649672027.400771662
#Sta/Elev= 30
       0 2685.48    38.2 2682.06    68.3 2677.94   118.9 2676.42   124.4  2673.6
     133 2665.93   149.7 2653.53   165.9    2646   174.1 2645.87   186.1 2648.76
   194.4  2649.3   218.8 2646.61   267.6 2646.95   288.6  2645.9   312.7 2643.69
   353.9 2643.87   359.1 2645.86   366.2 2647.53   410.9 2647.38   435.3 2649.27
   484.1 2648.64   513.8 2651.98   553.3  2653.3   573.6 2656.36   585.9  2661.6
   599.6 2663.74   609.9 2669.92   646.9  2687.6   667.2 2698.26   749.7 2746.04
#Mann= 7 ,-1,0
       0     .05       0      70     .06       0   169.5     .07       0
   269.5     .05       0   288.6    .045       0   359.1     .05       0
  469.92      .1       0
Bank Sta=288.6,359.1
XS Rating Curve= 0 ,0
Exp/Cntr=0.3,0.1

Type RM Length L Ch R = 1 ,86019   ,236.7,236.7,236.7
XS GIS Cut Line= 3
 2376097.7283403672393.4992891412376480.50958387 672538.37135702
2376865.94903052672515.776630837
#Sta/Elev= 30
       0 2681.27    83.9 2675.33    92.4 2672.87   113.8  2673.6   122.4 2672.62
   126.6 2671.22   130.9 2668.67   144.4 2659.35   156.8 2652.47   165.1 2646.01
   169.4 2644.36   176.6 2642.75   186.5 2641.48   228.1 2641.38   272.1 2642.76
     284 2642.14   292.9  2640.7     302 2642.61   308.8 2646.35   314.8 2647.16
   336.7 2646.91   352.2 2648.25   398.8 2647.77   545.2 2651.05   733.5 2659.11
   749.5 2662.21   761.5 2670.43   773.7  2676.5   785.6 2679.92   795.4 2680.89
#Mann= 9 ,-1,0
       0     .05       0      40     .08       0     150     .05       0
   176.6    .045       0   272.1     .05       0     360     .08       0
  459.28     .05       0  559.28     .08       0  659.28      .1       0
Bank Sta=176.6,272.1
XS Rating Curve= 0 ,0
Exp/Cntr(USF)=0,0
Exp/Cntr=0.3,0.1

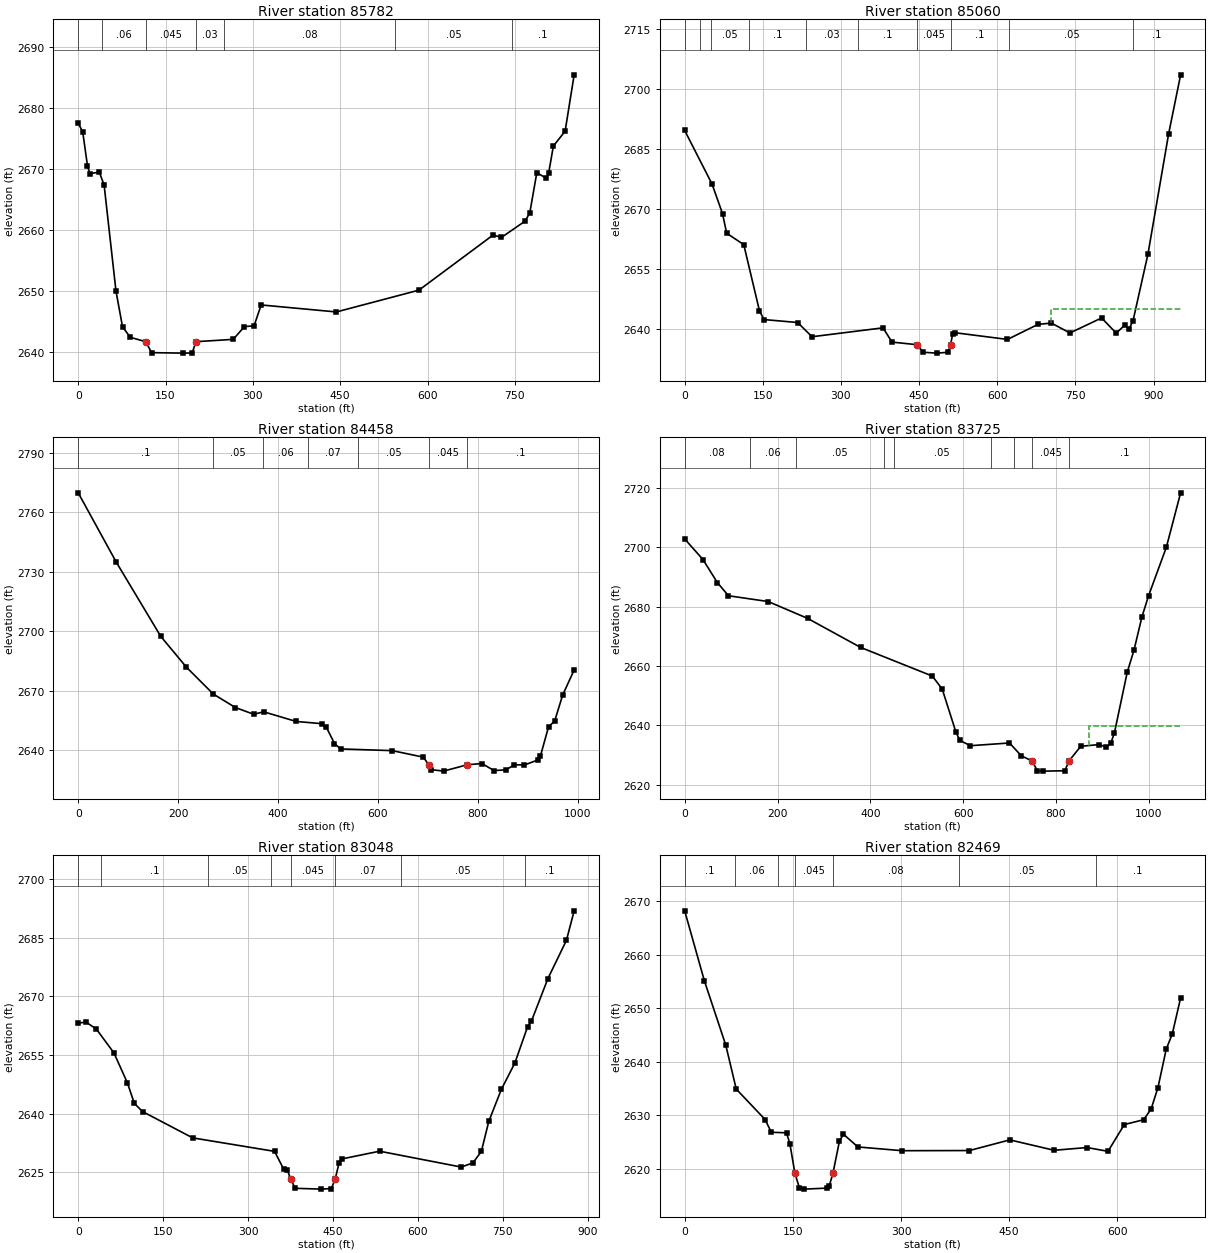
Type RM Length L Ch R = 1 ,85782   ,722.6,722.6,722.6
XS GIS Cut Line= 4
2376092.63106392672666.5855286992376427.55143818672736.762336651
2376509.46136152672744.4656723112376931.41270805672677.020644126
#Sta/Elev= 30
       0  2677.5     7.7 2676.11    15.9 2670.52      20 2669.24    36.3 2669.46
    44.5 2667.35    64.9 2649.93    76.1 2644.08    89.4 2642.36  115.78 2641.64
   126.2 2639.84   179.4 2639.76   195.7 2639.78   202.3 2641.64   266.2 2642.02
   285.6 2644.13     302 2644.22   314.2 2647.67   443.4 2646.52   585.2  2650.1
   712.6 2659.15     727 2658.76   767.5 2661.43   775.6 2662.79   787.7 2669.39
   803.9 2668.47     808  2669.3   816.1 2673.76   836.3  2676.2   851.8 2685.45
#Mann= 7 ,-1,0
       0     .05       0      40     .06       0  115.78    .045       0
   202.3     .03       0     250     .08       0  544.46     .05       0
  744.46      .1       0
Bank Sta=115.78,202.3
XS Rating Curve= 0 ,0
Exp/Cntr=0.3,0.1

Type RM Length L Ch R = 1 ,85060   ,601.9,601.9,601.9
XS GIS Cut Line= 4
2376011.81989508673539.6328060662376114.73035518673531.326831487
 2376669.7526755673308.4057423212376919.02300947673283.190208495
#Sta/Elev= 30
       0 2689.64    52.5 2676.23    72.6 2668.83    80.6 2663.91   113.4 2661.07
   143.6 2644.47   152.2 2642.31   216.9 2641.57   244.4 2638.01   380.7 2640.24
   397.9 2636.67   445.3 2636.03   458.3 2634.12   483.8 2633.91   505.7 2634.12
  510.32 2636.02   514.3 2638.63   518.6 2639.02   619.6 2637.34   678.1  2641.1
   703.8 2641.43   739.4 2638.96   800.3 2642.71   828.4  2638.9   844.5 2640.92
   852.6 2639.84   860.6 2642.04   889.1 2658.62   928.9  2688.8   951.9 2703.56
#Mann= 10 ,-1,0
       0      .1       0      30     .06       0      50     .05       0
  123.25      .1       0  233.25     .03       0  333.25      .1       0
   445.3    .045       0  510.32      .1       0  623.25     .05       0
  861.36      .1       0
#XS Ineff= 2 , 0
                           702.4            2645
Permanent Ineff=
       F       F
Bank Sta=445.3,510.32
XS Rating Curve= 0 ,0
Exp/Cntr=0.3,0.1

Type RM Length L Ch R = 1 ,84458   ,732.7,732.7,732.7
XS GIS Cut Line= 2
2375872.64889586674077.278460396 2376854.9094377673935.690078807
#Sta/Elev= 30
       0 2769.84    76.3 2734.81   165.2 2697.43   216.5  2681.9   270.3 2668.35
   314.7 2661.52   351.1 2658.16   371.3 2659.38     436 2654.53   488.5 2653.38
   496.6 2651.58   512.8  2643.4   524.9 2640.67   628.4  2639.8   690.6 2636.53
  701.42 2632.67   706.8 2630.21     731 2629.47   778.5 2632.68   807.8 2633.31
     832 2629.75   856.3 2630.11   872.5  2632.7   892.7 2632.54   920.9 2635.21
     925 2637.14   941.2 2651.88   953.3 2654.65   969.4 2667.84   992.4 2680.48
#Mann= 7 ,-1,0
       0      .1       0     270     .05       0     370     .06       0
     460     .07       0     560     .05       0  701.42    .045       0
   778.5      .1       0
Bank Sta=701.42,778.5
XS Rating Curve= 0 ,0
Exp/Cntr=0.3,0.1

Type RM Length L Ch R = 1 ,83725   ,677.1,677.1,677.1
XS GIS Cut Line= 3
2376203.65149856 674863.094839152377080.67613192 674539.78211621
2377190.58326442674463.672388523
#Sta/Elev= 30
       0 2702.77    39.3 2695.84    70.4 2688.08    94.3 2683.64     180 2681.69
   264.9 2676.02   378.8 2666.27   533.5 2656.61   554.8 2652.24   584.6 2637.62
   593.1 2634.93   615.5 2633.18   699.7 2634.09   725.3 2629.78  748.87 2627.99
   759.4 2624.78   772.2 2624.62   819.1 2624.74   827.6 2627.98   853.2 2632.97
   892.7 2633.56   908.6 2632.68   917.7 2633.94   925.7 2637.43   953.5 2657.99
   967.9  2665.3   985.1 2676.57   999.5 2683.71  1037.7 2699.99  1068.4 2718.28
#Mann= 9 ,-1,0
       0     .08       0     140     .06       0     240     .05       0
     430     .06       0     450     .05       0     660     .06       0
     710     .08       0  748.87    .045       0   827.6      .1       0
#XS Ineff= 2 , 0
                          870.76         2639.67
Permanent Ineff=
       F       F
Bank Sta=748.87,827.6
XS Rating Curve= 0 ,0
Exp/Cntr=0.3,0.1

Type RM Length L Ch R = 1 ,83048   ,579.3,579.3,579.3
XS GIS Cut Line= 2
2376819.98200761675423.4832945552377588.45141804675002.934136586
#Sta/Elev= 30
       0 2663.17    13.9 2663.43    32.1 2661.64    63.1 2655.55    86.9 2647.88
    99.1 2642.64   113.8 2640.53   202.2 2633.82   346.8 2630.37   363.1 2625.77
   369.6 2625.54  375.022623.375   383.2 2620.92   429.7 2620.71   447.1 2620.86
  454.072623.375   460.8 2627.44   465.3 2628.42   532.3 2630.41   676.7 2626.35
   697.3 2627.44   712.1 2630.36   725.2 2638.04   747.4 2646.21   771.4 2653.01
   793.6 2662.17   800.5 2663.66   829.7 2674.58   862.4 2684.36     876 2691.89
#Mann= 8 ,-1,0
       0     .08       0      40      .1       0     230     .05       0
     340     .08       0  375.02    .045       0  454.07     .07       0
     570     .05       0     790      .1       0
Bank Sta=375.02,454.07
XS Rating Curve= 0 ,0
Exp/Cntr=0.3,0.1

Type RM Length L Ch R = 1 ,82469   ,630.3,630.3,630.3
XS GIS Cut Line= 2
 2377306.1670845675839.046248608 2377861.4994803 675433.49378345
#Sta/Elev= 30
       0 2668.15    27.3  2655.1      57 2643.08    71.5 2634.89   111.5 2629.21
   120.1 2626.83   141.2 2626.73   145.9 2624.69  152.86 2619.16   159.2 2616.41
   165.9 2616.22   197.4 2616.41   200.6 2616.89   205.6 2619.18   214.6 2625.18
   220.2 2626.46   240.2 2624.09   301.6 2623.39   394.9 2623.42   450.8 2625.41
   512.3 2623.47   558.1 2623.98     587 2623.27   609.6 2628.27   636.5 2629.17
   646.9  2631.2   656.3 2635.18   667.8 2642.37   676.1 2645.15   687.7 2651.91
#Mann= 7 ,-1,0
       0      .1       0      70     .06       0     130     .08       0
  152.86    .045       0   205.6     .08       0     380     .05       0
     570      .1       0
Bank Sta=152.86,205.6
XS Rating Curve= 0 ,0
Exp/Cntr=0.3,0.1

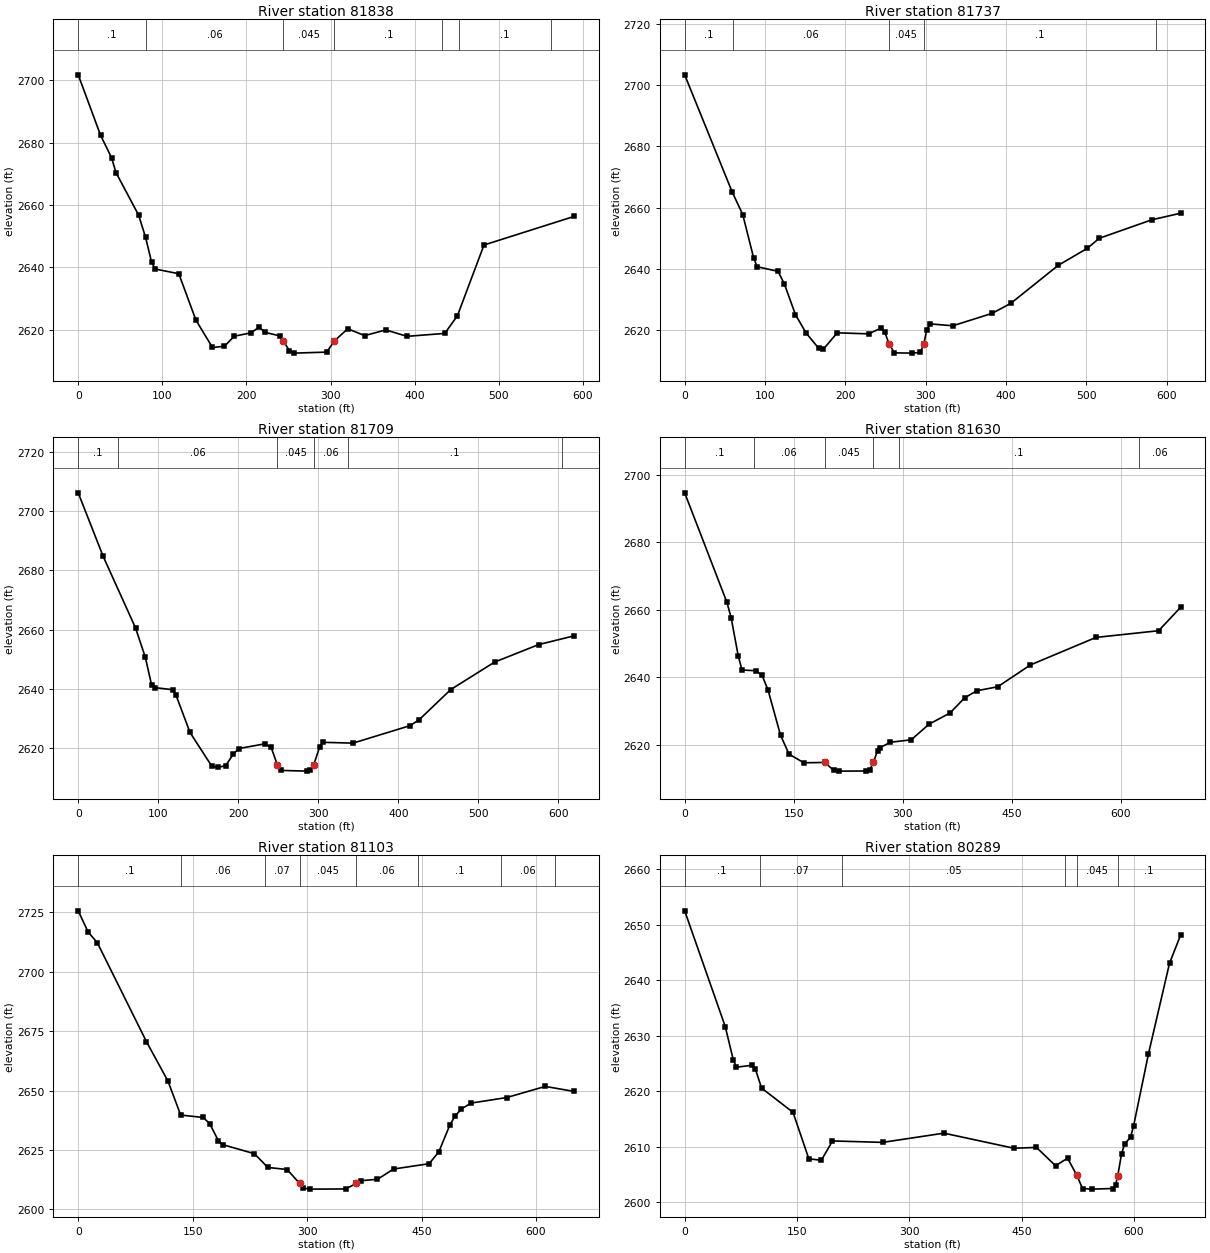
Type RM Length L Ch R = 1 ,81838   ,101,101,101
XS GIS Cut Line= 4
2377731.58238225676230.3394466782377826.61699553676191.107014421
 2378105.5158357675980.1265446592378227.88363301675918.383281245
#Sta/Elev= 30
       0 2701.82    26.6 2682.39    39.6 2675.24      45 2670.39    71.8 2656.79
      80 2649.73    87.2 2641.71    91.5 2639.48   119.6 2637.97   139.9  2623.1
   159.6 2614.29   173.8 2614.68   185.6 2617.93   205.1 2618.96   215.1 2620.82
   222.4 2619.12   239.5 2618.03  244.03 2616.37   250.9 2613.32   256.6 2612.48
   295.4 2612.81  304.682616.403   320.4 2620.31   340.5  2618.1   365.6 2619.93
   390.9 2617.87   435.8 2618.81   450.8 2624.47   482.4 2647.19   589.6 2656.37
#Mann= 7 ,-1,0
       0      .1       0      80     .06       0  244.03    .045       0
  304.68      .1       0  432.81     .05       0  452.52      .1       0
  562.52     .05       0
Bank Sta=244.03,304.68
XS Rating Curve= 0 ,0
Exp/Cntr=0.3,0.1

Type RM Length L Ch R = 1 ,81737   ,28.5,28.5,28.5
XS GIS Cut Line= 6
 2377753.1275526 676264.826954812377960.93386844676177.006162687
2377983.68854562676179.8504973352378074.70725436676168.473158743
2378099.35815465676158.9920432492378263.38145269675969.369733371
#Sta/Elev= 30
       0 2703.43      59 2665.15    72.3 2657.68    85.8 2643.56    90.2 2640.61
   116.2 2639.11   124.2 2634.92   137.9 2624.94     151 2618.98   166.9 2613.88
   172.7 2613.64     190 2618.98   228.9 2618.64     245 2620.58     249 2619.27
   254.3 2615.44   261.1 2612.42   283.6 2612.33   293.4  2612.6   297.62615.226
   301.4 2619.95   305.5  2621.9   333.7 2621.28   382.7 2625.34   406.1 2628.65
     465 2641.06   501.3 2646.64     516 2649.91   581.2 2655.95   617.4 2658.13
#Mann= 5 ,-1,0
       0      .1       0      60     .06       0   254.3    .045       0
   297.6      .1       0  586.67     .05       0
Bank Sta=254.3,297.6
XS Rating Curve= 0 ,0
Exp/Cntr(USF)=0,0
Exp/Cntr=0.3,0.1

Type RM Length L Ch R = 1 ,81709   ,78.7,78.7,78.7
XS GIS Cut Line= 6
2377763.69106988676286.6185602192377950.44768997676206.983760885
2377973.20236715676209.8280955332378064.22107589676198.450756941
2378088.87197618676188.969641447 2378269.2672598675980.636490909
#Sta/Elev= 30
       0 2706.11      31 2684.81    71.6 2660.58    83.8 2650.74    91.8 2641.22
      96 2640.45   117.9 2639.76   122.3 2637.84   139.7 2625.34   166.8 2614.02
   174.5 2613.55   184.4 2614.18   193.5 2617.95   200.6 2619.92   232.8 2621.49
     241 2620.38   248.82614.435   253.1 2612.55   285.4 2612.31   289.4 2612.53
  294.21  2614.4   301.5  2620.3   305.5 2622.02   343.4 2621.75   414.3 2627.61
   425.7 2629.54   465.5  2639.8   520.2 2649.05   575.2 2654.95   619.7 2657.91
#Mann= 6 ,-1,0
       0      .1       0      50     .06       0   248.8    .045       0
  294.21     .06       0  337.69      .1       0   604.1     .05       0
Bank Sta=248.8,294.21
XS Rating Curve= 0 ,0
Exp/Cntr(USF)=0,0
Exp/Cntr=0.3,0.1

Type RM Length L Ch R = 1 ,81630   ,527,527,527
XS GIS Cut Line= 3
2377830.13314402676368.7938990112377905.03395642676310.010982949
2378477.69333225676179.171589134
#Sta/Elev= 30
       0 2694.66    58.2 2662.18    63.9  2657.7    73.8 2646.25    78.9 2642.15
    98.5 2641.94   106.6 2640.53   114.8 2636.19   131.9 2622.86   143.6 2617.23
   164.1 2614.66   192.8 2614.76   205.1 2612.44   212.1 2612.19   250.2 2612.23
   254.4 2612.49  259.72 2614.78   265.5 2618.27   268.9 2619.14   283.1 2620.75
   311.8 2621.47   336.4  2626.1   365.1  2629.4   385.5 2633.93   402.1 2636.01
   430.8 2637.18   475.9 2643.66   566.1 2651.81   652.4  2653.8682.6294 2660.74
#Mann= 6 ,-1,0
       0      .1       0   95.21     .06       0   192.8    .045       0
  259.72     .06       0  295.21      .1       0  625.21     .06       0
Bank Sta=192.8,259.72
XS Rating Curve= 0 ,0
Exp/Cntr(USF)=0,0
Exp/Cntr=0.3,0.1

Type RM Length L Ch R = 1 ,81103   ,814.3,814.3,814.3
XS GIS Cut Line= 3
2377871.34852471676832.0113475442377995.23511595676847.240436916
2378491.89331219676676.143264798
#Sta/Elev= 30
       0 2725.69    12.9 2716.82      25 2712.29    89.5 2670.61   117.7    2654
   134.3 2639.74   163.9 2638.71   172.4  2636.1   183.8 2628.89   189.3 2627.29
     231 2623.47   248.5 2617.69   273.9 2616.81  290.212610.961     295 2609.01
   303.4 2608.56   350.6 2608.63  364.552610.962   371.2 2612.12   392.3  2612.7
   413.5 2617.03     460 2619.26   472.7 2624.25   487.3 2635.65   493.9 2639.24
   502.3 2642.32     515 2644.77   561.6  2647.1   612.3 2651.79   650.1 2649.67
#Mann= 8 ,-1,0
       0      .1       0  134.82     .06       0  244.82     .07       0
  290.21    .045       0  364.55     .06       0  444.82      .1       0
  554.82     .06       0  624.82     .05       0
Bank Sta=290.21,364.55
XS Rating Curve= 0 ,0
Exp/Cntr=0.3,0.1

Type RM Length L Ch R = 1 ,80289   ,517.1,517.1,517.1
XS GIS Cut Line= 3
2377906.32604511677430.9425822872378256.65110731677542.658354444
2378550.99405477677554.398504311
#Sta/Elev= 30
       0 2652.53    54.2 2631.67    64.9 2625.69    69.1 2624.36    90.1 2624.72
    94.3 2624.08   102.7  2620.6   144.7 2616.23   165.8 2607.86   182.5  2607.6
   197.4 2611.08   264.3 2610.82   346.2 2612.48   439.6 2609.77   469.8 2609.91
   495.3 2606.61   511.3 2607.98   523.7 2604.88   531.3 2602.51   543.4  2602.4
   571.4 2602.51   575.4  2603.1   578.32604.794   583.4 2608.73   587.4  2610.5
   595.4 2611.77   599.4 2613.73   619.4 2626.79   647.5  2643.1   662.3 2648.17
#Mann= 6 ,-1,0
       0      .1       0     100     .07       0     210     .05       0
  507.71      .1       0   523.7    .045       0   578.3      .1       0
Bank Sta=523.7,578.3
XS Rating Curve= 0 ,0
Exp/Cntr=0.3,0.1

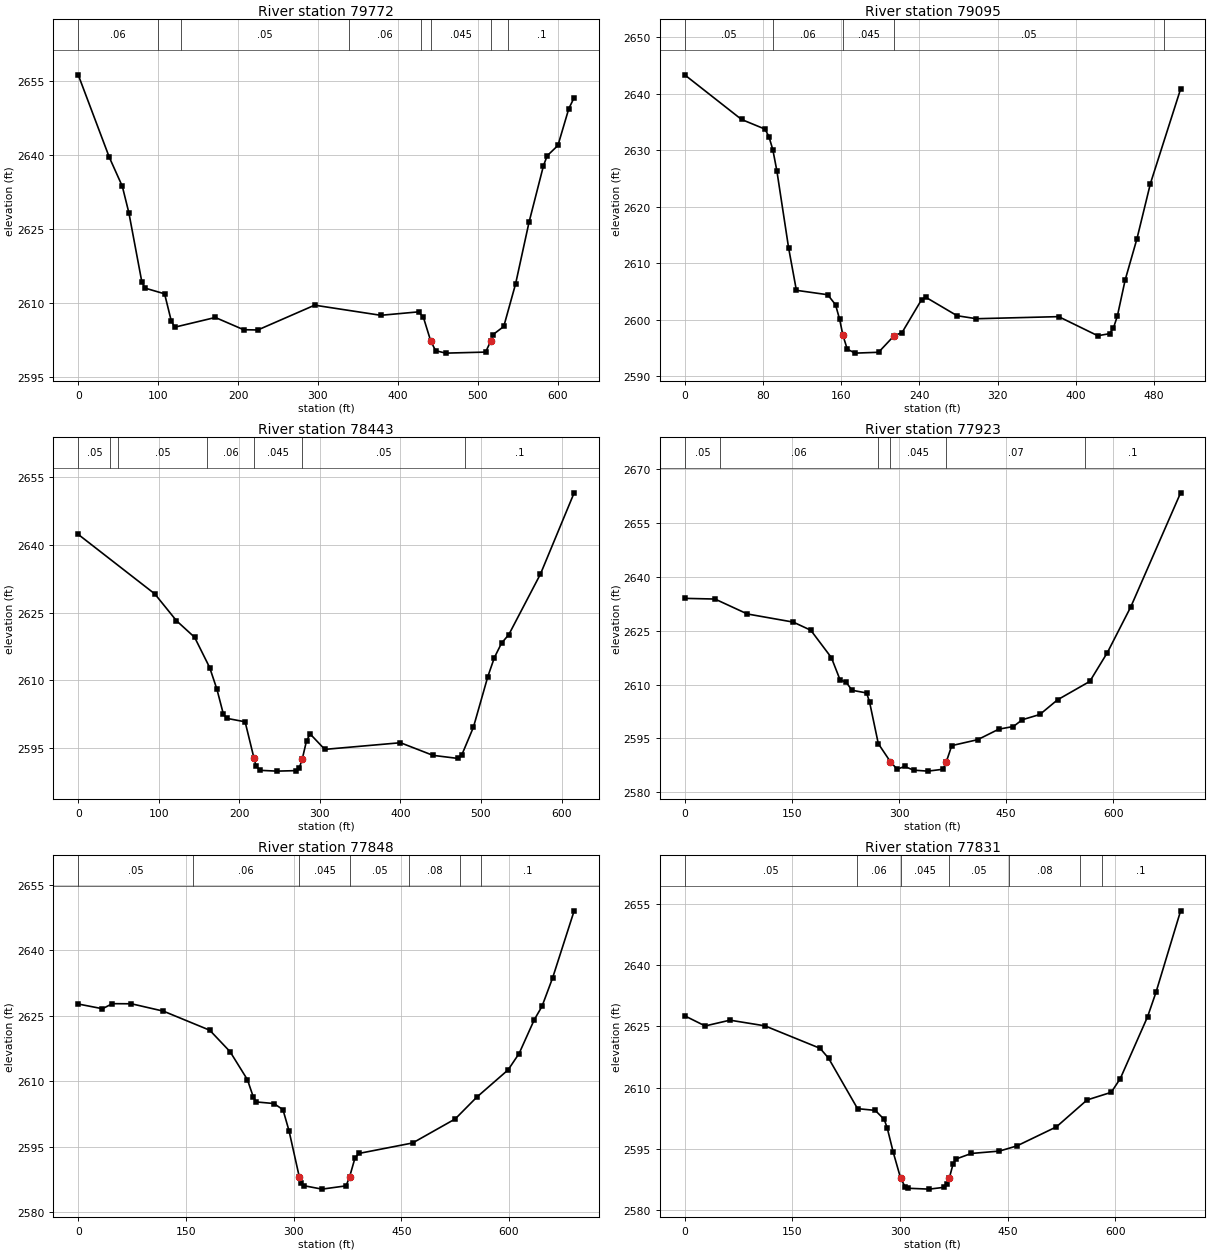
Type RM Length L Ch R = 1 ,79772   ,676.9,676.9,676.9
XS GIS Cut Line= 3
2377814.01241683677840.275195837 2377930.1695089677863.298143244
2378374.06886496 678098.31311061
#Sta/Elev= 30
       0 2656.23    38.9 2639.53    55.2 2633.65    63.4 2628.29    79.7 2614.23
    83.8 2613.03   108.1 2611.88   116.4 2606.44   120.7 2605.12   171.6 2607.09
   207.1 2604.61   224.8 2604.56   295.9 2609.58   378.7 2607.53   426.1 2608.23
     432 2607.13  441.122602.358   447.3 2600.36   460.1 2599.87   509.9 2600.08
  516.412602.358     519  2603.6   532.6 2605.27   547.4 2613.89   564.2 2626.36
   582.3 2637.82   586.9 2639.83   600.4 2641.93     614 2649.38   620.7 2651.61
#Mann= 8 ,-1,0
       0     .06       0     100     .07       0  128.42     .05       0
  338.42     .06       0  428.42     .05       0  441.12    .045       0
  516.41     .05       0  538.42      .1       0
Bank Sta=441.12,516.41
XS Rating Curve= 0 ,0
Exp/Cntr=0.3,0.1

Type RM Length L Ch R = 1 ,79095   ,651.8,651.8,651.8
XS GIS Cut Line= 2
2377714.07326389678614.5192789932378220.84141001678597.960408072
#Sta/Elev= 30
       0 2643.32    58.1 2635.42    82.1 2633.71    86.1 2632.39    90.1 2630.07
    94.2 2626.37   106.2 2612.73   114.2 2605.17   146.2 2604.39   154.2 2602.62
   158.4 2600.04  161.77  2597.2   166.2 2594.76   174.2 2594.05   198.2  2594.2
   214.2 2597.15   222.2 2597.69   242.2 2603.52   246.2 2603.97   278.5 2600.67
   298.3 2600.14   382.3 2600.51   422.3 2597.13   434.3 2597.49   438.3 2598.49
   442.3 2600.59   450.3    2607   462.3 2614.26   476.1 2624.06     507 2640.82
#Mann= 5 ,-1,0
       0     .05       0      90     .06       0  161.77    .045       0
   214.2     .05       0     490      .1       0
Bank Sta=161.77,214.2
XS Rating Curve= 0 ,0
Exp/Cntr=0.3,0.1

Type RM Length L Ch R = 1 ,78443   ,519.9,519.9,519.9
XS GIS Cut Line= 2
2377767.31797174 679359.709564542378316.56668386679081.374611305
#Sta/Elev= 30
       0  2642.3    95.1 2629.13     122  2623.2   144.5 2619.54   163.2 2612.85
   172.2 2608.05   180.3 2602.49   184.8  2601.6   207.2 2600.85  218.31 2592.74
   220.7 2591.18   225.2 2590.12   246.6 2589.94   270.4 2590.05   274.5 2590.65
  278.27 2592.71   283.5 2596.69     288 2598.15   306.1 2594.75   400.1 2596.22
   440.4 2593.43   471.8 2592.74   476.3 2593.56   490.6 2599.63   508.5 2610.83
   516.7 2615.07   525.6 2618.25   534.6 2620.14   573.9 2633.54   615.7 2651.49
#Mann= 7 ,-1,0
       0     .05       0      40     .08       0      50     .05       0
     160     .06       0  218.31    .045       0  278.27     .05       0
     480      .1       0
Bank Sta=218.31,278.27
XS Rating Curve= 0 ,0
Exp/Cntr=0.3,0.1

Type RM Length L Ch R = 1 ,77923   ,75.2,75.2,75.2
XS GIS Cut Line= 2
 2377856.3844949679798.916696533 2378531.8917248679639.417872377
#Sta/Elev= 30
       0 2634.04    42.4 2633.85    87.7 2629.69   151.9 2627.43   176.5 2625.16
   205.3 2617.54   217.6 2611.27   225.8 2610.75   234.1 2608.44   254.6 2607.69
   258.7 2605.21     271 2593.56  287.732588.587   297.2 2586.46     308  2587.2
   320.4 2586.18   340.4 2585.91   361.5 2586.43  366.31 2588.59   373.8 2593.02
   410.2 2594.68   439.6  2597.6   460.1 2598.34   472.4 2600.22   497.1 2601.69
   521.8 2605.77     567 2610.91   591.6 2618.94   624.5 2631.73   694.1 2663.44
#Mann= 6 ,-1,0
       0     .05       0      50     .06       0     270      .1       0
  287.73    .045       0  366.31     .07       0     560      .1       0
Bank Sta=287.73,366.31
XS Rating Curve= 0 ,0
Exp/Cntr=0.3,0.1

Type RM Length L Ch R = 1 ,77848   ,16.4,16.4,16.4
XS GIS Cut Line= 4
2377854.68427607679857.2960714892378108.29436129679822.180828919
2378256.55871881679776.6610700322378520.57332035679684.320987719
#Sta/Elev= 30
       0 2627.67    33.8 2626.59    47.5 2627.75    74.2 2627.72   118.6 2626.04
   183.2 2621.67   211.5 2616.76   235.7 2610.35   243.8 2606.42   247.8 2605.25
   272.6 2604.88   285.2 2603.48   293.6 2598.66     308 2588.04   310.3  2586.7
   314.5 2586.06   339.6 2585.28   373.1 2586.03  377.98 2588.07   385.6 2592.46
   391.2 2593.46   465.8 2595.85   525.1 2601.35   554.9  2606.3   598.8 2612.59
   614.1 2616.33   635.3 2624.09     646 2627.13   660.7  2633.6   690.8 2649.01
#Mann= 7 ,-1,0
       0     .05       0     160     .06       0     308    .045       0
  377.98     .05       0  461.12     .08       0  531.12     .07       0
  561.12      .1       0
Bank Sta=308,377.98
XS Rating Curve= 0 ,0
Exp/Cntr(USF)=0,0
Exp/Cntr=0.3,0.1

Type RM Length L Ch R = 1 ,77831   ,133.6,133.6,133.6
XS GIS Cut Line= 4
2377865.62641219679870.8155843382378119.23649741679835.700341768
2378267.50085493679790.1805828812378531.51545647679697.840500568
#Sta/Elev= 30
       0 2627.59    28.5 2625.11    63.1 2626.52   111.6 2625.14   188.6 2619.64
   200.4 2617.23   240.8 2604.89   265.4 2604.47   277.9 2602.27   282.1 2600.19
   290.5 2594.23  300.85 2587.85   307.2 2585.74   311.4 2585.43   340.7 2585.22
   361.6 2585.67   365.8 2586.49   368.52587.853     374 2591.46   378.4 2592.61
   399.3 2593.94   438.4 2594.52   462.7 2595.78   517.8 2600.44   560.5 2607.02
   594.1 2608.88   606.8 2612.25   644.8 2627.37   656.5 2633.34   690.8 2653.25
#Mann= 7 ,-1,0
       0     .05       0     240     .06       0  300.85    .045       0
   368.5     .05       0  451.12     .08       0  551.12     .06       0
  581.12      .1       0
Bank Sta=300.85,368.5
XS Rating Curve= 0 ,0
Exp/Cntr(USF)=0,0
Exp/Cntr=0.3,0.1

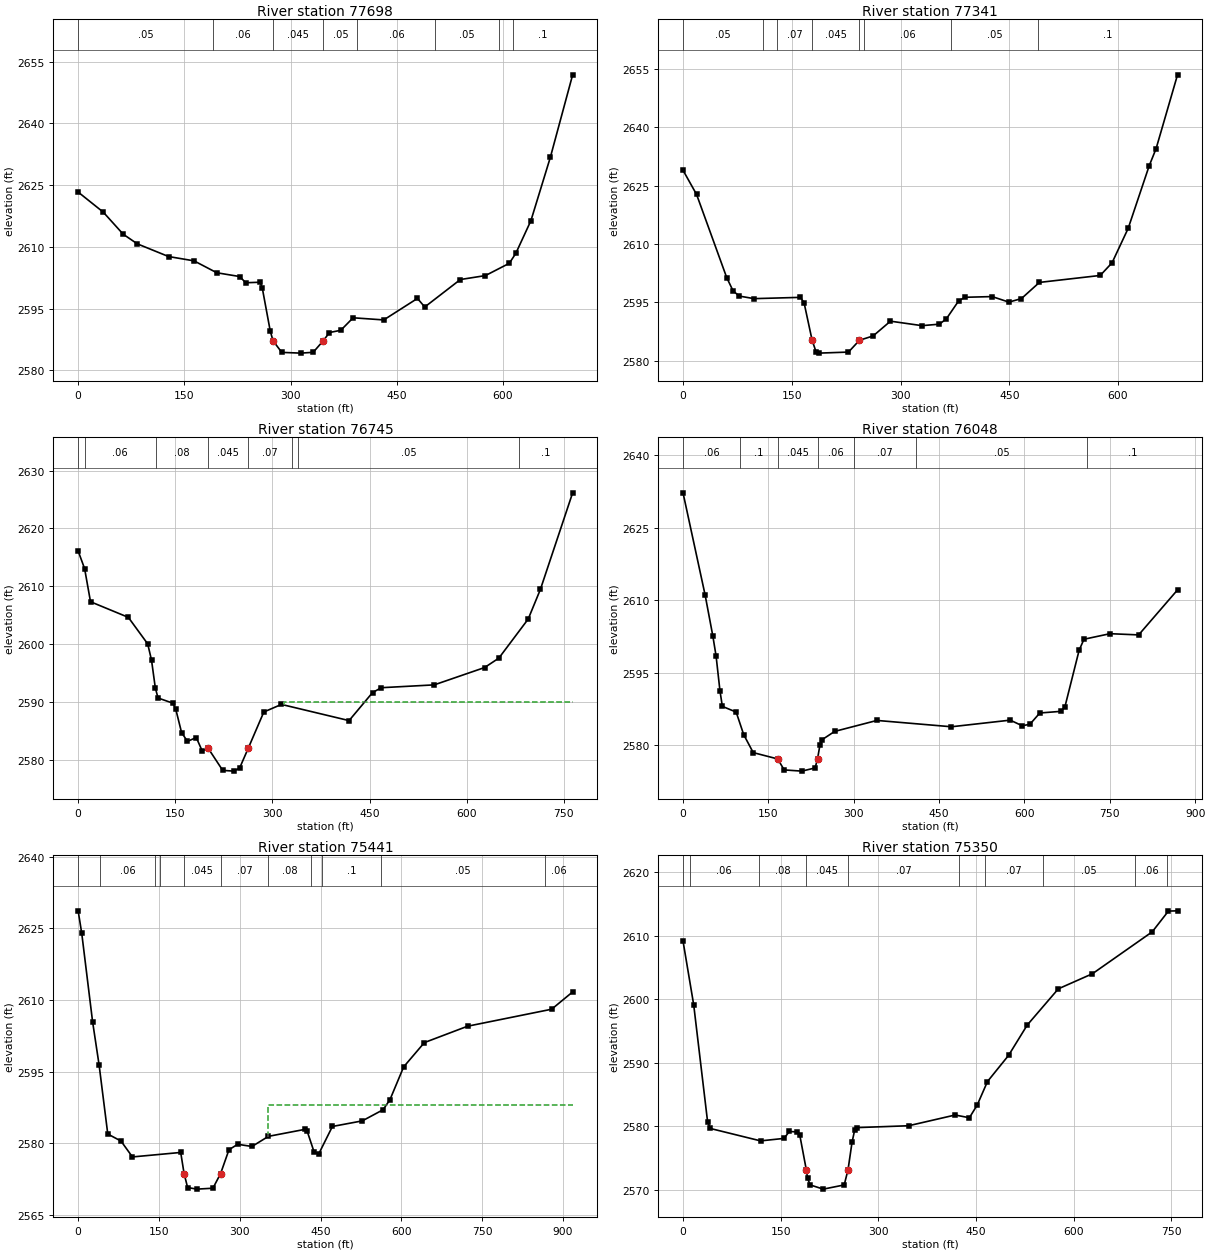
Type RM Length L Ch R = 1 ,77698   ,357.2,357.2,357.2
XS GIS Cut Line= 3
2377916.71024658679989.0306115362378140.81186504679976.386083217
2378578.64888404679794.582693409
#Sta/Elev= 30
       0 2623.33    35.5 2618.45    63.6 2613.09    83.6 2610.74   127.7 2607.66
   163.7 2606.61   195.8 2603.72   228.1  2602.8   236.8 2601.29     257 2601.41
   260.1 2600.02   271.4 2589.52  275.312587.188   287.6 2584.36   314.7 2584.18
     332 2584.38  346.252587.185     355 2589.19     371 2589.73   388.4 2592.77
   431.7 2592.25   479.3 2597.48   489.6 2595.39   539.9 2602.07   575.3 2603.03
     609 2606.01   618.2 2608.42   639.6  2616.4   667.1 2631.83   698.5 2651.83
#Mann= 8 ,-1,0
       0     .05       0     190     .06       0  275.31    .045       0
  346.25     .05       0  394.46     .06       0  504.46     .05       0
  594.46     .06       0  614.46      .1       0
Bank Sta=275.31,346.25
XS Rating Curve= 0 ,0
Exp/Cntr=0.3,0.1

Type RM Length L Ch R = 1 ,77341   ,595.3,595.3,595.3
XS GIS Cut Line= 2
2378190.87298757680387.6318267082378756.61402995680006.772010202
#Sta/Elev= 30
       0 2628.93    18.7 2622.71    60.3 2601.33    69.1 2597.92    77.6  2596.6
      98 2595.94     162 2596.27     167 2594.84  178.062585.238   183.5 2582.26
   187.1 2581.94   228.2 2582.21   243.3 2585.24   262.2 2586.36   286.1 2590.15
   329.5    2589   353.6 2589.38   363.2 2590.75   380.2 2595.38   388.9 2596.29
   426.3 2596.47   449.4 2595.05   466.7 2595.95   491.5 2600.11   575.4  2601.9
   591.7 2605.15     614 2614.02   642.9 2630.06   652.5 2634.51     682 2653.45
#Mann= 8 ,-1,0
       0     .05       0     110     .06       0     130     .07       0
  178.06    .045       0   243.3     .07       0     250     .06       0
     370     .05       0     490      .1       0
Bank Sta=178.06,243.3
XS Rating Curve= 0 ,0
Exp/Cntr=0.3,0.1

Type RM Length L Ch R = 1 ,76745   ,697.5,697.5,697.5
XS GIS Cut Line= 2
2378491.31922077680873.6987521592379164.65776681680513.748431991
#Sta/Elev= 30
       0 2616.08      10 2613.02    19.1  2607.3    77.5  2604.6   107.4 2600.01
   113.3  2597.2   119.2 2592.36   123.4 2590.65   146.1 2589.76   150.6 2588.77
   159.7 2584.67   168.8 2583.15   182.4 2583.81   191.5  2581.5   200.5    2582
   223.2 2578.13   240.4    2578   249.3 2578.53  262.83 2582.01   286.7 2588.23
   313.9 2589.54   418.3 2586.74   454.5 2591.58     468 2592.43   549.8 2592.92
   627.6 2595.92   649.6 2597.55   694.9 2604.31   713.8 2609.46   763.5 2626.14
#Mann= 8 ,-1,0
       0     .05       0      10     .06       0     120     .08       0
   200.5    .045       0  262.83     .07       0     330     .06       0
     340     .05       0     680      .1       0
#XS Ineff= 2 , 0
                           317.3            2590
Permanent Ineff=
       F       F
Bank Sta=200.5,262.83
XS Rating Curve= 0 ,0
Exp/Cntr=0.3,0.1

Type RM Length L Ch R = 1 ,76048   ,607.2,607.2,607.2
XS GIS Cut Line= 2
2378798.08520834 681451.576410022379629.50611117681198.786402696
#Sta/Elev= 30
       0 2632.22    38.9 2611.04    52.4 2602.59    58.1 2598.46    64.9 2591.27
    69.1 2588.03    93.4 2586.85   106.7 2582.16   123.4 2578.46  166.342577.152
   177.8 2574.88   208.8 2574.63   232.1 2575.29  236.382577.149   240.5 2579.96
   244.7 2581.16   266.5 2582.85   340.8 2585.12   471.7 2583.81     575 2585.18
   595.9 2584.03   609.5 2584.31     627 2586.66     664    2587   671.1 2587.93
   696.1 2599.64   704.6 2601.92   750.4 2603.07   800.7 2602.82     869 2612.13
#Mann= 7 ,-1,0
       0     .06       0     100      .1       0  166.34    .045       0
  236.38     .06       0     300     .07       0     410     .05       0
     710      .1       0
Bank Sta=166.34,236.38
XS Rating Curve= 0 ,0
Exp/Cntr=0.3,0.1

Type RM Length L Ch R = 1 ,75441   ,90.7,90.7,90.7
XS GIS Cut Line= 4
2378953.55230784682034.1681992472379025.80589338682026.140023076
2379592.59513102681815.8018074082379822.20096949681888.055392943
#Sta/Elev= 30
       0 2628.65     6.7 2623.93    26.8 2605.45    38.9 2596.38      55 2581.92
    79.5 2580.45   100.8 2577.12   190.4 2578.06  196.652573.647   203.2 2570.72
   220.3 2570.38   250.2 2570.57  264.512573.651     280 2578.63   296.2 2579.77
   322.7 2579.31   353.2 2581.43   420.8 2582.89   425.1 2582.54   437.9  2578.2
   446.4  2577.7     472  2583.5   527.5 2584.67   565.9 2586.99   578.7 2589.07
   604.3 2595.98   642.7 2601.06   722.9 2604.49     879 2608.05917.9638 2611.67
#Mann= 11 ,-1,0
       0      .1       0      40     .06       0   142.7     .08       0
   152.7      .1       0  196.65    .045       0  264.51     .07       0
   352.7     .08       0   432.7     .07       0   452.7      .1       0
   562.7     .05       0  867.26     .06       0
#XS Ineff= 2 , 0
                          352.35         2588.02
Permanent Ineff=
       F       F
Bank Sta=196.65,264.51
XS Rating Curve= 0 ,0
Exp/Cntr(USF)=0,0
Exp/Cntr=0.3,0.1

Type RM Length L Ch R = 1 ,75350   ,49.3,49.3,49.3
XS GIS Cut Line= 4
2378976.77741962682094.043908754  2379029.615946 682074.59427907
2379355.55989853682048.9041153252379626.28131768682309.877823514
#Sta/Elev= 30
       0 2609.15    16.4 2599.13    37.7 2580.75      42 2579.67   119.1 2577.72
   155.2 2578.11   163.2  2579.2   175.2 2579.13   179.2 2578.68  189.31 2573.17
   191.3 2571.81   195.3 2570.79   215.4 2570.13   247.5 2570.79   253.4 2573.19
   259.5 2577.49   263.5 2579.39   267.5 2579.81   346.4  2580.1   417.8 2581.79
   439.7 2581.36   451.8 2583.37   467.5 2587.06   499.9 2591.17   528.6 2595.95
   576.3 2601.64   628.6 2604.01   720.5 2610.61   745.3 2613.87   759.3 2613.91
#Mann= 10 ,-1,0
       0      .1       0      10     .06       0   116.3     .08       0
  189.31    .045       0   253.4     .07       0  423.26     .08       0
  463.26     .07       0  553.26     .05       0  693.26     .06       0
  743.26      .1       0
Bank Sta=189.31,253.4
XS Rating Curve= 0 ,0
Exp/Cntr=0.3,0.1