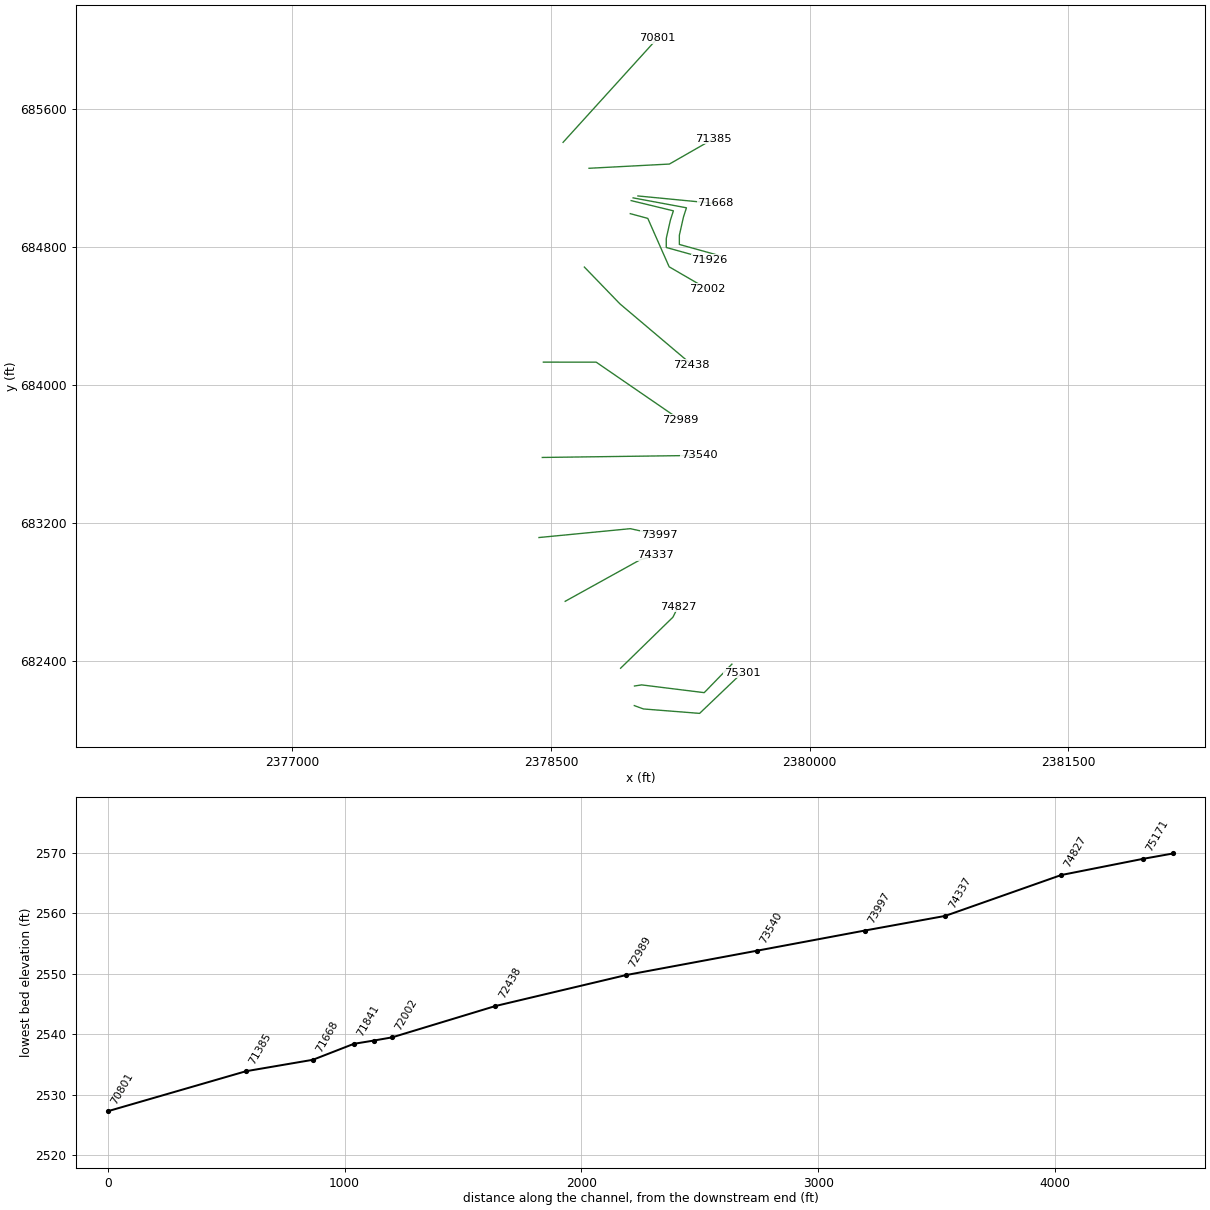
HEC-RAS study DRKFK_2.prj: DRKFK_2

--- DRKFK_2.g01 (geometry) --- (continued)

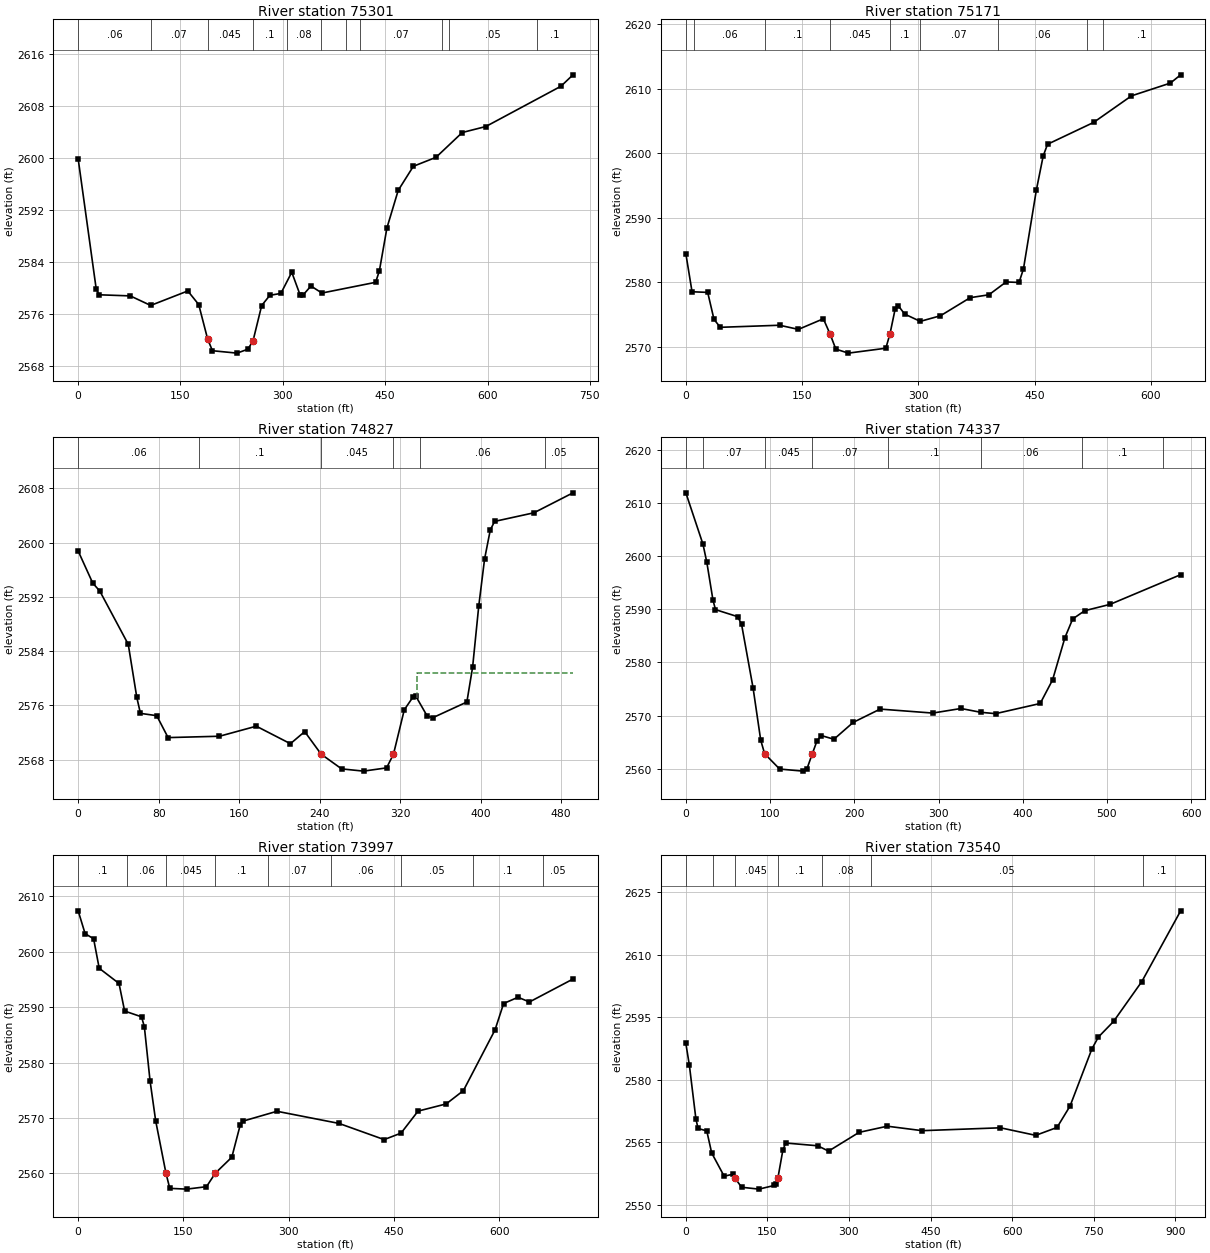
Type RM Length L Ch R = 1 ,75301   ,130,130,130
XS GIS Cut Line= 4
2378983.28799973682142.2991604922379036.12652611682122.849530808
2379362.07047864682097.1593670632379609.40334697682333.445160492
#Sta/Elev= 30
       0 2599.83    26.5 2579.75    30.8 2578.89    76.4 2578.72   106.3 2577.25
   160.7 2579.48   176.7 2577.39   189.72572.111   196.8 2570.28   232.9 2569.91
   248.9 2570.52   256.42571.836     269 2577.24     281 2578.81   297.1  2579.1
   313.1 2582.36   325.2  2578.9   329.2  2578.8   341.2 2580.24   357.3 2579.16
     436 2580.81   441.5 2582.57   452.6 2589.19   469.1 2594.96   491.3 2598.67
   524.5 2600.05     563 2603.87   597.5 2604.79   707.6 2610.99   725.3 2612.75
#Mann= 11 ,-1,0
       0     .06       0   106.3     .07       0   189.7    .045       0
   256.4      .1       0   306.3     .08       0   356.3     .07       0
  393.26     .08       0  413.26     .07       0  533.26     .06       0
  543.26     .05       0  673.26      .1       0
Bank Sta=189.7,256.4
XS Rating Curve= 0 ,0
Exp/Cntr=0.3,0.1

Type RM Length L Ch R = 1 ,75171   ,344,344,344
XS GIS Cut Line= 4
2378984.27947166682255.9088417732379026.02598774682262.331382709
2379388.89955065682217.3735961542379549.46307406682382.754025267
#Sta/Elev= 30
       0 2584.41       8 2578.51    28.2 2578.41    36.3 2574.24    44.4    2573
     121 2573.32   145.2 2572.68   177.4 2574.32     186 2571.98   193.5 2569.62
   209.7    2569     258 2569.76  263.36 2571.98   270.1 2575.87   274.1 2576.35
   282.2 2575.06   302.4 2573.92   328.5 2574.79   366.8 2577.59     391 2578.04
   413.2 2580.03   429.9 2579.95   435.6 2582.07   452.2 2594.26     461 2599.53
   466.6 2601.36     526 2604.74   574.9 2608.86   625.1 2610.84   638.4 2612.12
#Mann= 9 ,-1,0
       0      .1       0      10     .06       0  102.24      .1       0
     186    .045       0  263.36      .1       0  302.24     .07       0
  402.24     .06       0  517.89     .07       0  537.89      .1       0
Bank Sta=186,263.36
XS Rating Curve= 0 ,0
Exp/Cntr(USF)=0,0
Exp/Cntr=0.3,0.1

Type RM Length L Ch R = 1 ,74827   ,489.6,489.6,489.6
XS GIS Cut Line= 3
 2378903.8648012 682359.076774132379207.39864478682655.204483913
2379237.70583115682715.950789434
#Sta/Elev= 30
       0 2598.76    14.5 2594.03    21.5 2592.86    49.8 2585.01    58.3 2577.19
    61.9 2574.84    78.1  2574.5    89.4 2571.27   140.5 2571.47   177.1 2572.95
     211 2570.37   225.2 2572.15  241.562568.827   261.9 2566.66   283.7 2566.33
   306.6 2566.81  313.462568.828   324.2 2575.37   332.7 2577.21   335.5 2577.41
   346.9 2574.46   352.4 2574.19   386.4 2576.51   392.1 2581.63   398.2 2590.63
     404 2597.57   409.7 2601.87     414 2603.12   453.1 2604.39   491.9 2607.33
#Mann= 6 ,-1,0
       0     .06       0     120      .1       0  241.56    .045       0
  313.46      .1       0     340     .06       0  464.06     .05       0
#XS Ineff= 2 , 0
                          336.46         2580.78
Permanent Ineff=
       F       F
Bank Sta=241.56,313.46
XS Rating Curve= 0 ,0
Exp/Cntr=0.3,0.1

Type RM Length L Ch R = 1 ,74337   ,339.5,339.5,339.5
XS GIS Cut Line= 3
2378582.36306657682747.1977521592379016.67334946682987.665181272
2379104.16742179683012.977489014
#Sta/Elev= 30
       0 2611.87    20.4 2602.18    24.9 2598.82    32.2 2591.72    35.2 2589.92
    61.5  2588.6    66.1  2587.2    79.8 2575.23    88.9 2565.39   93.512562.847
   111.4 2559.96   139.2 2559.57   143.8 2560.01  150.172562.846   155.8 2565.29
     161 2566.25   175.8 2565.56   198.7 2568.73   230.7 2571.23   293.1 2570.48
   326.7 2571.34     350 2570.63   367.7 2570.37   420.7 2572.28   435.4 2576.71
   450.1 2584.67   459.3 2588.17   473.6 2589.72   503.7 2590.91   587.5 2596.49
#Mann= 8 ,-1,0
       0      .1       0      20     .07       0   93.51    .045       0
  150.17     .07       0     240      .1       0     350     .06       0
     470      .1       0  566.44     .05       0
Bank Sta=93.51,150.17
XS Rating Curve= 0 ,0
Exp/Cntr=0.3,0.1

Type RM Length L Ch R = 1 ,73997   ,457,457,457
XS GIS Cut Line= 3
2378430.27699298 683117.087040412378960.13662023683168.467367902
2379128.72831981683131.537757518
#Sta/Elev= 30
       0 2607.38     9.9 2603.26      22 2602.34      30 2597.01    58.2 2594.27
    66.2 2589.29    90.3 2588.25    94.3 2586.47   102.4 2576.71   110.4  2569.5
  125.082560.027   130.5 2557.29   154.6 2557.15   182.8 2557.59   195.4 2560.03
   218.9 2562.91     231 2568.79     235 2569.43   283.2  2571.2   371.6 2569.01
   435.9 2566.09     460 2567.26   484.2 2571.23   524.3 2572.53   548.8 2574.93
   593.8 2585.87   606.1 2590.65   626.6 2591.78   642.9 2590.93 704.934 2595.07
#Mann= 9 ,-1,0
       0      .1       0      70     .06       0  125.08    .045       0
   195.4      .1       0     270     .07       0     360     .06       0
     460     .05       0  562.34      .1       0  662.34     .05       0
Bank Sta=125.08,195.4
XS Rating Curve= 0 ,0
Exp/Cntr(USF)=0,0
Exp/Cntr=0.3,0.1

Type RM Length L Ch R = 1 ,73540   ,551.5,551.5,551.5
XS GIS Cut Line= 2
2378449.65676393683581.5578362542379359.57876393683593.474836254
#Sta/Elev= 30
       0 2588.74     6.5 2583.48    18.5 2570.62    22.5 2568.34    38.5 2567.75
    47.5 2562.47    70.5 2556.89    86.5 2557.38   89.982556.518   102.5 2554.25
   134.5  2553.8   162.5 2554.68   166.5 2555.09  169.372556.518   178.5  2563.2
   183.7 2564.85   242.5 2564.19   262.5 2562.91   318.5  2567.4   370.5 2568.88
   434.6 2567.81   578.6  2568.5   643.4 2566.69   682.6 2568.58   706.6 2573.72
   746.6 2587.36   758.6 2590.24   786.6 2593.99   838.6 2603.56     910  2620.5
#Mann= 7 ,-1,0
       0      .1       0      50     .06       0   89.98    .045       0
  169.37      .1       0     250     .08       0     340     .05       0
     840      .1       0
Bank Sta=89.98,169.37
XS Rating Curve= 0 ,0
Exp/Cntr=0.3,0.1

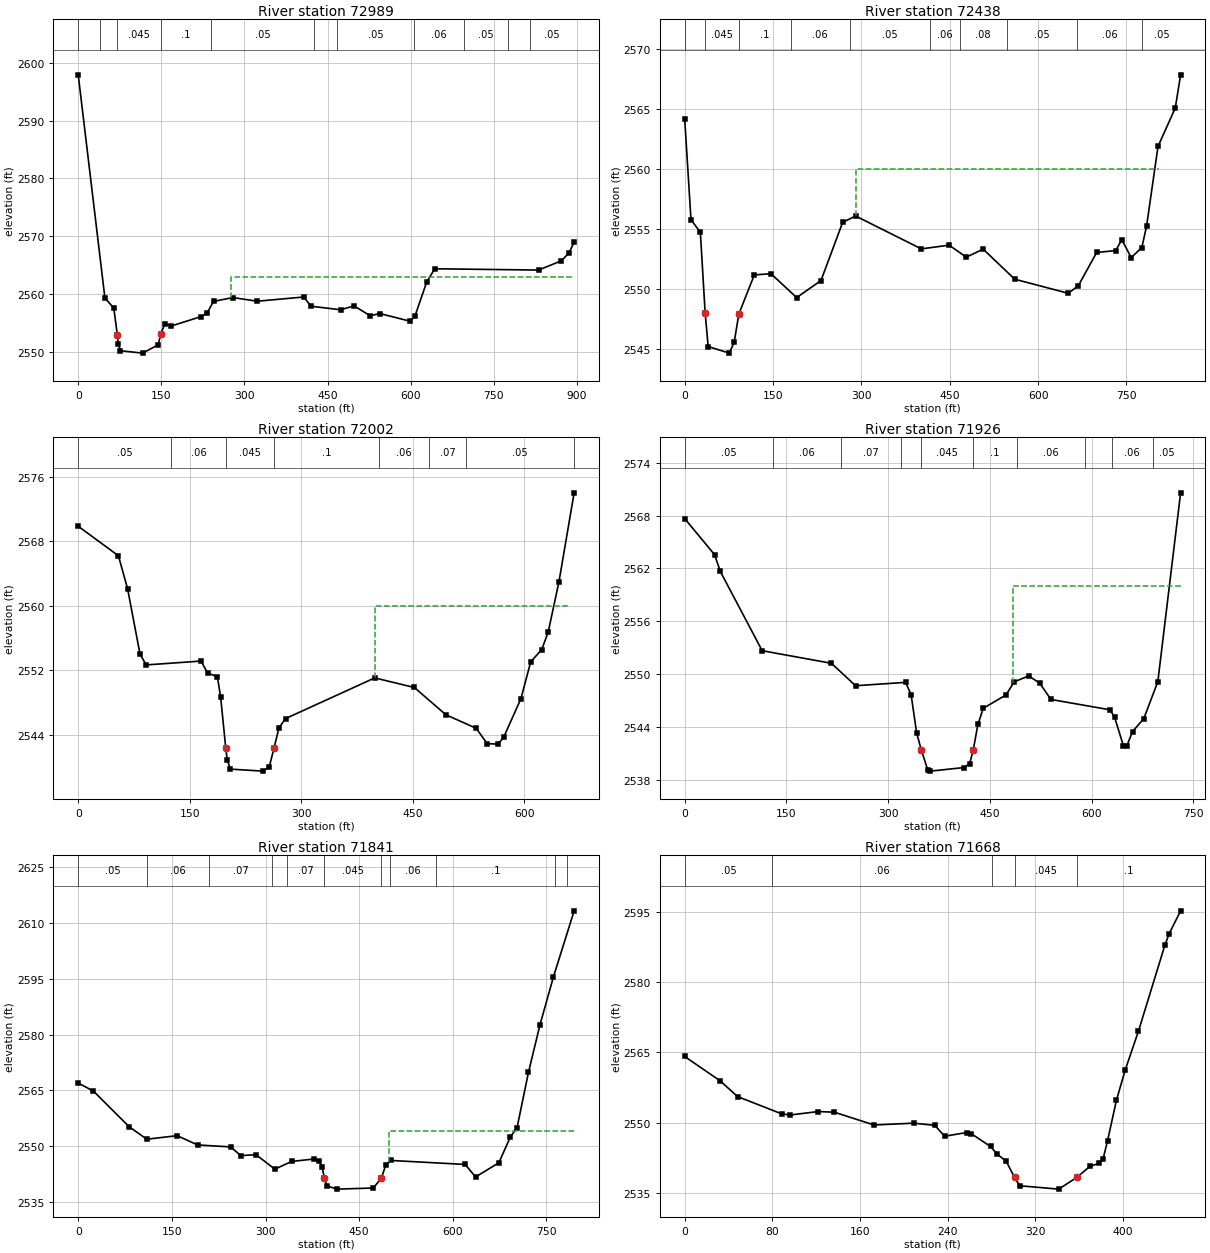
Type RM Length L Ch R = 1 ,72989   ,551.4,551.4,551.4
XS GIS Cut Line= 3
 2378455.9548458 684134.501798982378762.29333574  684134.2840092
2379247.63472774683800.787992345
#Sta/Elev= 30
       0 2597.92    48.2 2559.31    64.2 2557.57    70.62552.971    72.2 2551.43
    76.2  2550.2   116.2 2549.78   144.2 2551.21   149.1  2553.1   156.2 2554.82
   168.2 2554.48   221.4 2556.09   232.2 2556.64   244.2 2558.73   279.1 2559.39
   323.2 2558.76   407.2 2559.49   420.2 2557.89   473.6 2557.28   497.9 2557.95
     527 2556.25   544.4 2556.63     599  2555.3   607.7 2556.15   628.9 2562.04
   643.5 2564.37     831 2564.15   872.3 2565.76   886.2 2567.16   895.2 2569.01
#Mann= 11 ,-1,0
       0      .1       0      40     .06       0    70.6    .045       0
   149.1      .1       0     240     .05       0  426.34     .06       0
  466.34     .05       0  606.34     .06       0  696.34     .05       0
  776.34      .1       0  816.34     .05       0
#XS Ineff= 2 , 0
                           276.2            2563
Permanent Ineff=
       F       F
Bank Sta=70.6,149.1
XS Rating Curve= 0 ,0
Exp/Cntr=0.3,0.1

Type RM Length L Ch R = 1 ,72438   ,435.8,435.8,435.8
XS GIS Cut Line= 3
2378693.67909142684685.8584890142378899.79213844684472.580401186
2379316.21890544684120.358664999
#Sta/Elev= 30
       0 2564.21    10.7 2555.79    26.6 2554.73    34.82547.994    39.9 2545.21
    75.8 2544.66    84.2  2545.6    91.92547.908   118.2 2551.18   146.5 2551.28
   190.1 2549.29   231.4 2550.71   268.2 2555.56   290.2 2556.09   401.9 2553.35
     449 2553.66   478.1 2552.66   506.7 2553.33   560.4 2550.82   651.2 2549.65
   668.3 2550.28   699.5 2553.05   731.9 2553.21   742.1 2554.12   758.1 2552.63
   776.1 2553.45   784.3 2555.27   803.6 2561.89   832.9 2565.09     842 2567.86
#Mann= 10 ,-1,0
       0     .06       0    34.8    .045       0    91.9      .1       0
     180     .06       0     280     .05       0   416.6     .06       0
   466.6     .08       0   546.6     .05       0   666.6     .06       0
   776.6     .05       0
#XS Ineff= 1 ,-1
   290.8 804.891    2560
Permanent Ineff=
       F
Bank Sta=34.8,91.9
XS Rating Curve= 0 ,0
Exp/Cntr=0.3,0.1

Type RM Length L Ch R = 1 ,72002   ,76,76,76
XS GIS Cut Line= 4
2378959.95560076684995.6555155542379061.48683683684968.191140586
2379185.50888992684687.3008260672379406.12006413684559.187354045
#Sta/Elev= 30
       0 2569.87    54.1 2566.21    66.5 2562.09    83.1 2554.03    91.4 2552.66
   165.3 2553.14   174.1 2551.65   187.2 2551.21   191.6 2548.73  198.47 2542.39
   200.5 2540.91   204.7 2539.73   248.4 2539.48   257.1 2540.01  263.58 2542.39
   270.2 2544.87     279    2546     399 2551.05   452.3 2549.86   494.7 2546.48
   535.6 2544.79   550.3 2542.89     565 2542.83   572.6  2543.7   595.7 2548.47
   608.9 2553.05   623.6 2554.55   632.3  2556.7   646.9 2562.98   667.3 2574.02
#Mann= 8 ,-1,0
       0     .05       0  125.18     .06       0  198.47    .045       0
  263.58      .1       0  405.18     .06       0  472.23     .07       0
  522.23     .05       0  667.34      .1       0
#XS Ineff= 1 ,-1
     399   658.9    2560
Permanent Ineff=
       F
Bank Sta=198.47,263.58
XS Rating Curve= 0 ,0
Exp/Cntr=0.3,0.1

Type RM Length L Ch R = 1 ,71926   ,85.6,85.6,85.6
XS GIS Cut Line= 6
 2378965.0991041685071.2951540842379210.00896008685012.043005575
2379192.64986916684958.2331833832379168.75745812684852.423934471
2379168.75745812684799.5193100152379420.48107448684729.548677671
#Sta/Elev= 30
       0 2567.67    44.1 2563.57    52.5 2561.67   114.3 2552.65   216.4 2551.22
     252 2548.67   325.8 2549.05   333.9 2547.66   342.1 2543.31     349 2541.35
   358.4 2539.11   362.5 2538.96   412.1 2539.37   420.3 2539.82  425.71  2541.4
   432.4 2544.27   440.4 2546.11   473.7 2547.61   486.1 2549.12   507.3 2549.78
   523.5 2548.97   540.1 2547.11   627.3 2545.93     634 2545.09     647 2541.85
   652.2 2541.86   660.5 2543.46   677.1 2544.93   697.8 2549.14   731.4  2570.6
#Mann= 10 ,-1,0
       0     .05       0     130     .06       0     230     .07       0
  318.52     .08       0     349    .045       0  425.71      .1       0
  490.11     .06       0  590.11      .1       0  630.11     .06       0
  690.11     .05       0
#XS Ineff= 1 ,-1
484.6229731.3754    2560
Permanent Ineff=
       F
Bank Sta=349,425.71
XS Rating Curve= 0 ,0
Exp/Cntr(USF)=0,0
Exp/Cntr=0.3,0.1

Type RM Length L Ch R = 1 ,71841   ,173,173,173
XS GIS Cut Line= 6
2378976.21422753685087.2119636642379285.77529691 685029.67621905
2379268.41620599684975.8663968582379244.52379495684870.057147946
2379244.52379495 684817.152523492379496.24741131684747.181891146
#Sta/Elev= 30
       0 2566.95    24.4 2564.78    81.3 2555.24   109.8 2551.84   158.6 2552.79
   191.2 2550.29   244.1 2549.77   260.3 2547.44   284.8 2547.67   314.9 2543.79
     342 2545.86   378.2 2546.52   386.3 2545.85   390.4 2544.44   394.4 2541.34
   398.5 2539.28   414.3 2538.41   472.6 2538.71  485.49 2541.35   492.9 2545.03
   500.9 2546.12   619.8 2545.05   636.4 2541.68   673.8 2545.52   691.9 2552.37
   702.9 2554.98   721.1 2569.81   739.5 2582.58     761 2595.44   794.3 2613.28
#Mann= 11 ,-1,0
       0     .05       0     110     .06       0     210     .07       0
     310      .1       0  334.86     .07       0   394.4    .045       0
  485.49     .08       0  499.98     .06       0     573      .1       0
     763     .05       0     783      .1       0
#XS Ineff= 2 , 0
                          498.48          2554.1
Permanent Ineff=
       F       F
Bank Sta=394.4,485.49
XS Rating Curve= 0 ,0
Exp/Cntr(USF)=0,0
Exp/Cntr=0.3,0.1

Type RM Length L Ch R = 1 ,71668   ,282.4,282.4,282.4
XS GIS Cut Line= 2
2379004.22489952685098.3255249452379454.56392717 685054.76741781
#Sta/Elev= 30
       0 2564.14    32.1 2558.98    48.2 2555.57    88.4 2551.88    96.4 2551.63
   121.9 2552.37   136.6 2552.22   172.8 2549.49   208.9 2549.88   228.2 2549.41
   237.1 2547.08   257.1 2547.87   261.2 2547.66     279 2544.89   285.3 2543.21
   293.3 2541.72   300.9 2538.27   305.6 2536.49   341.2 2535.77   357.6 2538.26
   369.7 2540.64   377.7 2541.28   381.7 2542.25   385.8 2546.17   393.8 2554.74
   401.8 2561.22   413.9 2569.53     438 2587.92     442 2590.44   452.4  2595.3
#Mann= 5 ,-1,0
       0     .05       0      80     .06       0     280      .1       0
   300.9    .045       0   357.6      .1       0
Bank Sta=300.9,357.6
XS Rating Curve= 0 ,0
Exp/Cntr(USF)=0,0
Exp/Cntr=0.3,0.1

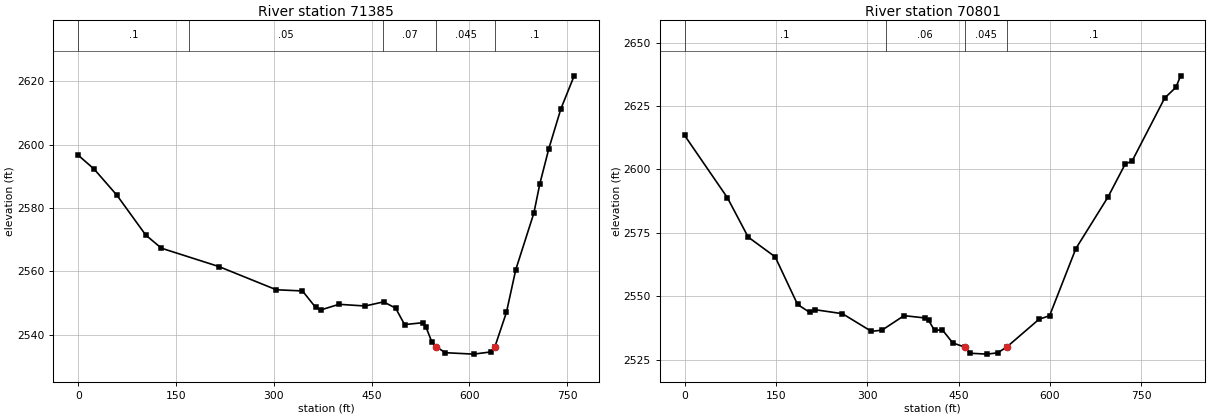
Type RM Length L Ch R = 1 ,71385   ,583.6,583.6,583.6
XS GIS Cut Line= 3
2378720.78254979 685258.87003914 2379187.0310766685283.406067216
2379441.82454979685429.344348061
#Sta/Elev= 30
       0 2596.66    24.5 2592.25    59.5 2583.99   103.5 2571.47   127.6 2567.31
   215.7 2561.52   303.8 2554.19   343.9 2553.82   363.9 2548.66   371.9 2547.82
   399.9  2549.6     440 2549.07   468.2 2550.37   486.7 2548.41   500.5  2543.2
   528.1 2543.79   533.5 2542.31   542.3  2537.7  549.02 2536.23   562.8 2534.33
   606.5 2533.88   633.2 2534.59     639 2536.23   656.6 2547.02     671 2560.56
   698.7 2578.38   707.9 2587.66   721.7 2598.76   740.2 2611.32   760.5 2621.71
#Mann= 5 ,-1,0
       0      .1       0     170     .05       0  466.89     .07       0
  549.02    .045       0     639      .1       0
Bank Sta=549.02,639
XS Rating Curve= 0 ,0
Exp/Cntr=0.3,0.1

Type RM Length L Ch R = 1 ,70801   ,640.5,640.5,640.5
XS GIS Cut Line= 2
2378570.12808885685409.2712532092379117.36404807686012.559004279
#Sta/Elev= 30
       0 2613.38    70.1 2588.89   104.3 2573.36   148.6 2565.58   185.4 2546.82
   205.1 2543.75   213.8 2544.77   259.1 2543.19   306.7 2536.22   324.2 2536.72
   360.3 2542.42   394.1 2541.52   400.7 2540.51   410.3 2536.64   423.3 2536.79
   440.3 2531.66     4602530.052   468.6 2527.61   496.7 2527.26   513.9 2527.77
  528.972530.054   581.9 2540.98   599.3 2542.39   642.5 2568.85   695.2 2589.13
   723.5 2602.14   734.8 2603.31   788.3 2628.11   806.8 2632.37   814.5 2636.88
#Mann= 4 ,-1,0
       0      .1       0     330     .06       0     460    .045       0
  528.97      .1       0
Bank Sta=460,528.97
XS Rating Curve= 0 ,0
Exp/Cntr=0.3,0.1