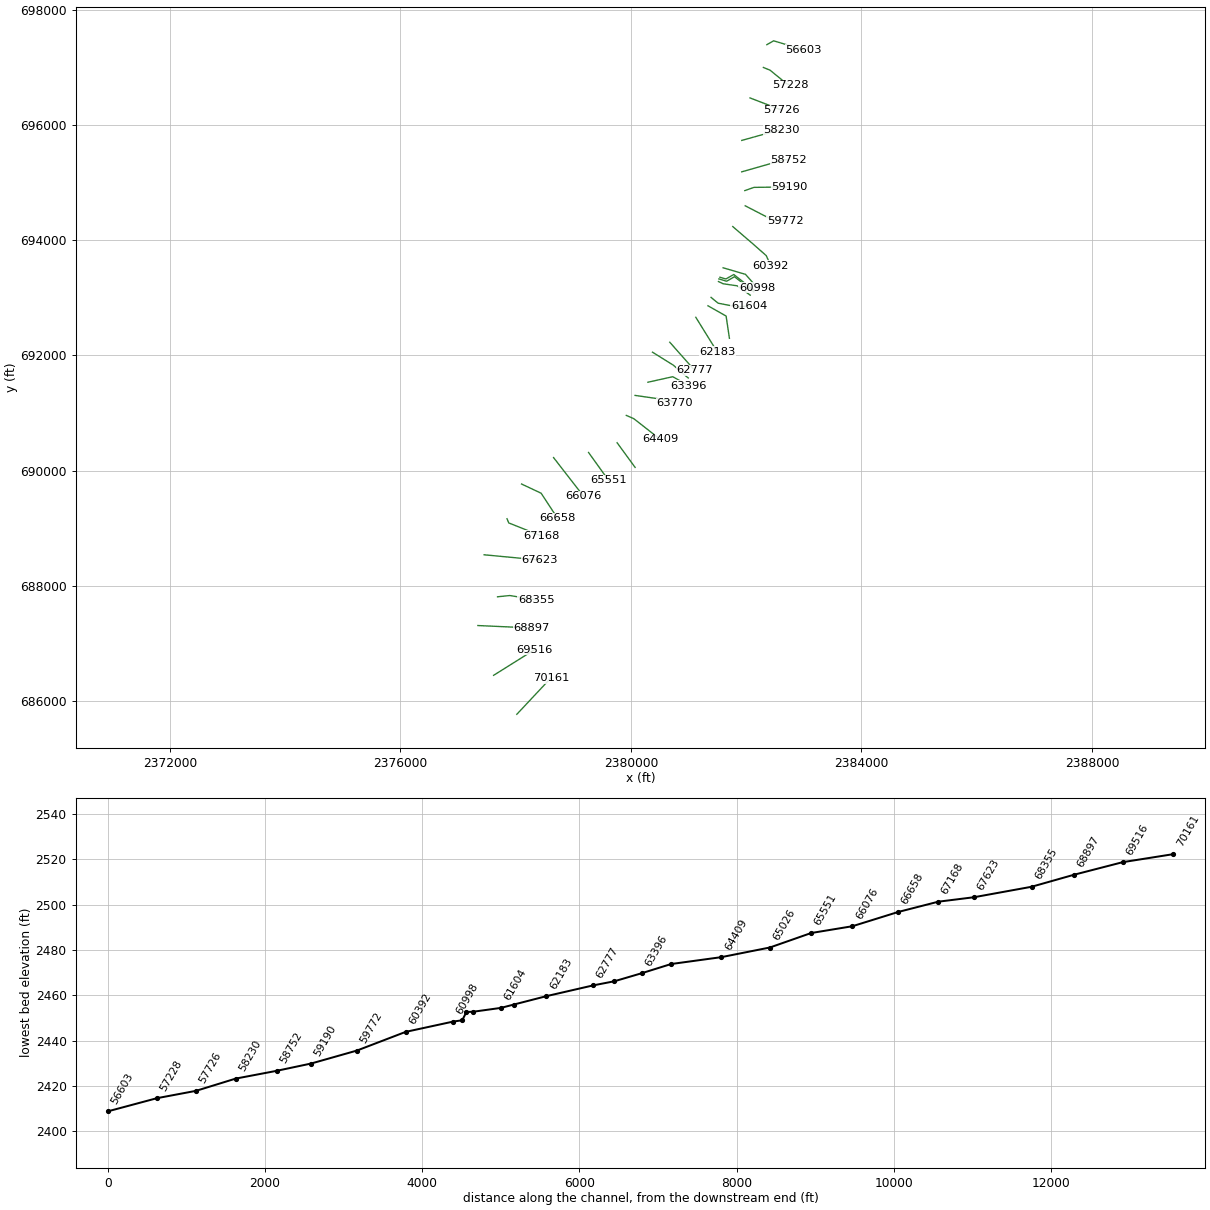
HEC-RAS study DRKFK_2.prj: DRKFK_2

--- DRKFK_2.g01 (geometry) --- (continued)

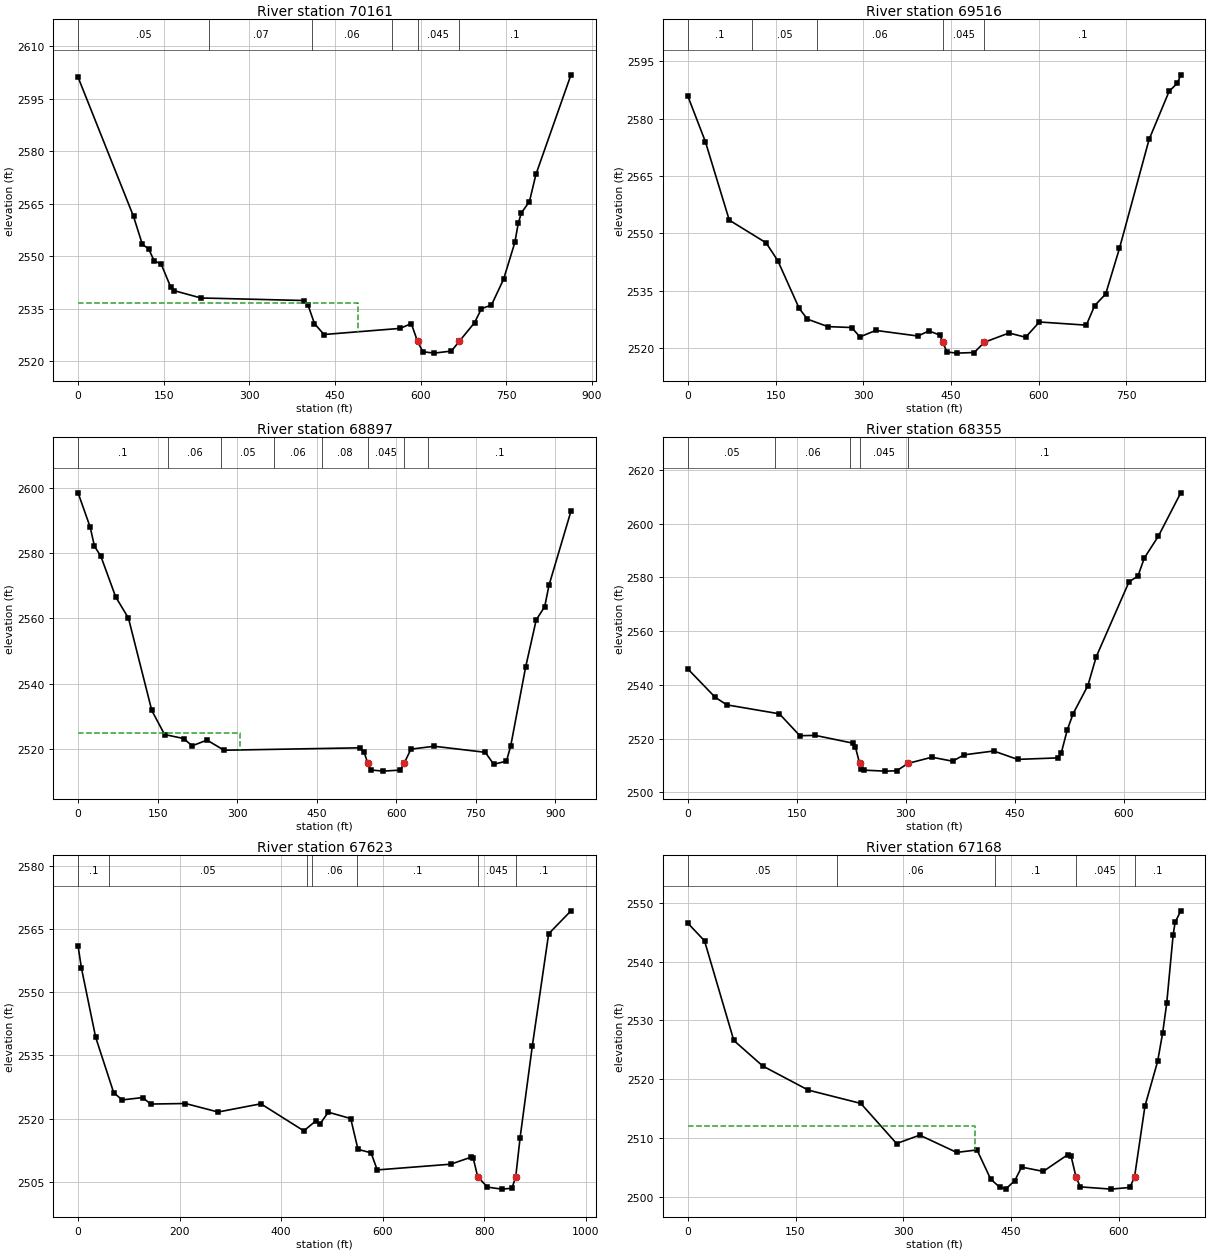
Type RM Length L Ch R = 1 ,70161   ,645,645,645
XS GIS Cut Line= 2
2378021.17796652685770.9882197332378611.36306695686400.804595268
#Sta/Elev= 30
       0 2601.09    97.1 2561.32   112.6 2553.32   123.6 2552.05   133.1 2548.65
   145.5 2547.71   162.1 2541.17   167.8 2540.12     215 2538.01   396.3 2537.28
   402.7 2535.97     414 2530.67   430.6 2527.57     564 2529.32   583.5 2530.69
   594.42525.635   603.6 2522.65   623.4 2522.25   653.7 2522.84  667.612525.635
   694.2 2530.94   706.4 2534.95   723.9 2535.99   745.1 2543.36   764.9 2553.91
   770.7 2559.29   776.2  2562.3   790.4 2565.56   801.7  2573.3   863.1 2601.77
#Mann= 6 ,-1,0
       0     .05       0     230     .07       0     410     .06       0
     550     .05       0   594.4    .045       0  667.61      .1       0
#XS Ineff= 2 , 0
          490.97 2536.57
Permanent Ineff=
       F       F
Bank Sta=594.4,667.61
XS Rating Curve= 0 ,0
Exp/Cntr=0.3,0.1

Type RM Length L Ch R = 1 ,69516   ,618.2,618.2,618.2
XS GIS Cut Line= 2
2377618.85324163686447.5732751072378333.02068412686895.116650642
#Sta/Elev= 30
       0 2585.86    29.9    2574    70.8 2553.47   133.7 2547.55   153.7 2542.89
   190.4 2530.39   204.5 2527.59   239.3 2525.64   280.1  2525.4   294.2 2522.95
   321.3 2524.65   393.4 2523.18   412.2 2524.52   431.1 2523.41  435.592521.547
   443.2 2519.01   459.5 2518.71   489.7 2518.87  506.862521.546   549.1 2523.97
   577.5 2522.86   601.1 2526.85   681.3 2526.02   695.5 2531.11   714.4 2534.16
     738 2546.11   788.6 2574.55   822.9 2587.15   837.1 2589.29   842.8 2591.45
#Mann= 5 ,-1,0
       0      .1       0     110     .05       0     220     .06       0
  435.59    .045       0  506.86      .1       0
Bank Sta=435.59,506.86
XS Rating Curve= 0 ,0
Exp/Cntr=0.3,0.1

Type RM Length L Ch R = 1 ,68897   ,542.4,542.4,542.4
XS GIS Cut Line= 2
2377345.28491845687311.4815064192378273.59557639687269.504963504
#Sta/Elev= 30
       0 2598.55    22.9 2587.99    30.9 2582.19    42.9 2579.12      71  2566.6
      95 2560.11     139 2531.78   163.1 2524.41   199.1 2523.18   215.1 2520.94
   243.1  2522.7   275.2 2519.59   531.4 2520.33   539.4 2518.94  546.072515.685
   551.5 2513.54   575.5 2513.18   607.5  2513.5  615.23 2515.72   627.5 2519.92
   671.5 2520.81   767.7 2518.95   783.7 2515.28   807.7 2516.25   815.7 2520.91
   843.9 2545.14   863.8 2559.57   879.8 2563.64   887.8 2570.15   929.3 2592.93
#Mann= 8 ,-1,0
       0      .1       0     170     .06       0     270     .05       0
     370     .06       0     460     .08       0  546.07    .045       0
  615.23     .08       0     660      .1       0
#XS Ineff= 2 , 0
          305.42 2524.85
Permanent Ineff=
       F       F
Bank Sta=546.07,615.23
XS Rating Curve= 0 ,0
Exp/Cntr=0.3,0.1

Type RM Length L Ch R = 1 ,68355   ,732,732,732
XS GIS Cut Line= 3
2377686.76786648687810.427114398 2377899.2124616687831.906646366
 2378358.4611266687757.977743771
#Sta/Elev= 30
       0 2545.88    37.6 2535.34    53.7 2532.52     126 2529.19   154.2 2521.04
   175.4 2521.16   226.7  2518.3   230.7 2516.82   236.5 2510.73   238.8 2508.58
   242.9 2508.22   271.2 2507.86   287.4 2507.98   303.1 2510.73     336 2513.04
   364.4 2511.56   380.6 2513.93   421.1 2515.35     454 2512.23   509.9 2512.79
   514.3 2514.79   522.4 2523.19   530.5 2529.25   550.8 2539.69   562.2 2550.35
   607.5 2578.34   619.7 2580.42   628.5 2587.16     648 2595.37   678.7 2611.43
#Mann= 5 ,-1,0
       0     .05       0     120     .06       0  223.53      .1       0
   236.5    .045       0   303.1      .1       0
Bank Sta=236.5,303.1
XS Rating Curve= 0 ,0
Exp/Cntr=0.3,0.1

Type RM Length L Ch R = 1 ,67623   ,454.8,454.8,454.8
XS GIS Cut Line= 2
2377453.74493531688539.1679251032378419.82126637688447.968925103
#Sta/Elev= 30
       0 2561.01     6.5 2555.81    34.6 2539.33    70.1 2526.17    86.8 2524.43
     127 2524.99   143.1 2523.45   211.4 2523.58   275.7 2521.56   359.9 2523.51
   444.4 2517.09   468.5 2519.48   476.5 2518.75   492.6 2521.52   536.8    2520
   551.1 2512.69   576.8 2511.88     589 2507.81   733.7 2509.17   773.9 2510.84
   777.9 2510.64  786.822506.167     806 2503.73   834.1 2503.25   854.2 2503.46
  861.662506.166   870.3 2515.49   894.4 2537.32   926.5 2563.88   970.4 2569.33
#Mann= 7 ,-1,0
       0      .1       0      60     .05       0     450      .1       0
     460     .06       0     550      .1       0  786.82    .045       0
  861.66      .1       0
Bank Sta=786.82,861.66
XS Rating Curve= 0 ,0
Exp/Cntr=0.3,0.1

Type RM Length L Ch R = 1 ,67168   ,509.9,509.9,509.9
XS GIS Cut Line= 3
2377851.36394211689164.3721140462377881.09943671689092.049880597
2378446.00628765688866.273548086
#Sta/Elev= 30
       0 2546.55    23.2 2543.55      64 2526.59   104.3 2522.24   167.7 2518.14
   240.9 2515.87   290.7 2509.04     323 2510.47   374.4 2507.53   402.8 2507.95
   421.8 2502.99   434.7 2501.56   443.4 2501.38   455.2 2502.69   464.9 2505.03
     495  2504.3   529.5 2507.17   533.8 2506.89  540.79 2503.29   546.7 2501.66
   589.8 2501.28   615.7 2501.57  622.17 2503.32   636.7 2515.41   654.4 2523.05
   661.4  2527.9     667  2532.9     676  2544.6   678.7 2546.68   686.6 2548.66
#Mann= 5 ,-1,0
       0     .05       0   208.2     .06       0   428.2      .1       0
  540.79    .045       0  622.17      .1       0
#XS Ineff= 2 , 0
        399.8679    2512
Permanent Ineff=
       F       F
Bank Sta=540.79,622.17
XS Rating Curve= 0 ,0
Exp/Cntr=0.3,0.1

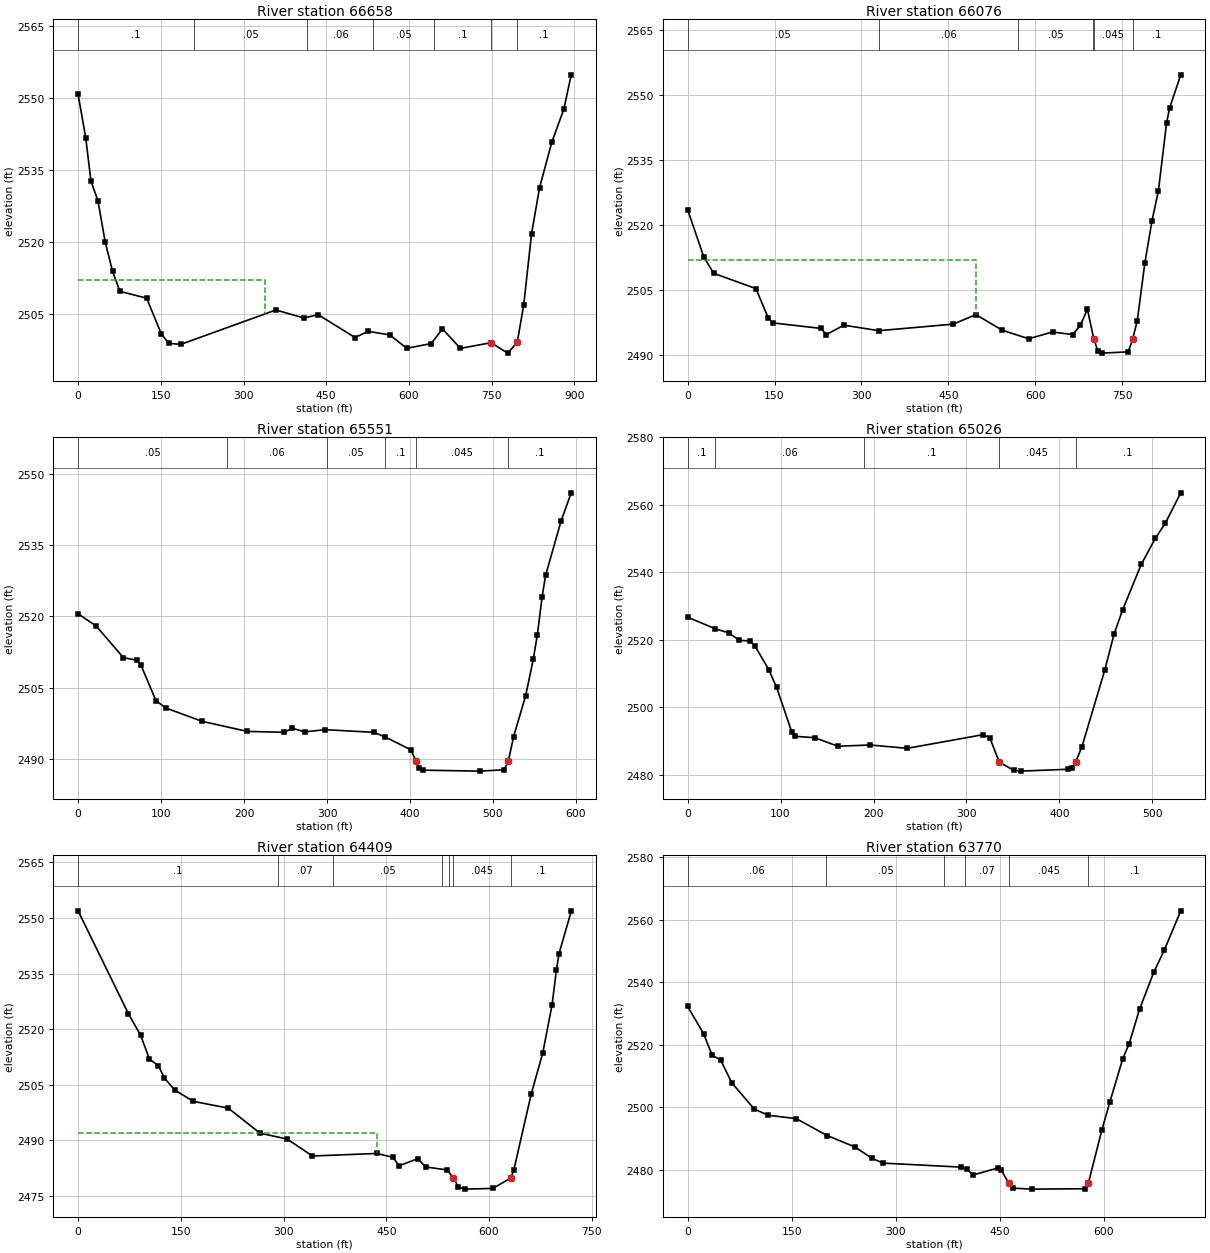
Type RM Length L Ch R = 1 ,66658   ,582.2,582.2,582.2
XS GIS Cut Line= 3
2378103.61354591689767.0976920082378443.44324447689607.091649903
 2378727.5070102689173.156975324
#Sta/Elev= 30
       0 2550.83    13.9 2541.72    23.3 2532.71      36 2528.58    49.3 2519.88
    62.5 2513.87    75.8 2509.65   124.4 2508.23   150.9 2500.78   164.2 2498.81
   186.3 2498.58   358.7 2505.76   409.3 2504.09   435.4 2504.78   502.2 2500.01
   526.1  2501.3   565.3 2500.56     596 2497.76   640.5 2498.75   660.7 2501.82
   693.4 2497.74   748.9 2498.93   779.1 2496.75   796.42498.988   808.2 2506.85
   822.4 2521.71   836.9 2531.33     859 2540.77   880.9 2547.71   894.3 2554.88
#Mann= 7 ,-1,0
       0      .1       0     210     .05       0  415.61     .06       0
  535.61     .05       0  645.61      .1       0   748.9    .045       0
   796.4      .1       0
#XS Ineff= 2 , 0
             339    2512
Permanent Ineff=
       F       F
Bank Sta=748.9,796.4
XS Rating Curve= 0 ,0
Exp/Cntr=0.3,0.1

Type RM Length L Ch R = 1 ,66076   ,525.3,525.3,525.3
XS GIS Cut Line= 2
2378658.27151386690226.3492529422379179.82261344689553.905192518
#Sta/Elev= 30
       0 2523.56    27.8 2512.66      45 2508.86   117.9 2505.34     139 2498.62
   146.7 2497.44   230.3 2496.16   239.4 2494.75   269.8 2496.91     330 2495.64
   458.3 2497.15   497.6 2499.34   543.1 2495.74   588.7 2493.78   629.7 2495.35
   664.6 2494.74   677.9 2496.91   689.9 2500.59  701.092493.629     708 2490.99
   714.5 2490.47   760.2 2490.76  767.912493.629     776 2497.97     789 2511.21
   801.3 2520.94   812.4 2527.87   826.6 2543.56   831.8 2546.99     851  2554.6
#Mann= 6 ,-1,0
       0     .05       0     330     .06       0     570     .05       0
     700      .1       0  701.09    .045       0  767.91      .1       0
#XS Ineff= 2 , 0
           497.6    2512
Permanent Ineff=
       F       F
Bank Sta=701.09,767.91
XS Rating Curve= 0 ,0
Exp/Cntr=0.3,0.1

Type RM Length L Ch R = 1 ,65551   ,524.7,524.7,524.7
XS GIS Cut Line= 2
 2379265.4528889690314.8567144582379612.01211199689832.083868681
#Sta/Elev= 30
       0 2520.57    21.8 2517.99    54.7 2511.33      71 2510.79    75.9 2509.71
    93.8  2502.3   105.5 2500.77   149.3 2497.95   203.9 2495.82   248.3 2495.64
   258.3 2496.49   272.9 2495.72   297.5 2496.19   356.6 2495.63     370 2494.65
   400.9 2491.97   407.3 2489.58   410.8 2488.17   415.7 2487.67   484.6 2487.47
   513.4 2487.76  518.52 2489.57   524.8 2494.71   539.2 2503.21   548.6    2511
   553.5 2516.18   559.2  2524.1   563.4 2528.64   582.2 2540.15   594.3    2546
#Mann= 6 ,-1,0
       0     .05       0     180     .06       0     300     .05       0
     370      .1       0   407.3    .045       0  518.52      .1       0
Bank Sta=407.3,518.52
XS Rating Curve= 0 ,0
Exp/Cntr=0.3,0.1

Type RM Length L Ch R = 1 ,65026   ,617,617,617
XS GIS Cut Line= 2
2379760.86599461690483.7309997122380073.58750848690055.249505597
#Sta/Elev= 30
       0 2526.73      30 2523.26    44.3 2522.08    55.7 2519.84    67.2  2519.7
    72.5 2518.18    87.2 2511.21    95.8  2505.9   112.1 2492.63   115.8  2491.4
   136.9    2491   161.6 2488.47   196.3 2488.84   236.3 2487.85   317.7 2491.89
     325 2491.05  335.272483.733   350.6 2481.38   358.4 2481.09   409.2 2481.64
   413.6 2482.16   417.32483.733   424.1 2488.24   448.8 2511.08   458.7 2521.67
     468 2528.93     488 2542.38   503.3 2550.18   513.8 2554.55   530.5 2563.59
#Mann= 5 ,-1,0
       0      .1       0      30     .06       0     190      .1       0
  335.27    .045       0   417.3      .1       0
Bank Sta=335.27,417.3
XS Rating Curve= 0 ,0
Exp/Cntr=0.3,0.1

Type RM Length L Ch R = 1 ,64409   ,639.3,639.3,639.3
XS GIS Cut Line= 3
2379920.80570978690958.1280445982380050.41570613690900.973528166
2380506.21894808690544.810989798
#Sta/Elev= 30
       0 2551.91    73.6 2524.12    91.3 2518.35   104.2 2511.94   117.3 2510.13
   126.1  2506.8   141.1 2503.57   168.4 2500.51   219.3 2498.69   265.7 2491.93
   305.2 2490.35   342.2 2485.78   436.3 2486.46   459.6 2485.42   468.8 2483.14
   496.1 2485.06   507.5 2482.82   538.9 2482.02  548.062479.866   555.1 2477.52
   565.2 2476.84   605.8 2477.03  632.012479.866   636.3 2482.02   661.7  2502.5
   678.5 2513.55   692.1  2526.5   698.4 2535.84   702.3 2540.39   720.1 2551.79
#Mann= 7 ,-1,0
       0      .1       0  291.65     .07       0  371.65     .05       0
  531.65     .07       0  541.65      .1       0  548.06    .045       0
  632.01      .1       0
#XS Ineff= 2 , 0
        436.4471    2492
Permanent Ineff=
       F       F
Bank Sta=548.06,632.01
XS Rating Curve= 0 ,0
Exp/Cntr=0.3,0.1

Type RM Length L Ch R = 1 ,63770   ,373.9,373.9,373.9
XS GIS Cut Line= 3
2380073.15741447691304.752243396 2380679.8247179691217.283669285
2380764.82988818691168.884707561
#Sta/Elev= 30
       0 2532.31    23.3 2523.46    35.4 2516.65    47.5 2515.17    63.7 2507.85
      96 2499.46   116.2 2497.45   156.6 2496.39   201.1 2490.97   241.5 2487.28
   265.7 2483.66   281.9 2482.14   394.4 2480.85   403.1  2480.1   411.2 2478.33
   447.6  2480.6   451.6 2480.07  463.042475.667   468.5 2474.13   496.1 2473.81
   572.9 2473.94  577.562475.666   597.1 2492.75   608.5 2501.63   627.2 2515.56
   636.4 2520.34   651.4 2531.41   671.9 2543.25     687 2550.29   710.8 2562.91
#Mann= 6 ,-1,0
       0     .06       0     200     .05       0     370     .06       0
     400     .07       0  463.04    .045       0  577.56      .1       0
Bank Sta=463.04,577.56
XS Rating Curve= 0 ,0
Exp/Cntr=0.3,0.1

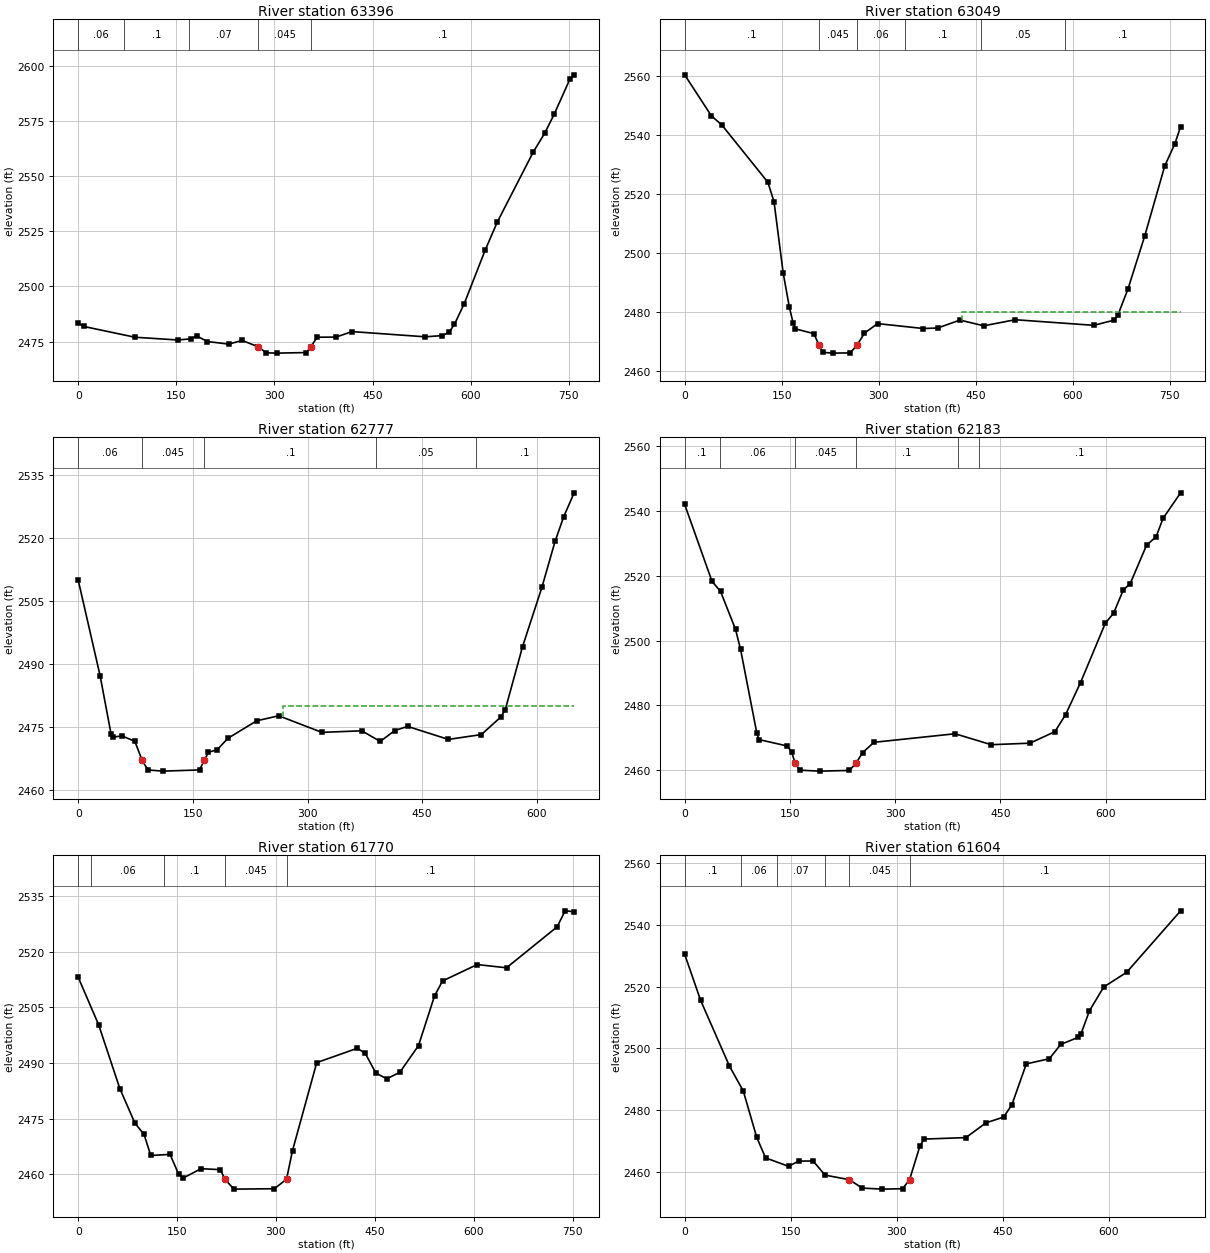
Type RM Length L Ch R = 1 ,63396   ,346.8,346.8,346.8
XS GIS Cut Line= 3
2380295.54280083691533.6052948722380727.06156355  691629.3814105
2381002.81257778691474.666146794
#Sta/Elev= 30
       0 2483.37     8.8 2481.83    86.7 2476.96   152.2 2475.72   172.7 2476.24
   180.9  2477.6   197.3 2475.02   230.1 2473.85   250.6 2475.51   275.2 2472.63
   275.2 2472.61   287.5 2469.89   303.9 2469.76   348.8 2470.02   355.6 2472.64
   365.3 2476.97     394 2477.02   418.6 2479.52   530.4 2477.16   556.9 2477.71
   567.1 2479.28   575.2 2482.83   590.1 2492.14     622 2516.31   640.5 2529.04
   695.7  2560.9   713.3 2569.49   727.7 2578.03   751.5  2593.8   758.2 2595.88
#Mann= 5 ,-1,0
       0     .06       0      70      .1       0     170     .07       0
   275.2    .045       0   355.6      .1       0
Bank Sta=275.2,355.6
XS Rating Curve= 0 ,0
Exp/Cntr(USF)=0,0
Exp/Cntr=0.3,0.1

Type RM Length L Ch R = 1 ,63049   ,272.3,272.3,272.3
XS GIS Cut Line= 4
2380374.93046111692055.007015446 2380738.5724389691828.369910817
2380921.28322128691668.355142256 2380995.0893879691607.556042857
#Sta/Elev= 30
       0 2560.53    41.3 2546.62    57.4 2543.55   128.7 2524.12   138.2 2517.49
   152.3 2493.44   161.7 2482.02   167.7 2476.41   171.1 2474.45   199.7 2472.83
   207.6 2469.04   213.6 2466.49   228.7 2466.22     256  2466.3  266.87 2469.01
   278.1 2473.02   298.4 2476.22   369.1 2474.56   391.3 2474.73   425.7 2477.42
   462.5 2475.48   511.3 2477.54   632.7 2475.64   664.6 2477.42     670 2479.13
   685.5  2487.9   711.4 2505.86   742.5 2529.68   758.1 2537.16     767 2542.99
#Mann= 6 ,-1,0
       0      .1       0   207.6    .045       0  266.87     .06       0
     340      .1       0  458.49     .05       0  588.49      .1       0
#XS Ineff= 2 , 0
                         428.899            2480
Permanent Ineff=
       F       F
Bank Sta=207.6,266.87
XS Rating Curve= 0 ,0
Exp/Cntr=0.3,0.1

Type RM Length L Ch R = 1 ,62777   ,594.3,594.3,594.3
XS GIS Cut Line= 2
2380674.48865064692228.0578142722381104.15133114 691741.92465547
#Sta/Elev= 30
       0 2509.86    28.7 2487.04    42.9 2473.29    45.7 2472.47    57.2 2472.77
    74.1 2471.48   83.58 2466.97    91.1 2464.66   110.6 2464.38   158.7 2464.66
  164.942466.968   170.4 2468.86   181.8 2469.48   195.9  2472.2   233.4 2476.36
   262.3 2477.56   318.8 2473.61     371 2473.98   395.1 2471.45   414.1 2474.04
   430.9 2475.03   484.3 2471.93   527.5 2473.09     553  2477.3   558.7 2479.03
   581.3 2494.03   606.6 2508.14   623.8 2519.08   635.2 2524.99   648.8 2530.65
#Mann= 5 ,-1,0
       0     .06       0   83.58    .045       0  164.94      .1       0
     390     .05       0     520      .1       0
#XS Ineff= 1 ,-1
 268.102 648.795    2480
Permanent Ineff=
       F
Bank Sta=83.58,164.94
XS Rating Curve= 0 ,0
Exp/Cntr=0.3,0.1

Type RM Length L Ch R = 1 ,62183   ,412.4,412.4,412.4
XS GIS Cut Line= 2
2381125.95448253692660.6360719612381498.64921618692059.965667959
#Sta/Elev= 30
       0 2542.06      39 2518.27    51.1  2515.2    72.5 2503.43    79.7 2497.24
   102.8 2471.44   105.8  2469.4   146.5 2467.39   152.3  2465.6  157.56 2462.07
   164.1 2459.93   192.4 2459.64   234.7 2459.85  244.12 2462.05   253.6 2465.36
   269.8 2468.55   385.4 2471.19     437 2467.81   492.2 2468.28   527.7 2471.84
   542.9 2477.09   564.2 2486.99   599.6 2505.37   611.3 2508.44   625.4 2515.73
   634.9 2517.52   658.4 2529.49   671.9 2532.06   681.9 2537.79   706.9 2545.66
#Mann= 6 ,-1,0
       0      .1       0      50     .06       0  157.56    .045       0
  244.12      .1       0     390     .05       0     420      .1       0
Bank Sta=157.56,244.12
XS Rating Curve= 0 ,0
Exp/Cntr=0.3,0.1

Type RM Length L Ch R = 1 ,61770   ,166,166,166
XS GIS Cut Line= 3
2381337.22003089692860.1279934972381652.10932462692681.888770628
 2381709.5419631692295.703787745
#Sta/Elev= 30
       0 2513.07      31 2500.27    63.1 2483.09    86.1 2473.71    99.9 2470.72
     110 2465.04   139.3 2465.32   152.2 2460.04   159.7    2459   186.3 2461.47
   215.7 2461.21   222.4 2458.65   236.2 2455.96   297.6 2456.07  316.01 2458.64
   325.1 2466.37   361.8 2490.07   423.2 2493.93   435.3 2492.61   451.5 2487.25
   468.1 2485.71   487.9 2487.46   516.2 2494.67   540.5 2508.04   552.6 2512.09
   605.2 2516.51   649.7 2515.64   726.5 2526.69   738.6    2531   752.3 2530.77
#Mann= 5 ,-1,0
       0      .1       0      20     .06       0     130      .1       0
   222.4    .045       0  316.01      .1       0
Bank Sta=222.4,316.01
XS Rating Curve= 0 ,0
Exp/Cntr(USF)=0,0
Exp/Cntr=0.3,0.1

Type RM Length L Ch R = 1 ,61604   ,351.6,351.6,351.6
XS GIS Cut Line= 4
2381390.77898477693006.0452314122381512.71979935692905.374898625
2381872.26926426  692835.74708512382047.60861571692863.675510899
#Sta/Elev= 30
       0 2530.45    22.6 2515.52    63.4 2494.26      83 2486.18   101.9 2471.27
   114.5 2464.58     147 2461.85   161.2 2463.53   181.7 2463.57   198.8    2459
   233.12457.516   251.3 2454.81   279.8 2454.47   308.3  2454.6  318.292457.514
   332.8 2468.34   338.7 2470.66     398 2471.14   426.5 2475.93   451.4 2477.78
   463.1 2481.76   483.5 2494.99   516.1 2496.66   532.2 2501.27   556.7 2503.57
   560.7 2504.58   572.9 2512.18   593.1 2519.87   625.5 2524.61   701.9 2544.51
#Mann= 6 ,-1,0
       0      .1       0      80     .06       0     130     .07       0
  198.13      .1       0   233.1    .045       0  318.29      .1       0
Bank Sta=233.1,318.29
XS Rating Curve= 0 ,0
Exp/Cntr=0.3,0.1

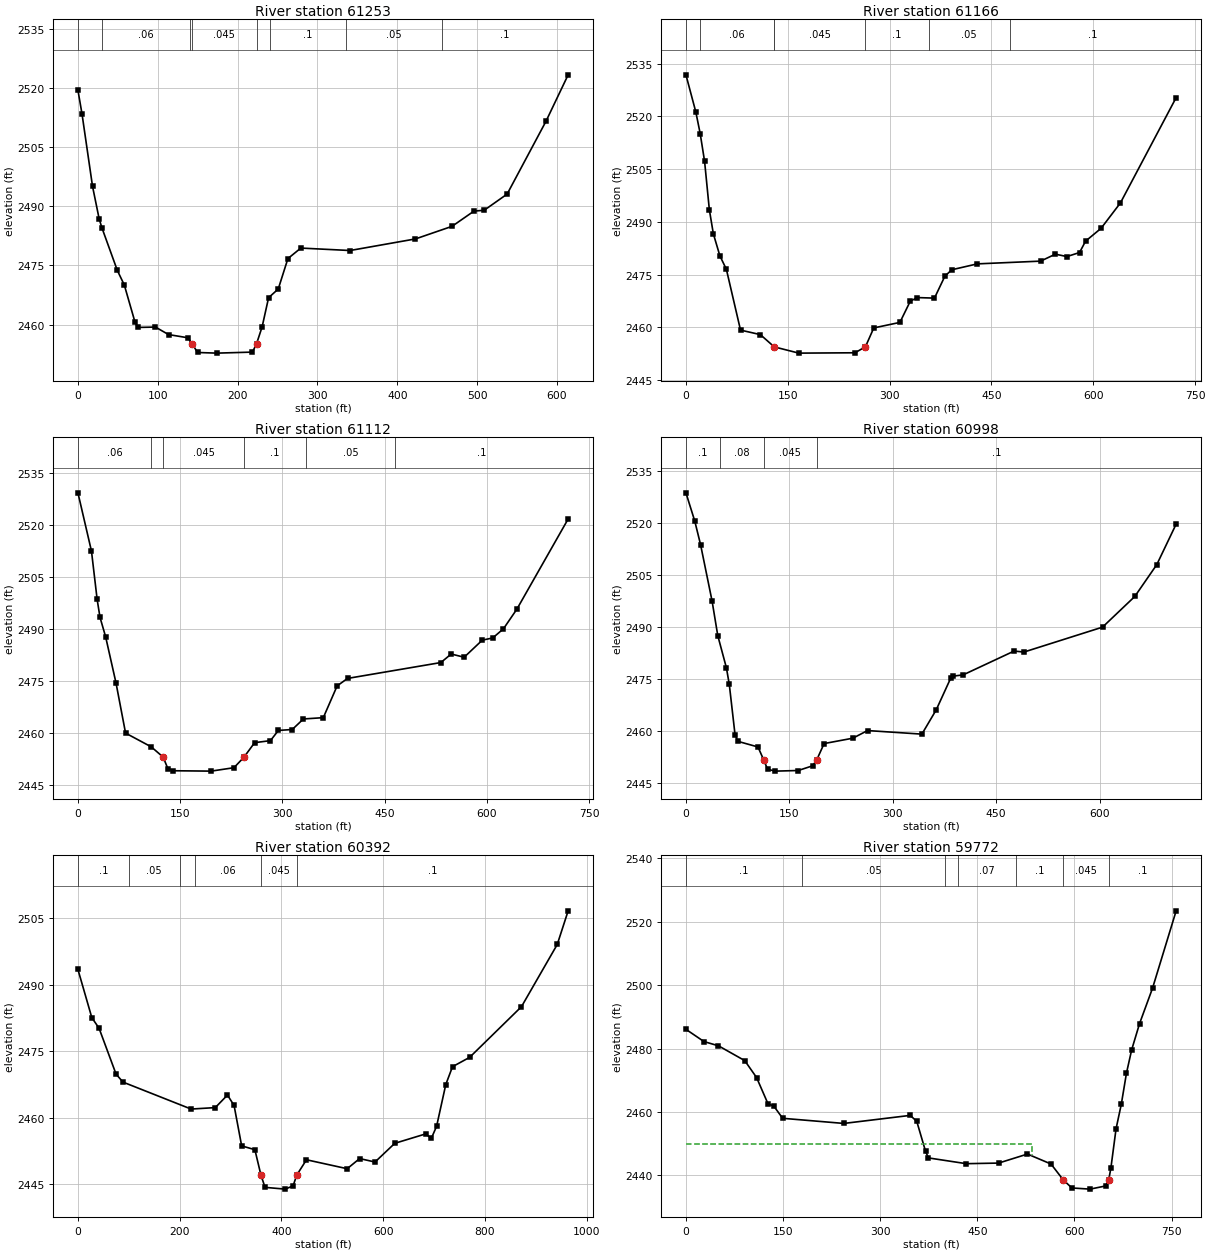
Type RM Length L Ch R = 1 ,61253   ,86.7,86.7,86.7
XS GIS Cut Line= 4
2381519.57194533693280.5249451082381601.45934227693241.989699489
2381843.91026262693206.6657243392382070.30483063693044.496565694
#Sta/Elev= 30
       0 2519.38     5.1 2513.38    18.3 2495.01    26.6 2486.78      30 2484.55
    49.3 2473.75    58.1 2470.03    71.4 2460.68    75.1 2459.29    97.1 2459.38
   113.5 2457.48   137.7 2456.67     143 2455.19   149.8 2452.94   174.1 2452.78
   218.6 2453.04  223.782455.188   230.7 2459.44   238.8 2466.82   250.9 2469.02
     263 2476.73   279.2 2479.39   340.8 2478.77   422.8 2481.71   468.6  2484.9
   496.1 2488.76   508.8 2488.96   537.6 2493.07   586.2 2511.49     614 2523.27
#Mann= 8 ,-1,0
       0      .1       0      30     .06       0   140.5     .07       0
     143    .045       0  223.78     .07       0   240.5      .1       0
  335.51     .05       0  455.51      .1       0
Bank Sta=143,223.78
XS Rating Curve= 0 ,0
Exp/Cntr(USF)=0,0
Exp/Cntr=0.3,0.1

Type RM Length L Ch R = 1 ,61166   ,53.4,53.4,53.4
XS GIS Cut Line= 4
2381527.04398067693326.1720558172381661.57290976693286.484594697
2381798.17929373693364.1794256012382132.10285396693101.743167076
#Sta/Elev= 30
       0 2531.84    14.6 2521.24      21 2515.14    27.5  2507.2    34.5 2493.47
    40.4 2486.61      50 2480.36    59.6  2476.5    80.4 2459.22   109.6 2457.94
   130.12454.446   166.3 2452.67   249.1 2452.77   264.4 2454.47   276.7 2459.84
   315.2 2461.41   330.5 2467.46   341.1 2468.47   366.1 2468.32   381.4 2474.54
   391.5 2476.38   429.2 2478.06   522.4 2478.84   544.2 2480.82   561.2 2480.14
   579.8 2481.29   588.7 2484.53   611.5 2488.17     640  2495.4   722.1 2525.36
#Mann= 7 ,-1,0
       0      .1       0      20     .06       0     130     .07       0
   130.1    .045       0   264.4      .1       0  357.42     .05       0
  477.42      .1       0
Bank Sta=130.1,264.4
XS Rating Curve= 0 ,0
Exp/Cntr=0.3,0.1

Type RM Length L Ch R = 1 ,61112   ,114,114,114
XS GIS Cut Line= 4
2381545.06703992693355.3655811482381648.33717084693325.150483113
 2381784.9435548693402.8453140172382143.49525905 693123.35880194
#Sta/Elev= 30
       0 2529.26    19.9 2512.43    28.2 2498.51    32.4 2493.36    40.7 2487.71
    55.9 2474.42    69.9 2459.98   107.6 2456.01   125.1 2453.05   131.9 2449.76
     140 2449.12   195.5 2449.01     229    2450  243.62 2453.02   259.3 2457.22
   282.5  2457.8   294.2 2460.75   314.5 2461.01   330.9 2464.05   360.1 2464.43
   380.4 2473.59   395.6 2475.74   532.6 2480.32   547.8 2482.78   566.8 2481.85
   593.4 2486.78   608.7 2487.41   624.5 2490.06   644.2 2495.73   719.4 2521.72
#Mann= 6 ,-1,0
       0     .06       0   107.6     .08       0   125.1    .045       0
  243.62      .1       0  334.75     .05       0  464.75      .1       0
Bank Sta=125.1,243.62
XS Rating Curve= 0 ,0
Exp/Cntr=0.3,0.1

Type RM Length L Ch R = 1 ,60998   ,606.3,606.3,606.3
XS GIS Cut Line= 3
2381599.85370704693519.7645949892381988.41743369693405.764493368
2382190.72747319693176.158654891
#Sta/Elev= 30
       0 2528.64    12.8 2520.51    21.2 2513.74    37.9 2497.49    46.2 2487.49
    58.7 2478.22    62.9 2473.42    71.2 2458.99    75.4 2457.03   104.5 2455.41
  112.722451.719   118.4 2448.99   129.6 2448.45   162.9 2448.63   183.8 2449.99
  189.772451.718   200.4 2456.39   242.1 2457.94   263.4 2460.14   342.2 2459.11
     363 2466.11   383.8 2475.15     388 2475.83     402 2476.18     476 2483.05
   490.2 2482.76   604.2 2489.94     651 2498.78   682.9 2507.96710.9616 2519.63
#Mann= 4 ,-1,0
       0      .1       0      50     .08       0  112.72    .045       0
  189.77      .1       0
Bank Sta=112.72,189.77
XS Rating Curve= 0 ,0
Exp/Cntr(USF)=0,0
Exp/Cntr=0.3,0.1

Type RM Length L Ch R = 1 ,60392   ,620,620,620
XS GIS Cut Line= 4
2381767.33932099694234.8396222752382112.54832099693938.434622275
2382347.47391969693731.3189490892382429.12459391693553.928923559
#Sta/Elev= 30
       0 2493.41    27.3 2482.55    41.5 2480.17    74.9 2469.83    88.5 2468.02
   222.5 2461.94     270 2462.27   293.9  2465.1   306.9 2462.75   321.8 2453.64
   347.8 2452.78   359.6  2447.1   367.7 2444.29   407.4 2443.89   422.9 2444.63
   430.1 2447.06   449.2 2450.51   529.2 2448.49   553.7 2450.78   583.9    2450
   622.8 2454.22   683.8 2456.35   694.5 2455.32   704.9 2458.04     723 2467.47
   736.2 2471.49   769.9  2473.6   871.8 2485.03   942.1 2499.05   963.5 2506.63
#Mann= 6 ,-1,0
       0      .1       0     100     .05       0     200      .1       0
     230     .06       0   359.6    .045       0   430.1      .1       0
Bank Sta=359.6,430.1
XS Rating Curve= 0 ,0
Exp/Cntr=0.3,0.1

Type RM Length L Ch R = 1 ,59772   ,581.9,581.9,581.9
XS GIS Cut Line= 3
2381983.48853553 694595.279043432382452.21778509694352.971848351
2382680.48786235694329.805392953
#Sta/Elev= 30
       0 2486.09    27.8 2482.23    50.3 2480.88    90.8 2476.22   109.1 2470.88
   126.7 2462.61   135.9 2461.81   149.4 2458.01   243.9 2456.39   346.4 2458.93
   356.5 2457.05   370.1 2447.58   374.5 2445.51     433 2443.69   482.9 2443.88
   527.5 2446.73   563.8 2443.59   582.8 2438.57     596 2436.03   624.1 2435.66
   648.2 2436.66  652.94 2438.55   656.3 2442.31   664.3  2454.7   672.4 2462.46
   680.4  2472.3   688.4 2479.62   700.5 2487.85   720.6 2499.05   757.1 2523.48
#Mann= 7 ,-1,0
       0      .1       0     180     .05       0     400     .06       0
     420     .07       0     510      .1       0   582.8    .045       0
  652.94      .1       0
#XS Ineff= 2 , 0
           534.5    2450
Permanent Ineff=
       F       F
Bank Sta=582.8,652.94
XS Rating Curve= 0 ,0
Exp/Cntr=0.3,0.1

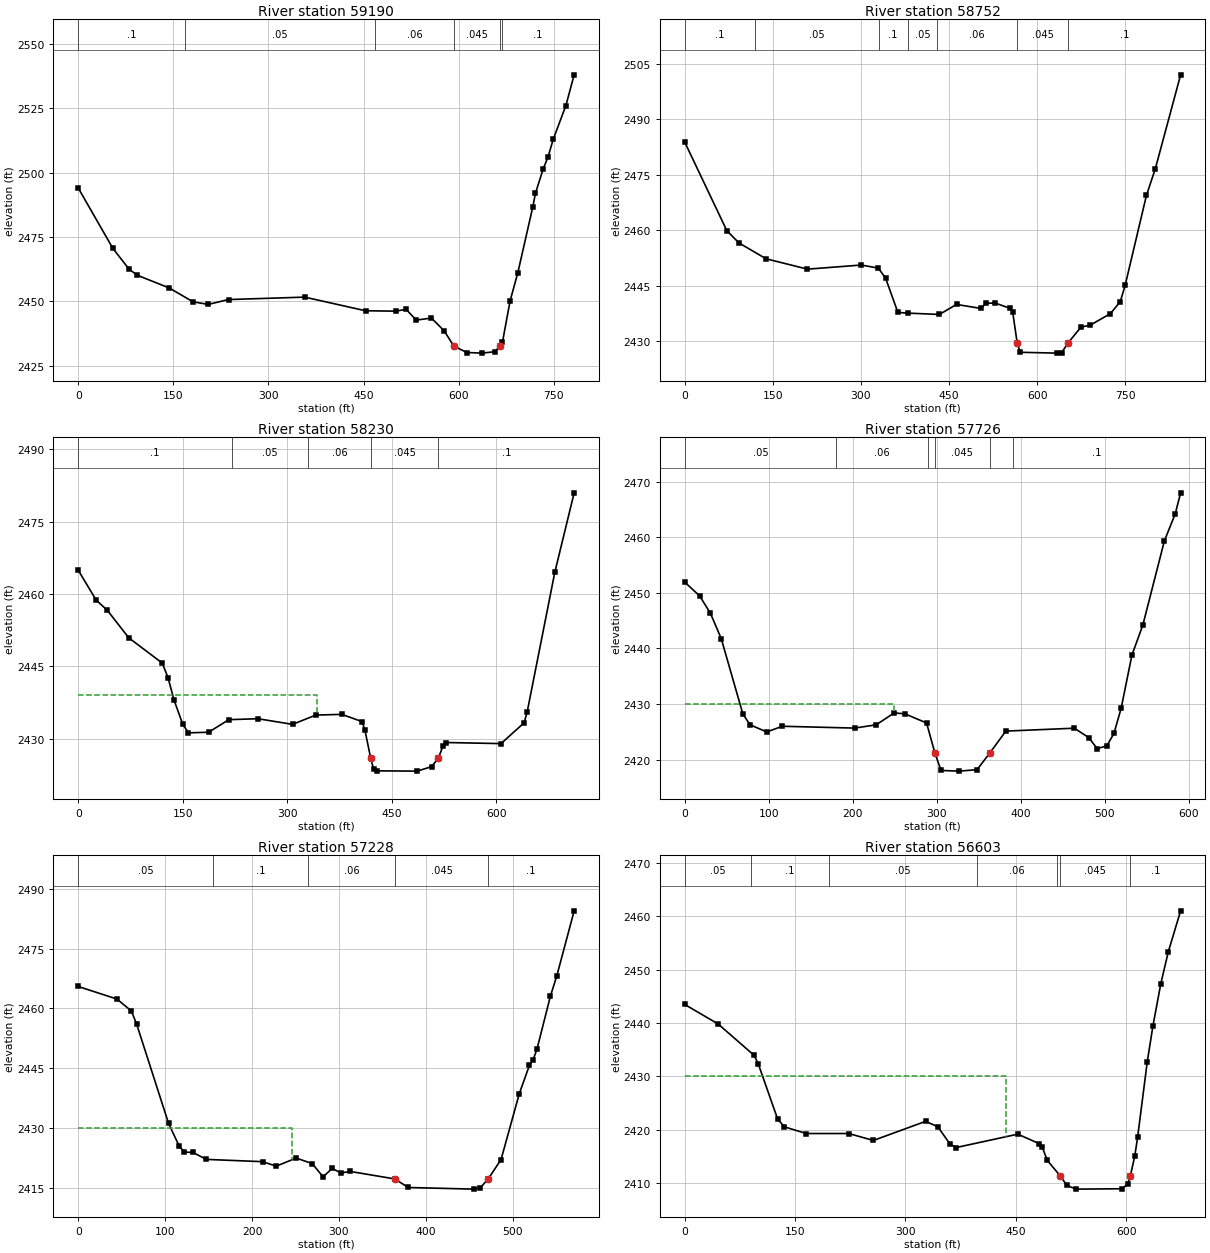
Type RM Length L Ch R = 1 ,59190   ,438.5,438.5,438.5
XS GIS Cut Line= 3
2381976.84146939694858.5821549712382135.00971603694914.703253209
2382749.09907853694922.368967154
#Sta/Elev= 30
       0 2494.07    54.5 2470.67    79.9 2462.63    92.7 2460.23   143.6 2455.24
     181 2449.88     205 2448.86     237 2450.75   357.1 2451.69     453  2446.4
     501 2446.24     517 2446.97     533 2442.77     557 2443.56     577  2438.6
  592.472432.629     613 2430.19   636.4 2429.95   656.7 2430.49     665 2432.63
     669 2434.26     681 2450.24   693.1 2461.08   716.7  2486.6     721 2492.03
     733 2501.33     741 2506.24     749 2512.96     769 2526.08     782 2537.99
#Mann= 6 ,-1,0
       0      .1       0  167.83     .05       0  467.83     .06       0
  592.47    .045       0     665     .06       0  667.83      .1       0
Bank Sta=592.47,665
XS Rating Curve= 0 ,0
Exp/Cntr=0.3,0.1

Type RM Length L Ch R = 1 ,58752   ,521.7,521.7,521.7
XS GIS Cut Line= 3
 2381923.2145109695184.3535544932382649.02129919695391.598700806
2382738.30053926695396.213240071
#Sta/Elev= 30
       0 2483.89    71.7  2459.9    92.5 2456.55   138.3 2452.29     209 2449.46
   300.5 2450.58   329.6 2449.75   342.1    2447   362.9 2437.75     380 2437.56
   433.6  2437.2   462.7 2439.91   504.3 2438.83   512.7 2440.25   528.9 2440.26
   554.3 2438.84   558.4 2437.79  566.042429.447   571.2 2426.96   633.3 2426.73
   641.6 2426.81  652.382429.443   674.5 2433.76   690.7 2434.32   724.8 2437.44
   741.5 2440.69   749.8 2445.09     786 2469.42   801.2 2476.69   844.2 2502.07
#Mann= 7 ,-1,0
       0      .1       0     120     .05       0     330      .1       0
     380     .05       0     430     .06       0  566.04    .045       0
  652.38      .1       0
Bank Sta=566.04,652.38
XS Rating Curve= 0 ,0
Exp/Cntr=0.3,0.1

Type RM Length L Ch R = 1 ,58230   ,504.1,504.1,504.1
XS GIS Cut Line= 3
 2381924.0252335 695729.664995522382536.89042193695900.798654977
 2382611.9750851695901.801532696
#Sta/Elev= 30
       0 2464.94    25.7 2458.74    41.7 2456.63    72.6 2450.91   120.6 2445.68
   128.9 2442.63   137.2 2438.14   149.7  2433.1     158 2431.23     187 2431.36
   216.1 2433.96   257.6 2434.16   307.5 2432.99   340.7 2434.91   378.1 2435.06
   407.2 2433.56   411.3 2431.78   419.6 2425.93   423.8  2423.7   427.9 2423.36
   486.1  2423.3   506.8 2424.22  516.62 2425.96   523.4 2428.59   527.6 2429.23
   606.5    2429   639.6 2433.31   643.9 2435.48   683.6 2464.46   711.4 2480.96
#Mann= 5 ,-1,0
       0      .1       0     220     .05       0     330     .06       0
   419.6    .045       0  516.62      .1       0
#XS Ineff= 2 , 0
           343.1 2439.16
Permanent Ineff=
       F       F
Bank Sta=419.6,516.62
XS Rating Curve= 0 ,0
Exp/Cntr=0.3,0.1

Type RM Length L Ch R = 1 ,57726   ,497.6,497.6,497.6
XS GIS Cut Line= 2
 2382067.5475109696466.741960584 2382618.2211484 696254.83616811
#Sta/Elev= 30
       0 2451.95    17.8 2449.47    30.7 2446.31    43.5 2441.77    69.2 2428.21
    77.8 2426.25    97.6 2424.97   116.2 2425.99   202.1 2425.66   227.8 2426.25
   249.3  2428.4   262.1 2428.22   287.8 2426.58  297.722421.149     305 2418.03
   326.4 2417.91   347.8 2418.17  362.852421.147   382.1 2425.12   463.6 2425.64
   480.7 2423.95   490.7 2421.97   502.1 2422.45   510.7  2424.7   519.3 2429.26
   532.1 2438.83     545 2444.18   570.7 2459.38   583.6 2464.25     590 2468.03
#Mann= 6 ,-1,0
       0     .05       0     180     .06       0     290     .05       0
  297.72    .045       0  362.85     .05       0     390      .1       0
#XS Ineff= 2 , 0
           249.3    2430
Permanent Ineff=
       F       F
Bank Sta=297.72,362.85
XS Rating Curve= 0 ,0
Exp/Cntr=0.3,0.1

Type RM Length L Ch R = 1 ,57228   ,625.6,625.6,625.6
XS GIS Cut Line= 4
2382298.98213317696995.5242597792382414.39968767696948.671203046
2382699.87671455696715.7301181022382771.94964616696687.079399522
#Sta/Elev= 30
       0 2465.53    44.5 2462.37    61.1 2459.39    67.2  2456.1     104 2431.14
   116.3 2425.41   122.2 2423.98     132 2423.87   147.5 2422.13   212.3 2421.56
   227.8 2420.43   250.8 2422.47   269.3 2421.07   281.7 2417.75   292.1 2419.85
   302.4 2418.74   313.1  2419.1   364.2 2417.23   379.8 2415.08   455.2 2414.67
   462.4 2414.96   471.7 2417.22   486.5  2422.1   507.5 2438.64   519.2 2445.77
   523.5  2447.2   527.8 2449.76   543.2 2463.04   550.7 2468.23   570.6 2484.51
#Mann= 5 ,-1,0
       0     .05       0  154.56      .1       0  264.56     .06       0
   364.2    .045       0   471.7      .1       0
#XS Ineff= 2 , 0
           245.6    2430
Permanent Ineff=
       F       F
Bank Sta=364.2,471.7
XS Rating Curve= 0 ,0
Exp/Cntr=0.3,0.1

Type RM Length L Ch R = 1 ,56603   ,551.1,551.1,551.1
XS GIS Cut Line= 3
2382358.42228661697390.8829757082382477.42245029697457.978504787
2382992.12106241697303.567997151
#Sta/Elev= 30
       0 2443.47    45.4 2439.81    94.3 2433.94    99.9 2432.37   126.3    2422
   135.4 2420.54   165.2 2419.28     223 2419.28   256.4 2417.98   327.4 2421.56
   344.1 2420.55   360.8 2417.25   369.2 2416.66   452.7 2419.16   481.9 2417.38
   486.1 2416.68   492.8 2414.25  510.242411.361   519.5 2409.54     532 2408.86
   594.7 2408.93   602.1 2409.86  605.722411.359   611.7 2415.06   615.6 2418.63
   628.7 2432.76   636.4 2439.46     647 2447.31   657.3 2453.36     674 2461.01
#Mann= 7 ,-1,0
       0     .05       0      90      .1       0  196.61     .05       0
  396.61     .06       0  506.61      .1       0  510.24    .045       0
  605.72      .1       0
#XS Ineff= 2 , 0
        437.2264    2430
Permanent Ineff=
       F       F
Bank Sta=510.24,605.72
XS Rating Curve= 0 ,0
Exp/Cntr=0.3,0.1