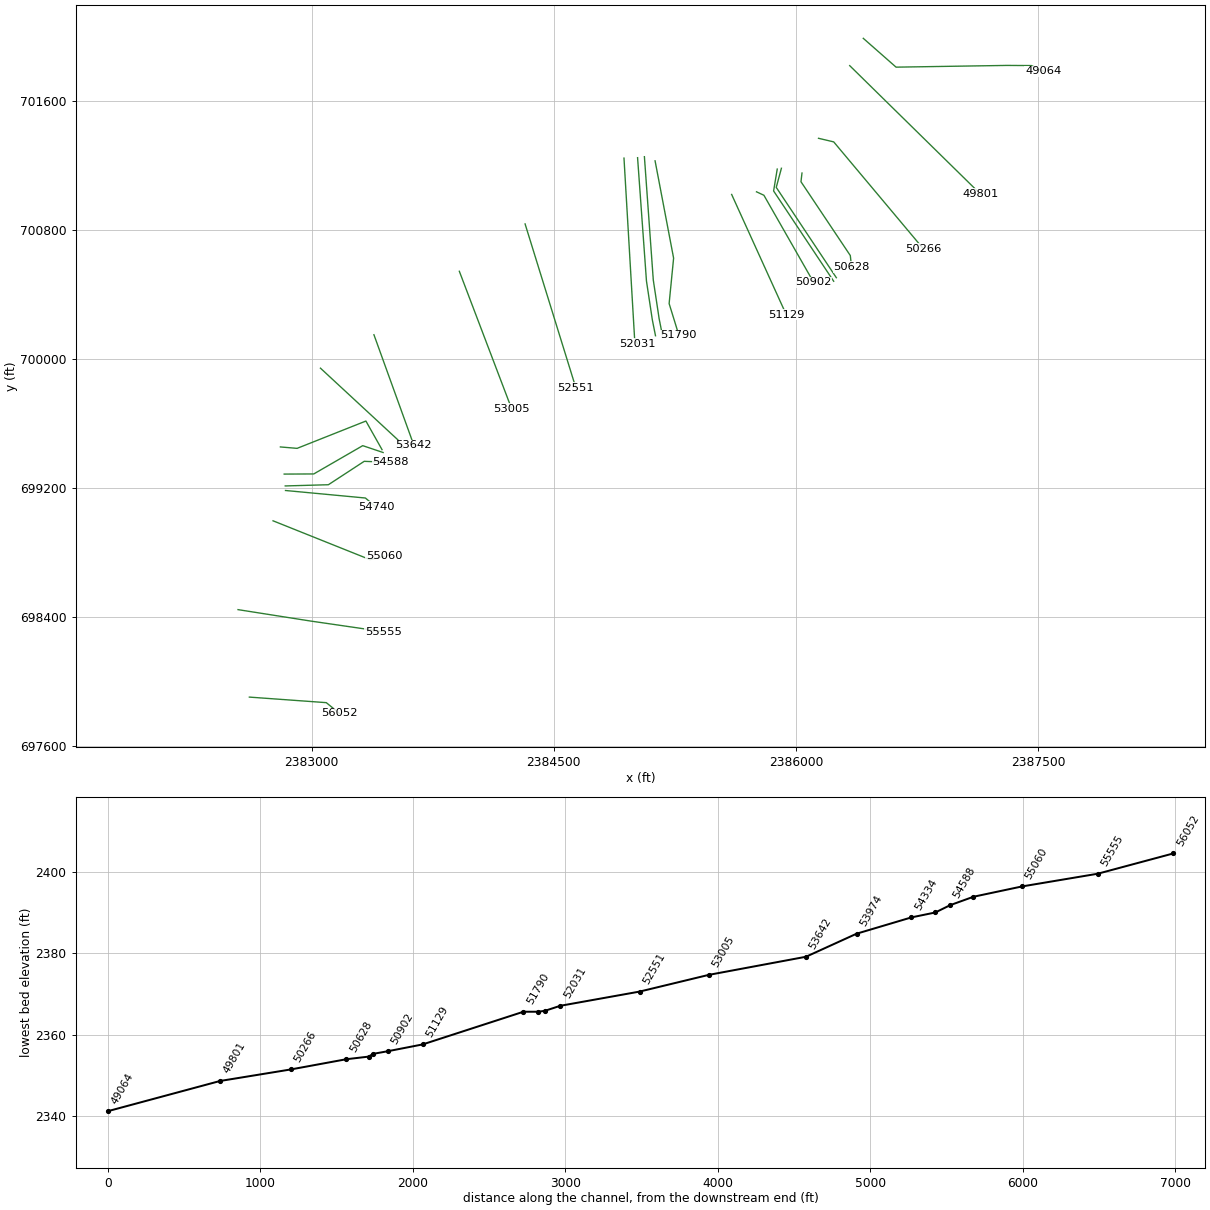
HEC-RAS study DRKFK_2.prj: DRKFK_2

--- DRKFK_2.g01 (geometry) --- (continued)

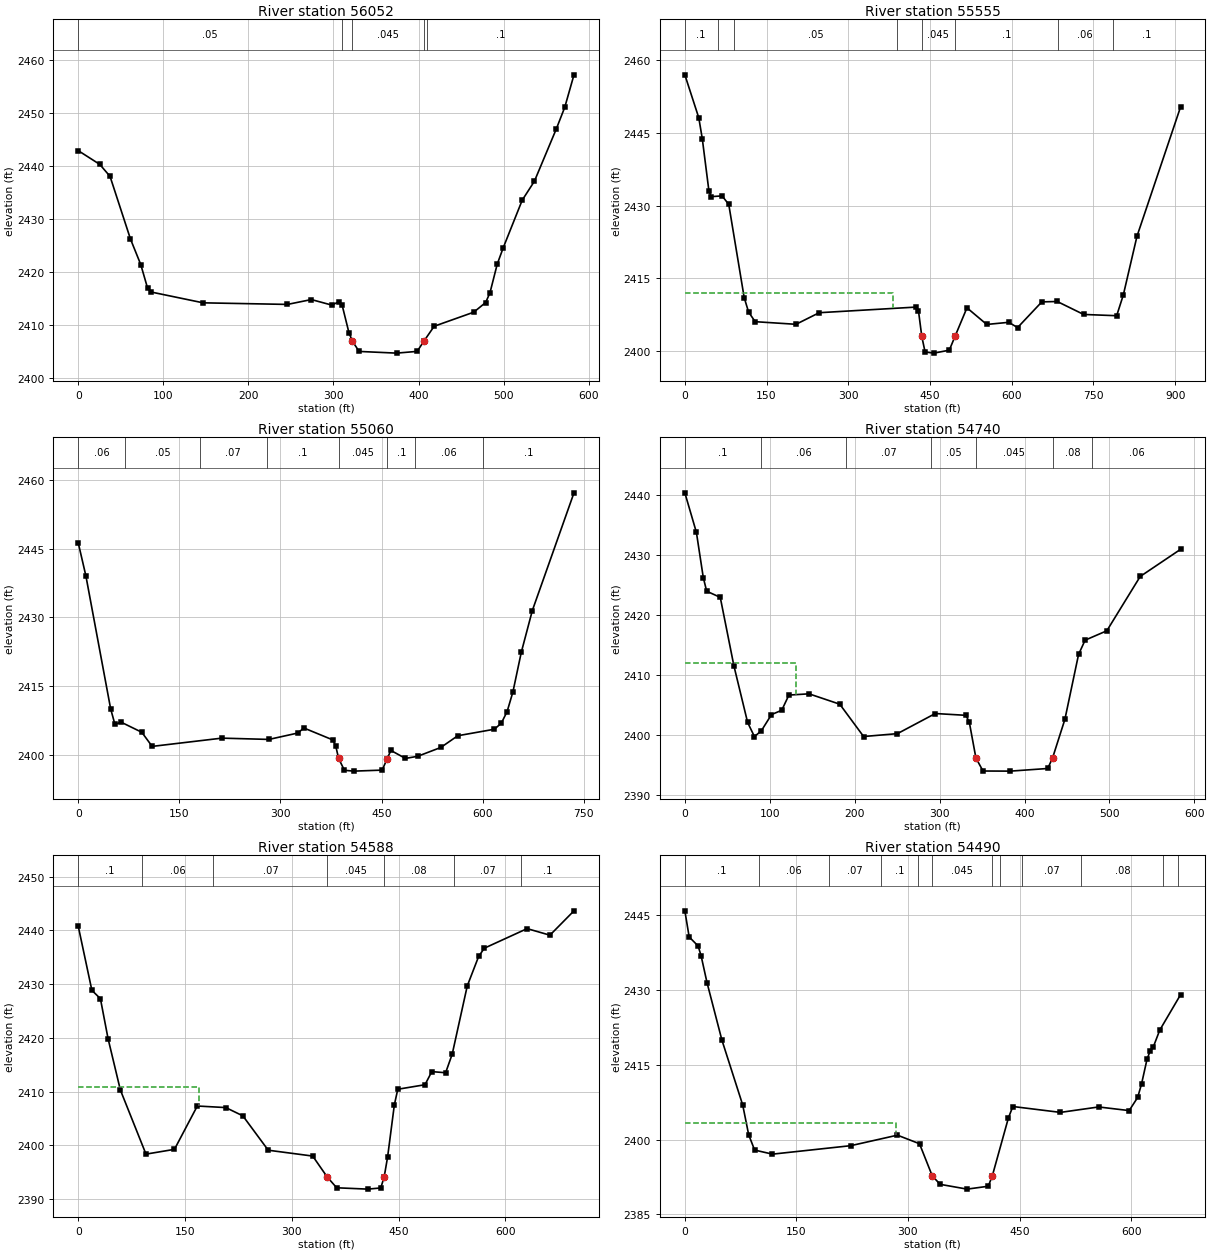
Type RM Length L Ch R = 1 ,56052   ,497,497,497
XS GIS Cut Line= 3
2382614.91366741697904.9246973582383091.21156069697870.558062124
2383172.52318637697804.078722208
#Sta/Elev= 30
       0 2442.91    25.3 2440.31    37.4 2438.04    61.4  2426.2    73.5 2421.37
    81.5 2416.92    85.5 2416.18   146.8 2414.13   245.9 2413.83     274 2414.75
     298  2413.7   306.1 2414.32   310.1 2413.72   318.1 2408.52  322.072406.912
   330.1 2404.94   374.2 2404.62   398.3 2404.95  406.372406.911   418.3  2409.7
   464.8 2412.36   478.8 2414.19   483.9 2416.04   492.4 2421.44   499.4 2424.52
   521.8 2433.55   536.1 2437.12   561.9 2447.04   571.8 2451.12   582.6 2457.24
#Mann= 5 ,-1,0
       0     .05       0     310     .06       0  322.07    .045       0
  406.37     .06       0     410      .1       0
Bank Sta=322.07,406.37
XS Rating Curve= 0 ,0
Exp/Cntr=0.3,0.1

Type RM Length L Ch R = 1 ,55555   ,495,495,495
XS GIS Cut Line= 3
2382544.60228289698446.8536030612382994.06928289698376.151603061
2383444.35128289698310.554603061
#Sta/Elev= 30
       0 2456.96    25.6 2448.09      32  2443.8    44.1 2433.09    48.2 2431.86
    68.4 2432.01    80.6 2430.25   108.9 2411.06     117 2408.07   129.1 2406.09
     204 2405.55   246.6 2407.94   424.7  2409.1   428.8 2408.34   434.9 2403.05
   440.9 2399.85   457.1 2399.61   485.4 2400.22  495.852403.052   517.8 2408.95
   554.1 2405.52   594.6 2405.96   610.7 2404.87   655.2 2410.17   683.5 2410.25
     732 2407.58   792.6 2407.32   804.8 2411.59   829.9  2423.7     910 2450.38
#Mann= 8 ,-1,0
       0      .1       0      60     .06       0      90     .05       0
     390     .06       0   434.9    .045       0  495.85      .1       0
  684.99     .06       0  784.99      .1       0
#XS Ineff= 2 , 0
        381.8464    2412
Permanent Ineff=
       F       F
Bank Sta=434.9,495.85
XS Rating Curve= 0 ,0
Exp/Cntr=0.3,0.1

Type RM Length L Ch R = 1 ,55060   ,319.6,319.6,319.6
XS GIS Cut Line= 3
 2382761.5911647698997.1961819162383361.92867569698756.708231615
2383448.46391176 698776.33218924
#Sta/Elev= 30
       0 2446.27    11.4 2439.04    48.1 2410.08    54.5 2406.66    63.5 2407.17
    94.3 2404.96   109.7 2401.88   213.1 2403.68   282.9  2403.4     326  2404.8
   334.6  2405.9   377.7 2403.29     382 2401.97  386.282399.242   394.9 2396.67
   408.8 2396.49   450.9 2396.71  458.41 2399.24   463.8    2401   485.4 2399.26
   503.5 2399.72   537.9 2401.65     563  2404.2   617.3 2405.62   627.6 2406.94
   636.2 2409.46   644.8 2413.74   657.2 2422.36   673.6 2431.48   735.4 2457.14
#Mann= 8 ,-1,0
       0     .06       0      70     .05       0     180     .07       0
     280      .1       0  386.28    .045       0  458.41      .1       0
     500     .06       0     600      .1       0
Bank Sta=386.28,458.41
XS Rating Curve= 0 ,0
Exp/Cntr=0.3,0.1

Type RM Length L Ch R = 1 ,54740   ,152.5,152.5,152.5
XS GIS Cut Line= 3
2382838.61221327699185.0371427212383333.33829462699138.463804332
2383399.82289193699082.458400351
#Sta/Elev= 30
       0 2440.42    13.6 2433.81    21.7 2426.27    25.7 2423.99    41.7 2422.96
    57.8  2411.5    73.9 2402.08    81.9 2399.71      90 2400.66     102 2403.38
   114.1 2404.11   122.5 2406.64   146.2 2406.85   182.4 2405.12   210.5 2399.72
   250.3  2400.2   294.9 2403.56     331 2403.26     335 2402.08  342.74 2396.13
   351.1 2393.96   383.2 2393.94   427.3 2394.38  432.98 2396.13   447.5 2402.58
   463.6 2413.42   471.3 2415.81   496.9 2417.38   536.2 2426.45   583.8 2430.99
#Mann= 7 ,-1,0
       0      .1       0      90     .06       0     190     .07       0
     290     .05       0  342.74    .045       0  432.98     .08       0
     480     .06       0
#XS Ineff= 2 , 0
           130.4 2411.92
Permanent Ineff=
       F       F
Bank Sta=342.74,432.98
XS Rating Curve= 0 ,0
Exp/Cntr(USF)=0,0
Exp/Cntr=0.3,0.1

Type RM Length L Ch R = 1 ,54588   ,97.2,97.2,97.2
XS GIS Cut Line= 4
2382836.98646901699213.2954726962383104.24437669699220.778886173
2383325.90282938 699365.77283374 2383489.9594887 699359.27277506
#Sta/Elev= 30
       0 2440.81    19.2 2428.85    31.2  2427.3    41.9 2419.89    59.2 2410.32
    95.2 2398.38   135.2 2399.27   167.3 2407.33   207.3 2407.04   231.3  2405.5
   266.9 2399.11   329.4 2398.02  349.87 2394.11   363.1 2392.12   406.9 2391.87
     425 2392.09   429.8 2394.15   434.6 2397.84   444.1 2407.56   448.9 2410.45
   487.1 2411.29   496.7 2413.73   516.1 2413.52   525.4    2417   546.5 2429.67
   562.5 2435.16   570.5 2436.69   630.6 2440.33   662.6 2439.11   696.4 2443.64
#Mann= 7 ,-1,0
       0      .1       0      90     .06       0     190     .07       0
  349.87    .045       0   429.8     .08       0  527.36     .07       0
  622.23      .1       0
#XS Ineff= 2 , 0
          170.32 2410.86
Permanent Ineff=
       F       F
Bank Sta=349.87,429.8
XS Rating Curve= 0 ,0
Exp/Cntr=0.3,0.1

Type RM Length L Ch R = 1 ,54490   ,156.6,156.6,156.6
XS GIS Cut Line= 4
2382830.39963007699286.7584097552383013.68070948699287.583484462
 2383316.8014847699462.8889938982383442.96869168699420.393955499
#Sta/Elev= 30
       0 2445.92     5.8 2440.68    17.8 2438.87    21.8 2436.93    29.8 2431.51
    49.8 2419.99    77.8 2406.95    85.8 2400.99    93.8 2397.91   117.8 2397.09
   223.1 2398.79   285.8  2400.9   315.5 2399.18   332.7 2392.71   343.3 2391.03
   379.5 2390.07     408 2390.65  413.51 2392.79   435.1 2404.39     441 2406.65
     505 2405.47   556.4 2406.56   597.4 2405.83   608.8 2408.46     614 2411.14
   621.4 2416.12   625.6 2417.79   629.9 2418.62   638.5 2421.97   666.6 2429.11
#Mann= 12 ,-1,0
       0      .1       0     100     .06       0  193.28     .07       0
  263.28      .1       0  313.28     .07       0   332.7    .045       0
  413.51     .07       0  423.28     .08       0  453.28     .07       0
  533.28     .08       0  643.45     .07       0  663.45      .1       0
#XS Ineff= 2 , 0
          284.04  2403.4
Permanent Ineff=
       F       F
Bank Sta=332.7,413.51
XS Rating Curve= 0 ,0
Exp/Cntr=0.3,0.1

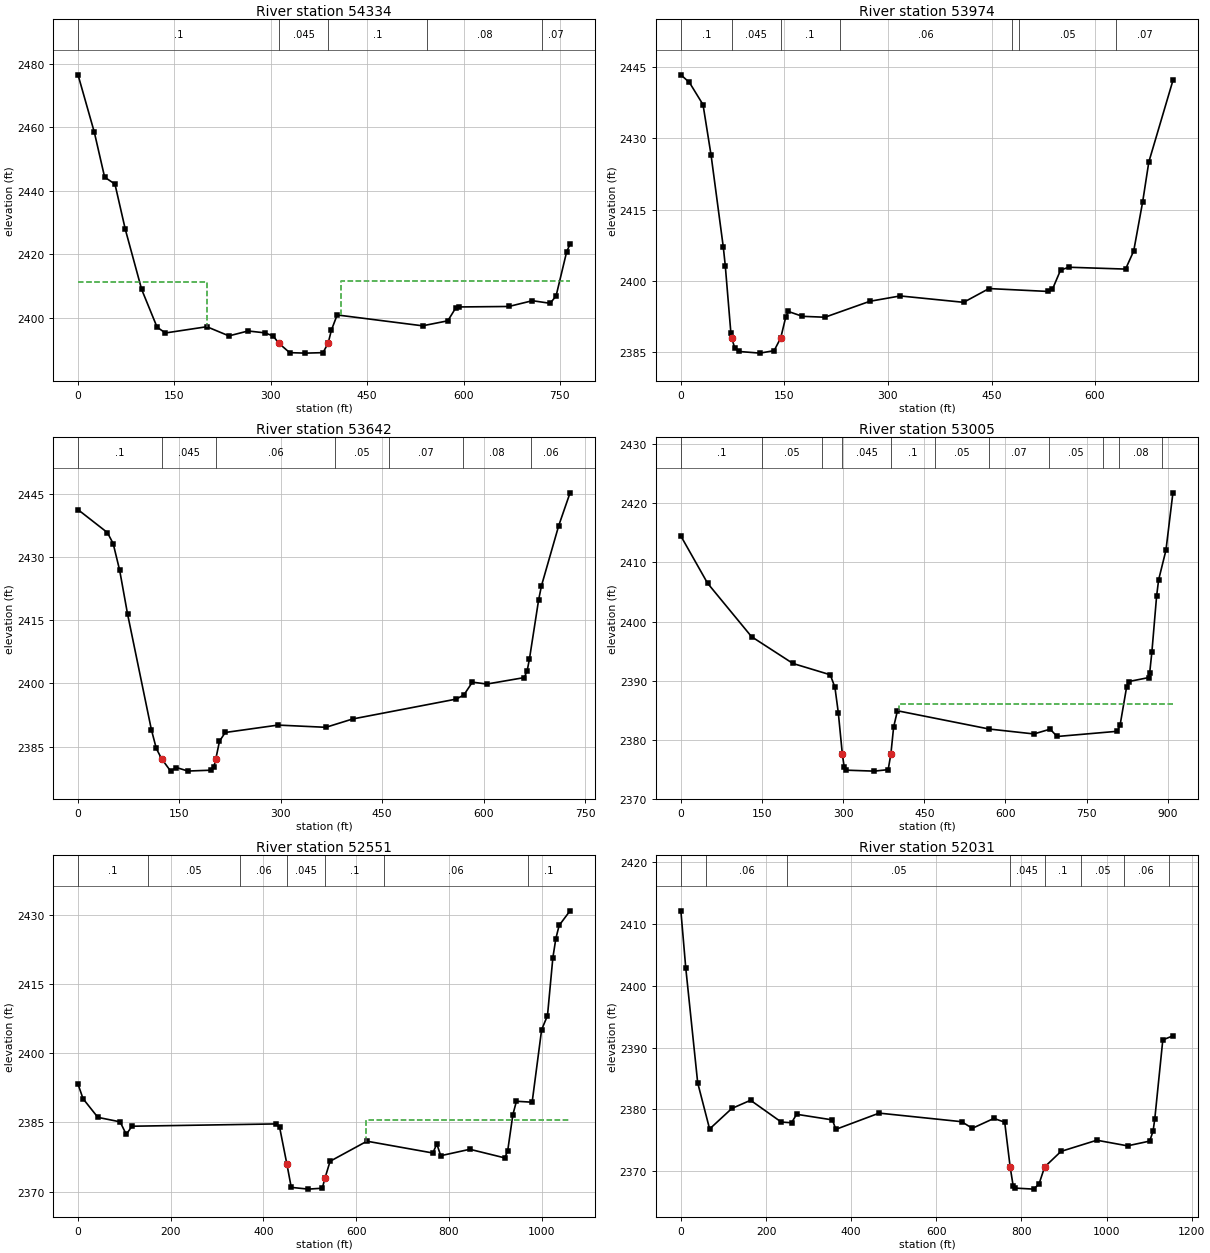
Type RM Length L Ch R = 1 ,54334   ,359.7,359.7,359.7
XS GIS Cut Line= 4
2382806.87593593699454.9225276652382910.39425692699446.112457794
2383336.47356805699615.3982579712383436.27224907699438.180318965
#Sta/Elev= 30
       0 2476.56    25.4 2458.44    41.4 2444.32    57.5 2442.12    73.6 2427.86
      99 2408.96     123 2397.06   135.9 2395.21   200.5 2397.18   234.9 2394.29
   264.7 2395.84   290.9 2395.25   303.8 2394.24   312.4    2392   329.4 2389.01
     354 2388.86   381.3 2389.01  389.34 2392.03   394.4 2396.13   403.3 2400.89
   536.2 2397.47   575.5 2399.04   587.9 2403.11   592.5 2403.41   670.5 2403.56
   707.2 2405.38   734.8 2404.56     744 2406.86   760.5 2420.79   765.8 2423.21
#Mann= 5 ,-1,0
       0      .1       0   312.4    .045       0  389.34      .1       0
  543.89     .08       0  722.37     .07       0
#XS Ineff= 2 , 0
          201.01 2411.21  409.53         2411.66
Permanent Ineff=
       F       F
Bank Sta=312.4,389.34
XS Rating Curve= 0 ,0
Exp/Cntr(USF)=0,0
Exp/Cntr=0.3,0.1

Type RM Length L Ch R = 1 ,53974   ,332.1,332.1,332.1
XS GIS Cut Line= 3
2383055.08797192699942.9782629712383535.28403627699498.114915731
2383560.68674893699445.738917953
#Sta/Elev= 30
       0 2443.29    12.4 2441.68    32.1 2437.02    43.8 2426.37    61.5 2407.06
    64.3 2403.24    72.4 2389.14   73.66 2388.04    77.8 2386.01    84.1 2385.19
   114.5 2384.84   135.1 2385.36  144.66 2388.04   152.1 2392.52   155.7 2393.59
     176 2392.57   208.7 2392.38   273.8 2395.73   317.7 2396.85   409.6 2395.51
   446.4  2398.4   532.4 2397.79   538.3 2398.26     550 2402.27   561.8 2402.88
   644.2 2402.49     656 2406.29     669 2416.63   677.9 2424.99   712.8  2442.1
#Mann= 7 ,-1,0
       0      .1       0   73.66    .045       0  144.66      .1       0
     230     .06       0     480     .08       0     490     .05       0
     630     .07       0
Bank Sta=73.66,144.66
XS Rating Curve= 0 ,0
Exp/Cntr=0.3,0.1

Type RM Length L Ch R = 1 ,53642   ,637,637,637
XS GIS Cut Line= 2
2383386.20570808700150.0529140312383633.38662638699465.400237425
#Sta/Elev= 30
       0 2441.28    43.5 2435.83      52 2433.22    61.6 2426.88    73.2 2416.55
   108.5 2389.04   115.8 2384.54  123.572382.114     137 2379.16   145.5 2380.02
   162.5 2379.18   196.6 2379.38   200.8 2380.03  203.912382.116   209.3 2386.28
   217.8 2388.34   295.9  2390.1   366.7 2389.57   406.3 2391.55   559.4 2396.27
   570.8 2397.25   583.4  2400.3   604.8 2399.85   660.1 2401.38   664.4 2402.98
   667.8 2405.79   681.4 2419.85   685.6 2423.19   711.1 2437.47   727.9 2445.28
#Mann= 7 ,-1,0
       0      .1       0  123.57    .045       0  203.91     .06       0
     380     .05       0     460     .07       0     570     .08       0
     670     .06       0
Bank Sta=123.57,203.91
XS Rating Curve= 0 ,0
Exp/Cntr=0.3,0.1

Type RM Length L Ch R = 1 ,53005   ,454,454,454
XS GIS Cut Line= 2
2383914.99803915700543.3456902092384238.13311745699693.086729358
#Sta/Elev= 30
       0 2414.47    49.4 2406.48   130.7 2397.44   207.2 2392.91   276.2    2391
   284.8 2388.87     291 2384.61   298.5 2377.58   301.9 2375.37   306.1 2374.86
   357.5  2374.7   383.2 2374.95   388.2 2377.58   393.3 2382.15   400.3 2384.91
     570 2381.82   652.7 2380.99   682.7  2381.8   695.5 2380.56   806.8 2381.44
   811.9 2382.46   823.9 2388.87   828.2 2389.86   864.6 2390.52   866.7 2391.35
   870.8 2394.93   879.5 2404.35   883.2 2407.07   896.7 2412.06   909.6 2421.78
#Mann= 11 ,-1,0
       0      .1       0     150     .05       0     260      .1       0
   298.5    .045       0   388.2      .1       0     470     .05       0
     570     .07       0     680     .05       0     780     .06       0
     810     .08       0     890     .06       0
#XS Ineff= 1 ,-1
   402.6 909.591    2386
Permanent Ineff=
       F
Bank Sta=298.5,388.2
XS Rating Curve= 0 ,0
Exp/Cntr=0.3,0.1

Type RM Length L Ch R = 1 ,52551   ,520,520,520
XS GIS Cut Line= 2
2384322.09920314700836.6521299552384635.99131931699822.622364083
#Sta/Elev= 30
       0  2393.3    10.8 2390.15    42.8 2386.11    90.8 2385.14   104.1 2382.41
   116.3 2384.19   426.5 2384.69   434.9 2383.97   450.62376.002     460 2370.96
   496.8 2370.58     527 2370.78   532.82372.974   543.8 2376.61   623.3 2380.95
   765.4  2378.4   774.1 2380.35   782.5 2377.81   845.3  2379.2   920.6 2377.34
   926.9 2378.83   938.1 2386.69   945.8 2389.59   979.7 2389.39  1000.2  2405.1
  1012.8 2408.12  1024.4 2420.65  1030.8 2424.77  1037.9 2427.64  1061.5  2430.8
#Mann= 7 ,-1,0
       0      .1       0     150     .05       0     350     .06       0
   450.6    .045       0   532.8      .1       0     660     .06       0
     970      .1       0
#XS Ineff= 2 , 0
                          620.36         2385.64
Permanent Ineff=
       F       F
Bank Sta=450.6,532.8
XS Rating Curve= 0 ,0
Exp/Cntr=0.3,0.1

Type RM Length L Ch R = 1 ,52031   ,99.1,99.1,99.1
XS GIS Cut Line= 3
2384934.46164088  701244.58260332384999.87640967700130.549268033
2385017.71680116700094.868485053
#Sta/Elev= 30
       0 2412.15    11.4 2402.95    39.5  2384.3    67.5 2376.82   119.6 2380.14
   163.7 2381.47   235.9 2377.94   259.9 2377.83   271.9  2379.2     356 2378.29
     364 2376.76   465.8 2379.39   659.6    2378   684.6 2376.93   735.3 2378.53
   760.7 2377.92   773.5 2370.67   780.7 2367.55   784.8 2367.25   828.8 2367.08
   841.3 2367.91  854.53 2370.67   892.9 2373.19   977.1    2375  1049.2 2374.09
  1101.3 2374.86  1109.3 2376.49  1113.3 2378.49  1132.1 2391.251155.845  2391.9
#Mann= 8 ,-1,0
       0      .1       0      60     .06       0     250     .05       0
   773.5    .045       0  854.53      .1       0     940     .05       0
    1040     .06       0 1145.95     .07       0
Bank Sta=773.5,854.53
XS Rating Curve= 0 ,0
Exp/Cntr(USF)=0,0
Exp/Cntr=0.3,0.1

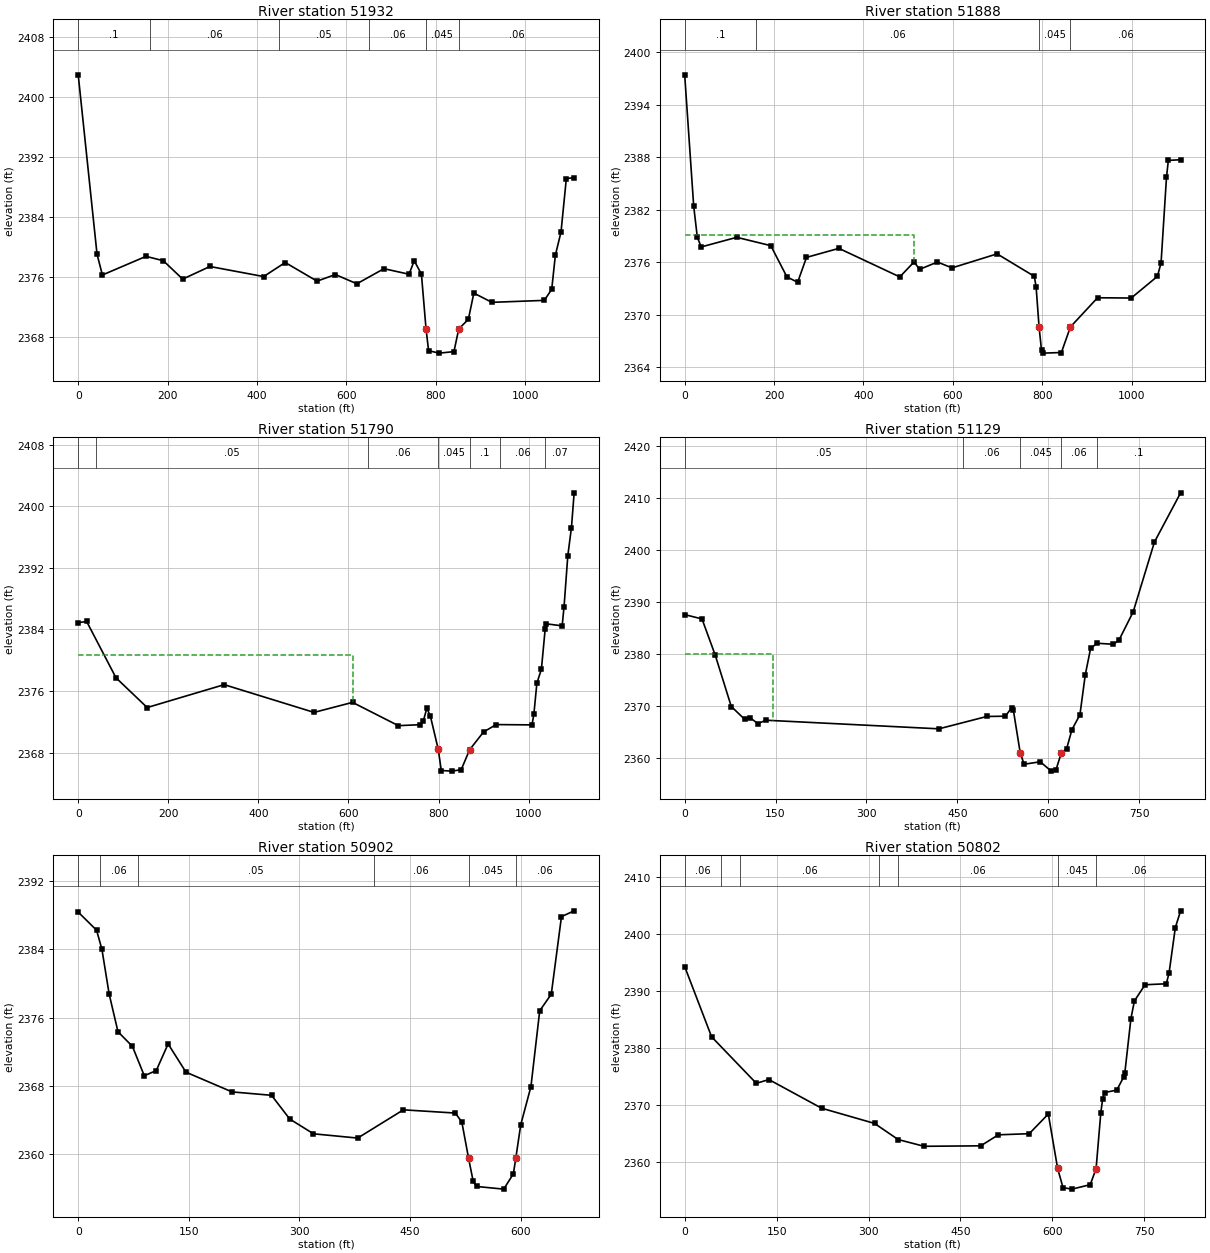
Type RM Length L Ch R = 1 ,51932   ,44.2,44.2,44.2
XS GIS Cut Line= 4
2385018.58785732701247.1357809982385073.63774245700482.762831397
2385109.94008811700242.4460267542385129.54384847  700143.9852495
#Sta/Elev= 30
       0  2402.9    42.1 2379.03    54.1 2376.26   151.7 2378.74   190.4 2378.16
   233.8 2375.71   294.7 2377.39     415 2376.05   463.2 2377.92   534.5 2375.44
   575.4 2376.32   623.6 2375.09   684.2  2377.1   740.3 2376.36   751.9 2378.15
     768 2376.39  778.35 2369.08   784.1 2366.18   808.1 2365.86   840.8 2366.06
  851.57 2369.08   873.1 2370.36   885.3 2373.85   925.7 2372.62    1043 2372.88
  1059.6 2374.35  1067.8 2378.91  1080.4 2381.98  1092.3 2389.09  1109.8 2389.22
#Mann= 6 ,-1,0
       0      .1       0     160     .06       0     450     .05       0
     650     .06       0  778.35    .045       0  851.57     .06       0
Bank Sta=778.35,851.57
XS Rating Curve= 0 ,0
Exp/Cntr=0.3,0.1

Type RM Length L Ch R = 1 ,51888   ,97.9,97.9,97.9
XS GIS Cut Line= 4
2385060.86925187701253.358703616  2385115.919137700488.985754015
2385152.22148266700248.6689493712385171.82524302700150.208172118
#Sta/Elev= 30
       0 2397.39    20.2 2382.38    28.3 2378.85    36.9 2377.74   116.5 2378.84
   192.7 2377.89   228.8 2374.32   252.8 2373.71   272.6 2376.55   345.1 2377.58
   481.4 2374.32   513.5 2376.04   525.5 2375.18   565.6 2376.02   598.1 2375.35
   699.1 2376.95   782.3 2374.39   786.4 2373.21  793.04  2368.6   798.5 2365.95
   802.6 2365.62     843 2365.69   863.2 2368.61   923.9 2371.94   999.3 2371.91
  1057.8 2374.38    1066 2375.91  1078.2  2385.7  1082.3 2387.62  1109.8  2387.7
#Mann= 4 ,-1,0
       0      .1       0     160     .06       0  793.04    .045       0
   863.2     .06       0
#XS Ineff= 2 , 0
          512.92 2379.13
Permanent Ineff=
       F       F
Bank Sta=793.04,863.2
XS Rating Curve= 0 ,0
Exp/Cntr=0.3,0.1

Type RM Length L Ch R = 1 ,51790   ,660.7,660.7,660.7
XS GIS Cut Line= 4
2385126.98785344701227.5599329392385241.70881231700624.810070211
2385213.96034712700343.2543845892385274.27624548700147.689329559
#Sta/Elev= 30
       0 2384.88    18.7 2385.04    83.9 2377.73   153.1 2373.87   324.1 2376.84
   523.6 2373.24   609.1 2374.54   710.8 2371.52   757.9 2371.64   765.9 2372.06
     774 2373.77     782 2372.74   799.4 2368.43   806.1  2365.7   830.2 2365.62
   850.3 2365.81   869.22368.409   899.9  2370.7     928 2371.66  1007.5 2371.62
  1011.7 2373.02  1018.3 2377.02  1028.4 2378.85  1036.8 2384.09  1039.7 2384.73
  1074.5 2384.47  1078.7 2386.98    1087 2393.56  1095.1 2397.23  1101.1 2401.73
#Mann= 7 ,-1,0
       0      .1       0      40     .05       0  643.57     .06       0
   799.4    .045       0   869.2      .1       0  936.49     .06       0
 1036.49     .07       0
#XS Ineff= 2 , 0
          609.87 2380.64
Permanent Ineff=
       F       F
Bank Sta=799.4,869.2
XS Rating Curve= 0 ,0
Exp/Cntr(USF)=0,0
Exp/Cntr=0.3,0.1

Type RM Length L Ch R = 1 ,51129   ,227.7,227.7,227.7
XS GIS Cut Line= 2
2385601.12719103701019.2294564012385939.57159516700273.842742424
#Sta/Elev= 30
       0 2387.58    28.6 2386.75    50.6 2379.75    76.9 2369.96    98.9 2367.52
   107.7 2367.83   120.9 2366.68     134 2367.33   419.6 2365.68   498.7 2368.05
   529.4  2368.1   539.5 2369.71   542.6 2369.21  553.75 2361.14   560.2 2358.89
   586.9 2359.36   605.1 2357.57   612.9 2357.82   621.7 2361.08   630.5 2361.88
   639.2 2365.52   652.4 2368.38   661.2 2376.02     670 2381.09   680.6 2382.09
   707.8 2381.89   716.9  2382.7   740.3 2388.11   775.4  2401.5   818.6 2410.93
#Mann= 5 ,-1,0
       0     .05       0     460     .06       0  553.75    .045       0
   621.7     .06       0     680      .1       0
#XS Ineff= 2 , 0
         145.479    2380
Permanent Ineff=
       F       F
Bank Sta=553.75,621.7
XS Rating Curve= 0 ,0
Exp/Cntr=0.3,0.1

Type RM Length L Ch R = 1 ,50902   ,99.4,99.4,99.4
XS GIS Cut Line= 3
2385754.96664398 701035.688368272385800.79851196701014.356803898
2386109.03935773700474.264638845
#Sta/Elev= 30
       0 2388.35    24.9 2386.23    32.2 2383.97    41.9 2378.77    53.9 2374.34
    73.5 2372.62    89.6 2369.18   105.8 2369.79   121.9 2372.91   146.1  2369.6
   208.5 2367.29   262.1 2366.89   286.8 2364.11     319 2362.38   378.9 2361.88
   440.9 2365.19   511.3 2364.81   520.1 2363.76  529.252359.521   535.5 2356.82
   540.1 2356.21   576.9  2355.9     590 2357.69  593.262359.518     600 2363.45
   613.8 2367.91   625.7 2376.79   641.4 2378.74   655.2 2387.82   672.4  2388.5
#Mann= 6 ,-1,0
       0     .05       0      30     .06       0   80.55     .05       0
  400.55     .06       0  529.25    .045       0  593.26     .06       0
Bank Sta=529.25,593.26
XS Rating Curve= 0 ,0
Exp/Cntr=0.3,0.1

Type RM Length L Ch R = 1 ,50802   ,25.9,25.9,25.9
XS GIS Cut Line= 3
2385883.33477964701176.4595440872385860.86155159701040.948777821
 2386232.9041322700481.456346046
#Sta/Elev= 30
       0 2394.25    43.9 2381.94   116.9 2373.78   137.4 2374.44   223.6 2369.41
   309.8 2366.75   348.4 2363.92   390.6 2362.74   483.1 2362.82   511.8 2364.75
   562.3 2364.95   593.4  2368.4   608.6 2358.85   617.4 2355.49   631.9 2355.23
   661.8 2356.01  671.37 2358.83   679.1 2368.66     682 2370.99   685.1 2372.16
   705.1 2372.59   716.6 2374.93   718.3 2375.65   728.2 2385.13   733.9 2388.22
   751.2 2391.06   785.9 2391.23   790.4 2393.09   800.7 2401.09   809.3 2404.02
#Mann= 7 ,-1,0
       0     .06       0      60     .05       0      90     .06       0
  317.36     .05       0  347.36     .06       0   608.6    .045       0
  671.37     .06       0
Bank Sta=608.6,671.37
XS Rating Curve= 0 ,0
Exp/Cntr=0.3,0.1

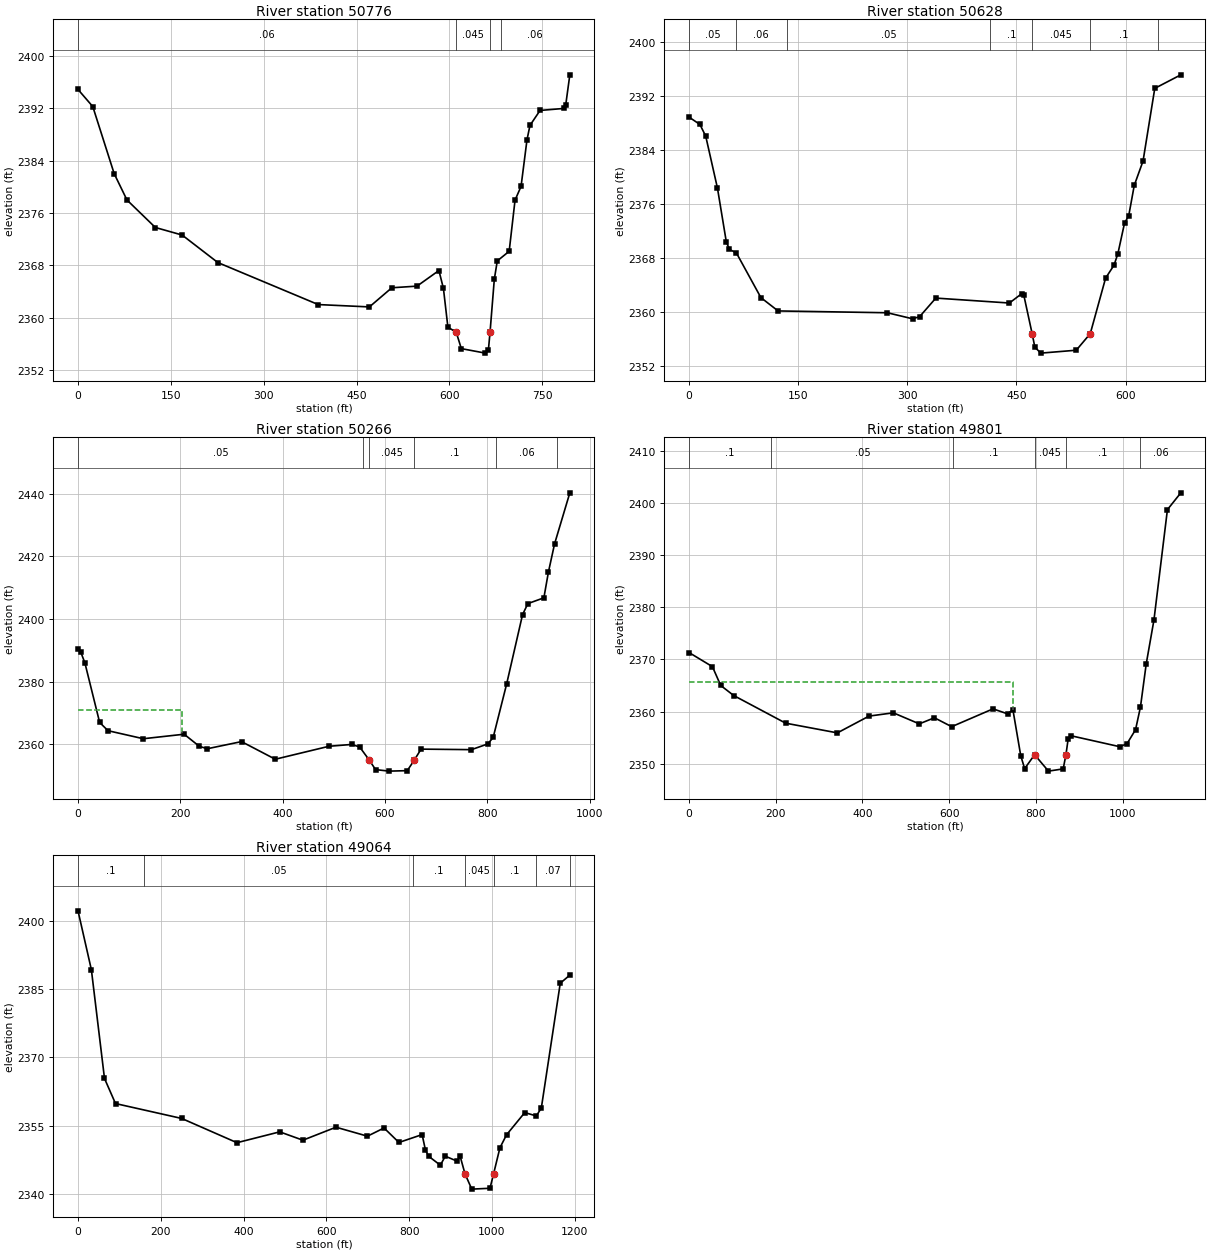
Type RM Length L Ch R = 1 ,50776   ,147.9,147.9,147.9
XS GIS Cut Line= 3
2385909.15709704701181.550684997 2385877.2115059701063.090172283
2386249.25408651700503.597740508
#Sta/Elev= 30
       0 2394.91    23.9 2392.29    58.4 2382.04    79.1    2378     125 2373.79
   168.2 2372.64   225.9 2368.43   388.1    2362   470.8 2361.64     507 2364.57
   547.7 2364.82   583.1 2367.21   590.4 2364.46   597.6 2358.54  611.04 2357.77
   619.3 2355.26   658.2 2354.57     663 2355.01   665.7 2357.76   672.6 2365.87
   677.4 2368.68   696.6 2370.15   706.1 2377.98   715.8 2380.08   725.4 2387.21
   730.2 2389.41   746.5  2391.7   785.4 2392.01   787.9 2392.49   794.6 2397.15
#Mann= 4 ,-1,0
       0     .06       0  611.04    .045       0   665.7      .1       0
  682.69     .06       0
Bank Sta=611.04,665.7
XS Rating Curve= 0 ,0
Exp/Cntr=0.3,0.1

Type RM Length L Ch R = 1 ,50628   ,362.9,362.9,362.9
XS GIS Cut Line= 4
2386036.62468656701152.0539662432386030.29378254701098.241282108
2386335.75990131700640.8334669612386343.67353133700569.610796782
#Sta/Elev= 30
       0 2388.83      15 2387.74      23    2386    39.1 2378.32    51.2 2370.42
    55.5 2369.26    65.1 2368.74    98.8 2362.13   122.4 2360.16   272.6 2359.89
   307.2    2359   316.9 2359.31   339.2 2362.06   440.3 2361.33   457.2 2362.71
   460.1  2362.5   471.6 2356.78   475.3  2354.8   483.5 2353.92   532.2 2354.35
  551.45  2356.8   572.5 2365.01   584.1 2366.93   589.4 2368.63   598.5 2373.14
   604.3 2374.24   611.9 2378.73     624 2382.34   640.1 2393.08   675.9 2395.08
#Mann= 7 ,-1,0
       0     .05       0   64.18     .06       0  134.18     .05       0
  414.18      .1       0   471.6    .045       0  551.45      .1       0
  644.21     .06       0
Bank Sta=471.6,551.45
XS Rating Curve= 0 ,0
Exp/Cntr(USF)=0,0
Exp/Cntr=0.3,0.1

Type RM Length L Ch R = 1 ,50266   ,465.2,465.2,465.2
XS GIS Cut Line= 3
2386139.05135476701367.2564401412386233.00787667701345.026275214
2386788.21890613700682.329785776
#Sta/Elev= 30
       0 2390.28     5.3 2389.49    13.5 2385.95    42.3 2366.95    58.7 2364.32
   127.7 2361.76   207.4  2363.2   237.2 2359.32   252.9 2358.57   319.5 2360.84
   385.5 2355.21   490.5 2359.35   534.7 2359.93   550.3 2359.14  569.282354.914
   581.4  2351.9   607.7 2351.41   643.4 2351.56  657.112354.914   670.4 2358.44
   768.8 2358.27   800.8  2360.1   811.3 2362.16   837.4 2379.09   868.7 2401.39
   879.1 2404.92   910.4 2406.77   919.3 2415.02   931.3 2424.01   961.1 2440.31
#Mann= 6 ,-1,0
       0     .05       0  556.55      .1       0  569.28    .045       0
  657.11      .1       0  816.55     .06       0  936.55      .1       0
#XS Ineff= 2 , 0
          203.61 2371.07
Permanent Ineff=
       F       F
Bank Sta=569.28,657.11
XS Rating Curve= 0 ,0
Exp/Cntr=0.3,0.1

Type RM Length L Ch R = 1 ,49801   ,736.7,736.7,736.7
XS GIS Cut Line= 2
2386332.07148224701817.4517364722387141.08363687 701022.43622746
#Sta/Elev= 30
       0 2371.32      54 2368.61    73.1    2365   103.1 2363.07     223 2357.76
   342.2  2355.9   415.1 2359.12   471.2 2359.75   531.1 2357.63     566  2358.8
   605.8 2357.09   701.2 2360.51   734.8 2359.55     747 2360.36   765.1 2351.52
   774.1 2349.04  797.08 2351.71     829 2348.56     863 2348.99   869.4 2351.74
   874.3 2354.65   879.9 2355.37   993.4 2353.25  1010.1 2353.81  1029.9 2356.52
  1041.2 2360.87  1054.5 2369.14  1072.3 2377.56  1103.4 2398.75  1134.3 2401.97
#Mann= 6 ,-1,0
       0      .1       0     190     .05       0     610      .1       0
  797.08    .045       0   869.4      .1       0    1040     .06       0
#XS Ineff= 2 , 0
          746.86 2365.68
Permanent Ineff=
       F       F
Bank Sta=797.08,869.4
XS Rating Curve= 0 ,0
Exp/Cntr=0.3,0.1

Type RM Length L Ch R = 1 ,49064   ,447.9,447.9,447.9
XS GIS Cut Line= 5
2386416.12100874701986.6464125122386619.13839269 701808.10538873
2387304.90317279 701818.839915792387457.39697998701817.875302334
2387529.31721172701783.489261371
#Sta/Elev= 30
       0 2402.19    32.3 2389.27      64  2365.4    90.6 2359.89   250.6 2356.62
   384.1  2351.3   487.4 2353.68   543.4 2351.85   623.4  2354.7   699.4 2352.73
   739.5 2354.53   775.5 2351.35   831.5 2353.08   839.6 2349.66   847.4 2348.32
   875.5 2346.36   887.5 2348.34   915.5 2347.27   923.5 2348.28  935.222344.437
   951.5 2341.11   995.5  2341.3 1004.122344.437  1019.5 2350.18  1035.5 2353.03
  1079.5 2357.91  1107.5 2357.17  1119.6 2358.94  1165.3  2386.3  1188.4 2388.08
#Mann= 7 ,-1,0
       0      .1       0     160     .05       0  810.36      .1       0
  935.22    .045       0 1004.12      .1       0 1106.21     .07       0
 1188.42     .06       0
Bank Sta=935.22,1004.12
XS Rating Curve= 0 ,0
Exp/Cntr=0.3,0.1