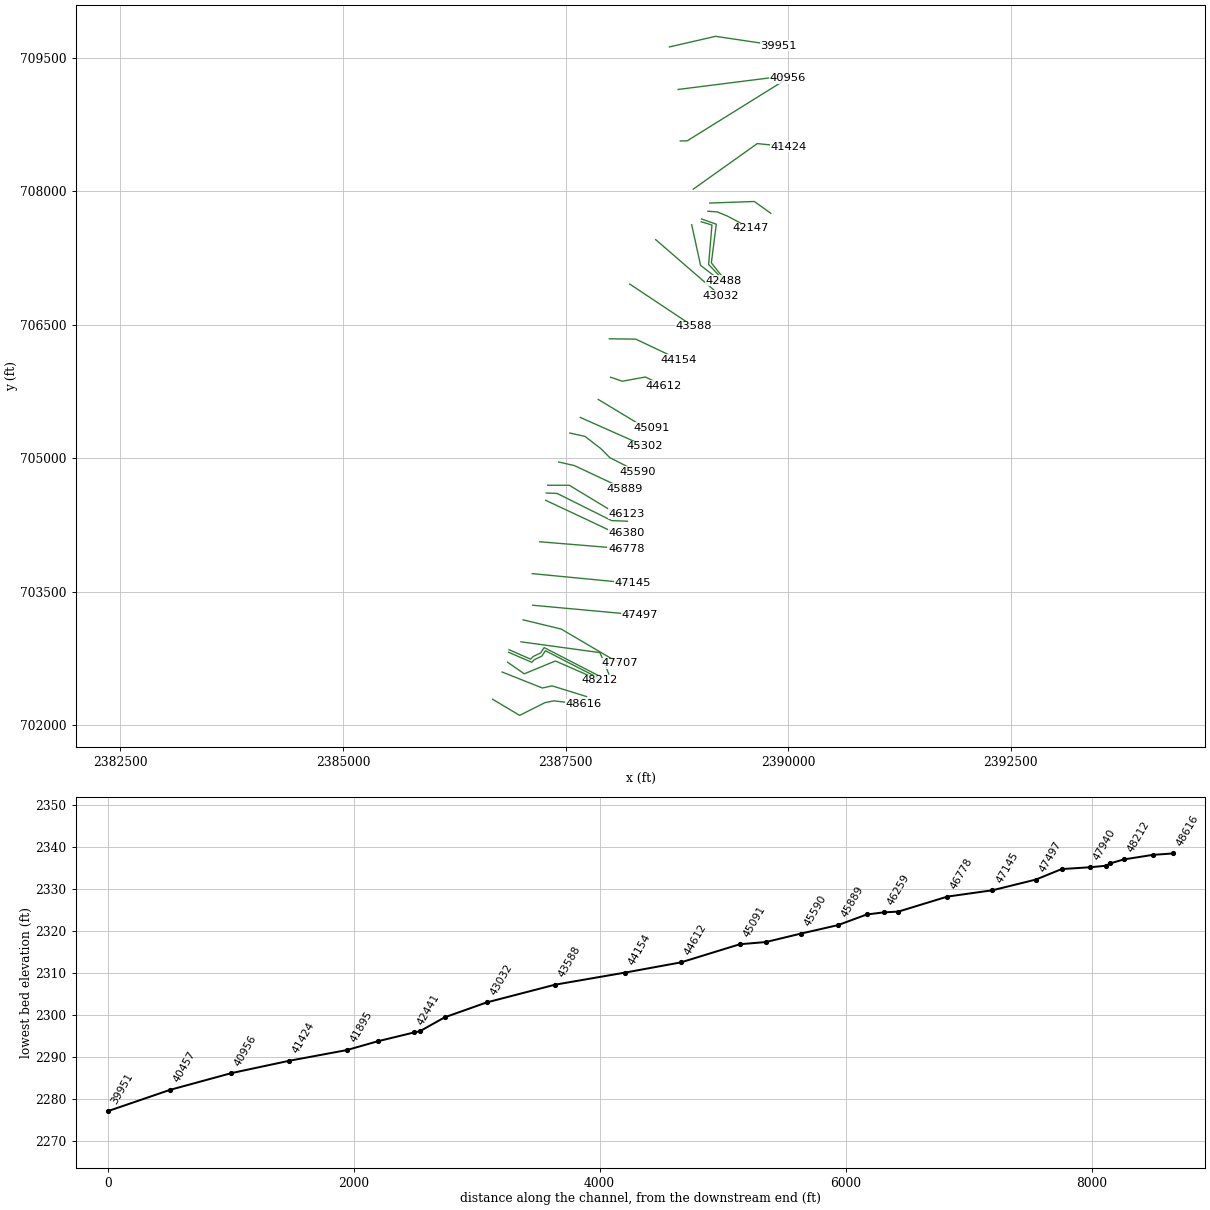
HEC-RAS study DRKFK_2.prj: DRKFK_2

--- DRKFK_2.g01 (geometry) --- (continued)

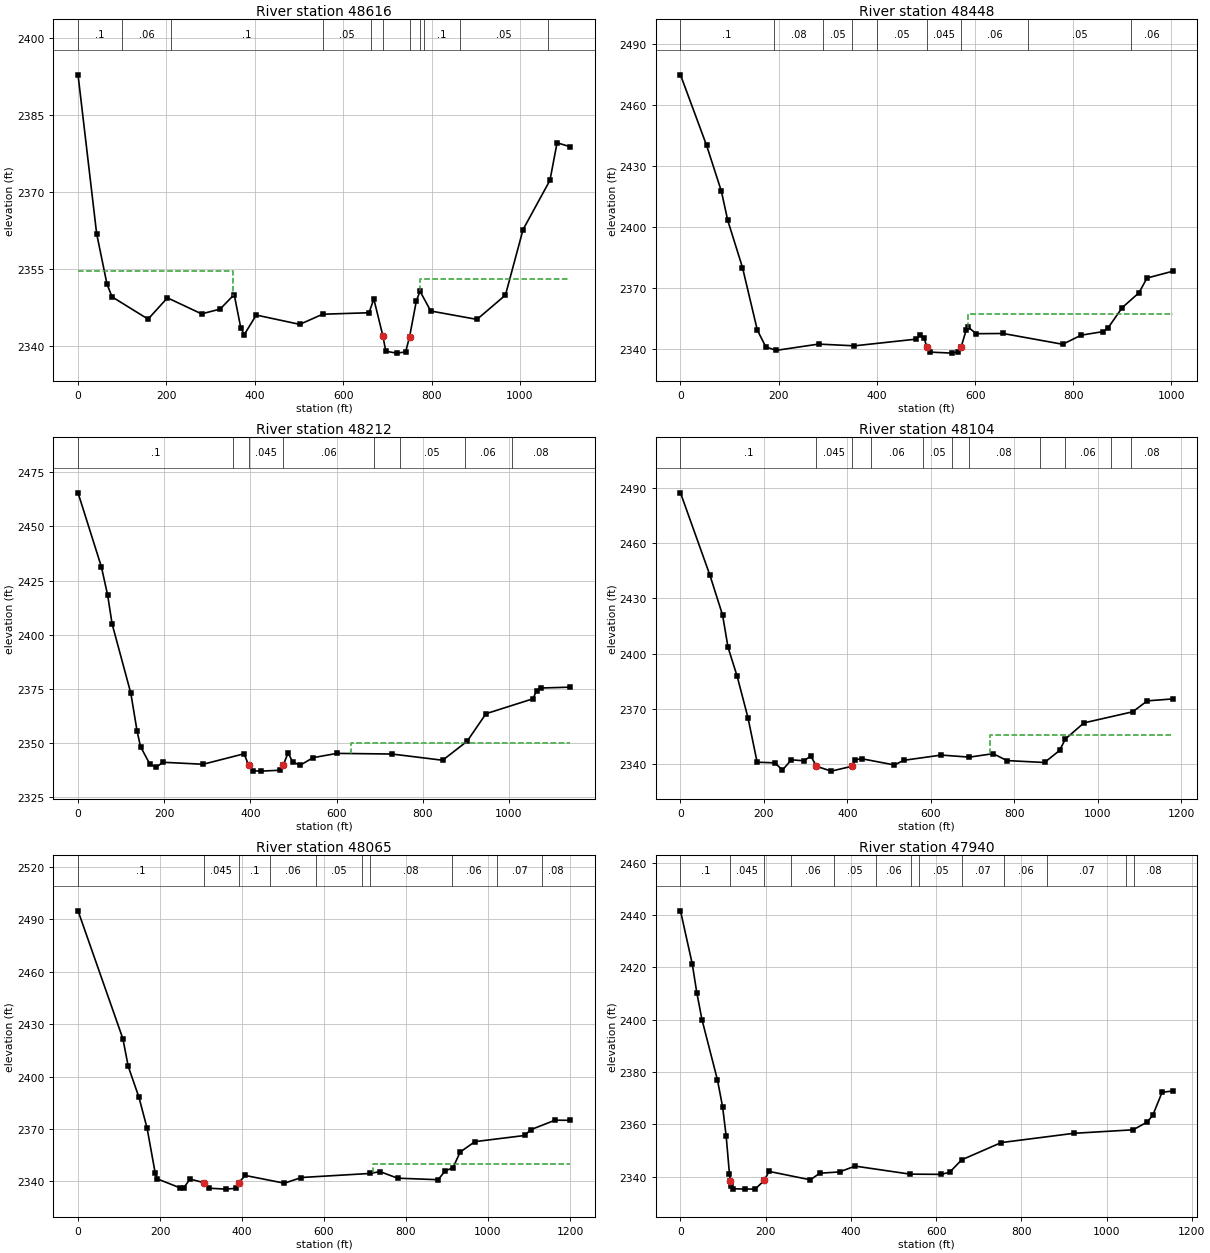
Type RM Length L Ch R = 1 ,48616   ,167.8,167.8,167.8
XS GIS Cut Line= 5
2386679.97626911702294.2128955892386983.70153782702113.556404654
2387268.43434415702256.7491981412387368.19880297702276.633442533
2387705.99450734702237.265720231
#Sta/Elev= 30
       0 2392.85    42.1 2361.87    65.4 2352.07    76.8 2349.54   158.5 2345.18
   202.3 2349.34   279.5 2346.21   321.4 2347.14   353.4 2349.98   368.4  2343.4
   376.3 2342.18   403.2 2345.98   501.7 2344.16   553.5 2346.14   658.4 2346.43
   669.3 2349.11   689.82341.903   696.3 2338.92   720.8 2338.55   741.2 2338.78
   750.1 2341.71   765.6 2348.78   773.8 2350.63     798 2346.77   902.7 2345.13
   967.1 2349.87  1006.9 2362.65  1067.8 2372.27  1083.9 2379.59  1113.9 2378.81
#Mann= 11 ,-1,0
       0      .1       0     100     .06       0     210      .1       0
  553.39     .05       0  663.39      .1       0   689.8    .045       0
   750.1      .1       0  773.83     .06       0  783.83      .1       0
  863.83     .05       0 1063.83     .06       0
#XS Ineff= 2 , 0
          350.04 2354.65  773.72         2352.99
Permanent Ineff=
       F       F
Bank Sta=689.8,750.1
XS Rating Curve= 0 ,0
Exp/Cntr=0.3,0.1

Type RM Length L Ch R = 1 ,48448   ,236.2,236.2,236.2
XS GIS Cut Line= 4
2386786.75616442 702600.294397382387238.65068808702420.865689456
2387347.63701438702444.7895171792387734.40556257702325.170378563
#Sta/Elev= 30
       0 2474.68    53.2 2440.05    83.3 2417.57    96.2 2403.35   126.3 2380.18
   156.5 2349.48   173.7 2341.29   194.5 2339.54   281.3 2342.63   354.4 2341.78
   479.2 2345.04   487.8    2347     496 2345.64   501.82341.199   508.2  2338.7
   553.3  2338.2   565.6  2338.9   571.7 2341.31     582 2349.62   586.1 2350.87
   602.5 2347.73     657 2347.83   778.4 2342.54   816.1 2347.01   859.9 2348.72
   870.5 2350.48   899.8 2360.56   933.7 2367.77   950.1 2375.02  1002.6 2378.36
#Mann= 9 ,-1,0
       0      .1       0     190     .08       0     290     .05       0
     350     .06       0     400     .05       0   501.8    .045       0
   571.7     .06       0  707.79     .05       0  917.79     .06       0
#XS Ineff= 2 , 0
                           585.7         2357.63
Permanent Ineff=
       F       F
Bank Sta=501.8,571.7
XS Rating Curve= 0 ,0
Exp/Cntr(USF)=0,0
Exp/Cntr=0.3,0.1

Type RM Length L Ch R = 1 ,48212   ,107.9,107.9,107.9
XS GIS Cut Line= 4
2386847.75437104702710.8454058072387035.33671225702579.928563504
 2387385.0996193702724.5232848542387875.54928226702509.585185549
#Sta/Elev= 30
       0 2465.45    54.2 2431.33    68.8 2418.19    79.1 2404.99   122.5 2373.05
   137.1 2355.55   145.1 2348.38   166.4 2340.47     181 2338.83   196.9  2341.2
   290.3 2340.28   385.5 2345.11   395.7 2339.97   407.1 2337.27   424.4 2337.11
   467.7 2337.51  476.58 2339.95   487.6 2345.53     498 2341.41   515.3 2339.78
   545.6 2343.32   600.9 2345.29   728.5    2345   846.4 2342.13   903.2  2350.9
   946.9 2363.58    1056 2370.47  1064.5 2374.25  1073.5 2375.441142.703 2375.83
#Mann= 8 ,-1,0
       0      .1       0  358.75     .06       0   395.7    .045       0
  476.58     .06       0  687.22     .08       0  747.22     .05       0
  897.22     .06       0 1007.22     .08       0
#XS Ineff= 2 , 0
                           633.4            2350
Permanent Ineff=
       F       F
Bank Sta=395.7,476.58
XS Rating Curve= 0 ,0
Exp/Cntr(USF)=0,0
Exp/Cntr=0.3,0.1

Type RM Length L Ch R = 1 ,48104   ,38.7,38.7,38.7
XS GIS Cut Line= 6
2386859.60179466 702822.144340172387119.40025974702709.523794651
2387148.71000056702738.833535465 2387233.7352725702779.814297832
 2387272.7156646702839.4009813682387885.51207149702524.241316208
#Sta/Elev= 30
       0 2487.39    70.4 2442.72   100.9 2420.96     114 2403.43   135.8 2387.74
   161.9 2365.09   183.7 2341.03   226.2 2340.67   244.5 2336.77   265.8 2342.32
   295.6  2341.8   312.5 2344.35   325.9 2338.83   361.2 2336.18   410.1 2338.76
   419.1 2342.39   434.8 2342.89   512.8 2339.53   535.2 2342.06   625.2  2344.9
   692.7 2343.78   749.4 2345.67   782.6 2341.91   872.6 2340.87   908.6  2347.4
   922.8 2353.68   967.1 2362.39    1084 2368.42  1118.9 2374.36    1180 2375.41
#Mann= 11 ,-1,0
       0      .1       0   325.9    .045       0   410.1      .1       0
   456.9     .06       0  580.87     .05       0  650.87     .06       0
  690.87     .08       0  860.87     .05       0  920.87     .06       0
 1030.87     .07       0 1080.87     .08       0
#XS Ineff= 2 , 0
                          740.79         2355.68
Permanent Ineff=
       F       F
Bank Sta=325.9,410.1
XS Rating Curve= 0 ,0
Exp/Cntr=0.3,0.1

Type RM Length L Ch R = 1 ,48065   ,125.5,125.5,125.5
XS GIS Cut Line= 6
2386864.04061873702851.0613326942387105.64798872702744.937606849
2387134.95772954702774.2473476632387219.98300148 702815.22811003
2387258.96339358702874.8147935662387906.84262671702540.164669385
#Sta/Elev= 30
       0 2494.81   109.4 2421.64   122.5 2405.79   148.7 2388.06   168.5 2370.39
     188  2345.1   192.4 2341.56   249.2 2336.29   257.9 2336.35   273.1 2341.35
   306.7 2339.33   320.5 2336.12   360.5  2335.6   385.8 2336.08  392.13 2339.35
   407.9 2343.41   503.4 2338.99   544.9 2342.25   711.6 2344.56   736.6 2345.61
   779.5 2341.86   878.2 2340.99   896.2 2346.18   914.2  2347.7   932.2 2356.83
   968.2 2362.77  1089.8  2366.3  1103.8 2369.56  1163.7 2375.04  1200.8 2374.96
#Mann= 10 ,-1,0
       0      .1       0   306.7    .045       0  392.13      .1       0
  467.63     .06       0   581.6     .05       0   691.6     .07       0
   711.6     .08       0   911.6     .06       0  1021.6     .07       0
  1131.6     .08       0
#XS Ineff= 2 , 0
                           719.6            2350
Permanent Ineff=
       F       F
Bank Sta=306.7,392.13
XS Rating Curve= 0 ,0
Exp/Cntr=0.3,0.1

Type RM Length L Ch R = 1 ,47940   ,232.8,232.8,232.8
XS GIS Cut Line= 3
2386998.21104056702939.4613841582387885.31919586702818.314455459
2387984.97231463702577.974580783
#Sta/Elev= 30
       0 2441.58    27.7 2421.25    38.3  2410.3    50.4 2400.04    86.8 2376.96
    98.9 2366.65   107.2 2355.54     115 2340.97     117 2338.54   119.1  2336.3
   123.1 2335.41   151.4 2335.25   175.6  2335.3  196.58 2338.57   207.9 2342.02
   304.8 2338.81     327 2341.33   373.4 2341.82   409.7 2344.05   538.9 2340.98
   611.6 2340.89   631.8 2341.69     660 2346.44   752.9 2353.03   922.9 2356.57
  1062.3 2357.91  1095.8  2360.9  1108.8 2363.55  1130.4 2372.241155.523 2372.76
#Mann= 13 ,-1,0
       0      .1       0     117    .045       0  196.58      .1       0
     260     .06       0     360     .05       0     460     .06       0
     540     .07       0     560     .05       0     660     .07       0
     760     .06       0     860     .07       0 1045.34     .06       0
 1065.34     .08       0
Bank Sta=117,196.58
XS Rating Curve= 0 ,0
Exp/Cntr(USF)=0,0
Exp/Cntr=0.3,0.1

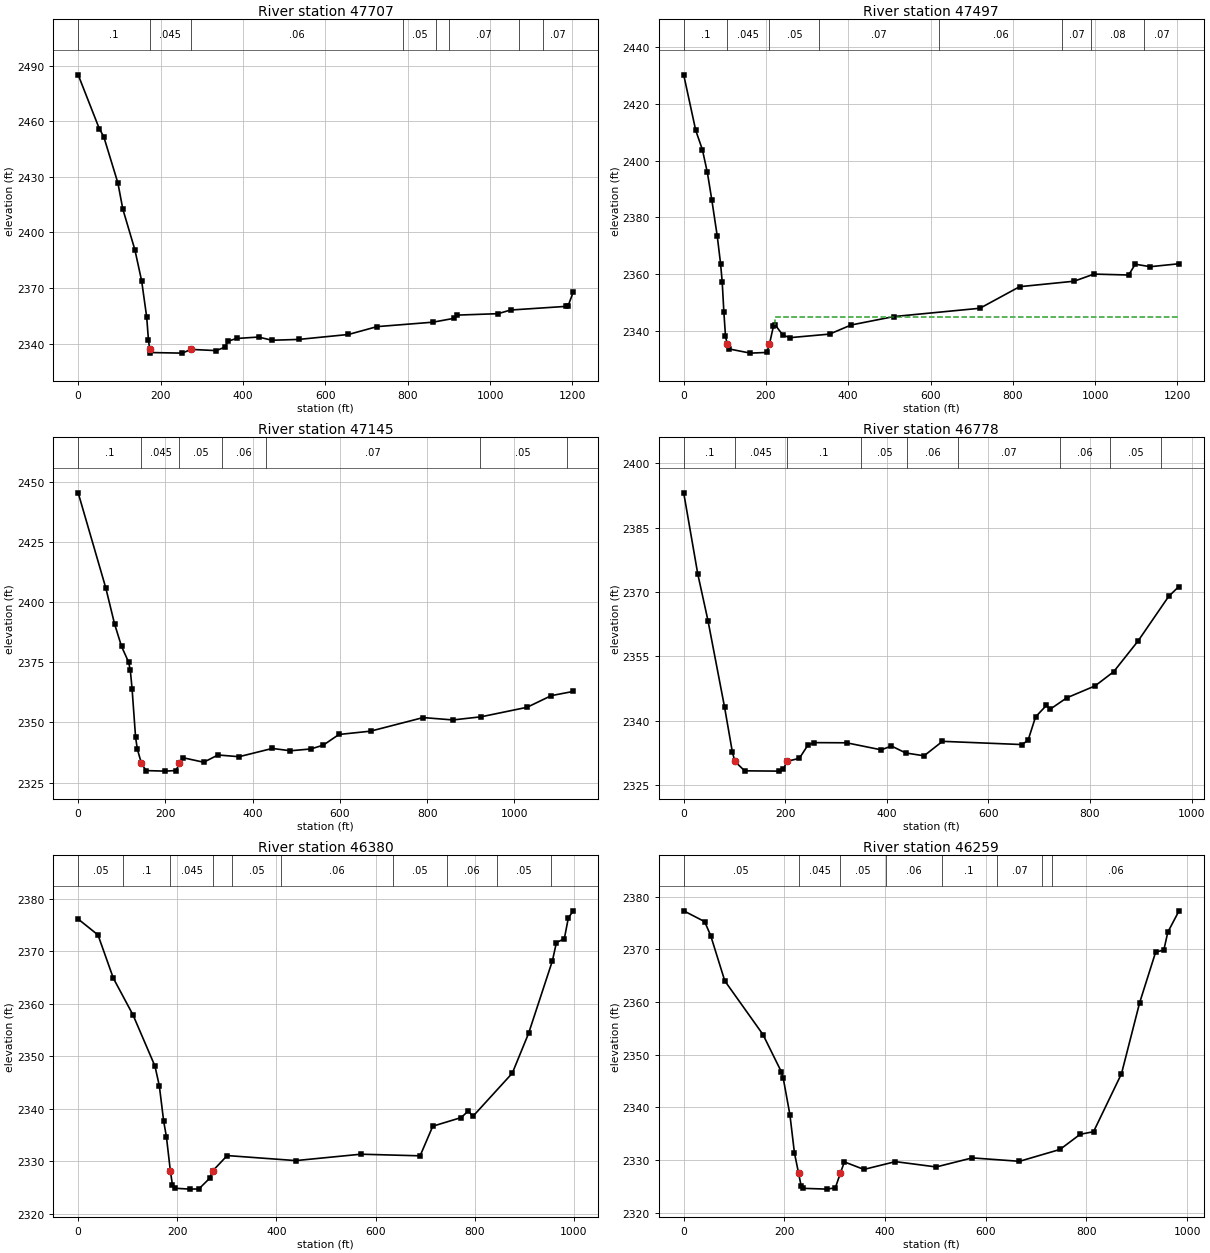
Type RM Length L Ch R = 1 ,47707   ,209.9,209.9,209.9
XS GIS Cut Line= 3
2387022.40106193703186.3028923312387449.39824571 703083.06234065
2388106.78024375 702696.58992682
#Sta/Elev= 30
       0 2485.08    51.2 2456.05    62.1 2451.68    96.5 2426.62   108.4 2412.58
   137.6 2390.66   154.1 2373.82   166.4 2354.19   170.6 2341.83  173.72 2336.88
   174.7 2335.13   252.9 2334.81   273.62336.828   335.2 2336.17   355.7 2337.98
     364 2341.28   384.5 2342.72     438 2343.49   470.4 2341.76   535.3 2342.21
   656.1 2344.88   725.6 2349.12   861.3 2351.52   911.2 2353.55   920.4 2355.34
  1019.2 2356.11  1049.8 2358.08  1184.9 2360.06  1189.6 2360.49  1201.9 2367.76
#Mann= 8 ,-1,0
       0      .1       0  173.72    .045       0   273.6     .06       0
   789.3     .05       0   869.3     .06       0   899.3     .07       0
  1069.3     .06       0  1129.3     .07       0
Bank Sta=173.72,273.6
XS Rating Curve= 0 ,0
Exp/Cntr(USF)=0,0
Exp/Cntr=0.3,0.1

Type RM Length L Ch R = 1 ,47497   ,352.3,352.3,352.3
XS GIS Cut Line= 2
2387130.95063277703350.3060367432388329.56298033703240.407226813
#Sta/Elev= 30
       0 2430.16    29.3 2410.59    45.4 2403.86    57.5 2395.83    68.4 2386.14
    81.6 2373.41    89.6 2363.81    93.6 2357.38    97.6 2346.86   101.6 2338.23
   105.7 2335.52   109.7 2333.79   161.9  2332.3   202.1 2332.54  208.53 2335.51
   218.1 2341.74   222.2 2342.24   241.3 2338.61   258.3 2337.74   354.7 2338.99
   406.9 2342.19   511.4 2345.17   720.2 2348.08   816.6 2355.66   949.2 2357.59
   997.4 2360.09  1081.7 2359.77  1097.8 2363.57    1134 2362.69  1203.6 2363.72
#Mann= 8 ,-1,0
       0      .1       0   105.7    .045       0  208.53     .05       0
     330     .07       0     620     .06       0     920     .07       0
     990     .08       0    1120     .07       0
#XS Ineff= 2 , 0
                           222.2            2345
Permanent Ineff=
       F       F
Bank Sta=105.7,208.53
XS Rating Curve= 0 ,0
Exp/Cntr=0.3,0.1

Type RM Length L Ch R = 1 ,47145   ,366.7,366.7,366.7
XS GIS Cut Line= 2
2387125.21991742703705.4226107692388254.62193012703595.999578396
#Sta/Elev= 30
       0 2445.55    63.2 2406.03    83.3 2391.07    99.4 2381.64   115.5 2375.14
   119.5 2371.72   123.5 2364.11   131.6 2343.79   135.6 2338.93  145.02 2332.93
   155.7 2329.97   199.9 2329.75     224    2330  232.212332.932   240.1 2335.33
   287.8 2333.45   320.4 2336.47   368.7 2335.75     445 2339.19   486.5 2338.22
   533.4 2338.98   561.6 2340.55   597.7    2345   670.1 2346.38   790.6 2352.03
     859 2351.05   923.3 2352.35  1028.8 2356.31  1084.3 2361.16 1134.69 2362.92
#Mann= 7 ,-1,0
       0      .1       0  145.02    .045       0  232.21     .05       0
     330     .06       0     430     .07       0     920     .05       0
    1120     .08       0
Bank Sta=145.02,232.21
XS Rating Curve= 0 ,0
Exp/Cntr(USF)=0,0
Exp/Cntr=0.3,0.1

Type RM Length L Ch R = 1 ,46778   ,398,398,398
XS GIS Cut Line= 2
 2387208.5693563704063.198669513 2388180.0297861 703983.24172135
#Sta/Elev= 30
       0 2393.08    27.7 2374.18    47.8  2363.3    80.5 2343.11    95.9 2332.63
  100.772330.505     120 2328.31   188.2 2328.24   196.3 2328.63  202.972330.504
   227.7 2331.23   244.4 2334.27   256.5 2334.88   320.7 2334.84   388.9  2333.2
     409 2334.09   437.1 2332.47   473.2 2331.81   509.5 2335.18   665.8 2334.43
   677.9  2335.4   692.7 2340.87     714 2343.55     722 2342.71   754.1 2345.31
   809.9  2348.1   846.5  2351.4   894.6 2358.57   954.8 2368.95   974.7 2371.23
#Mann= 9 ,-1,0
       0      .1       0  100.77    .045       0  202.97      .1       0
     350     .05       0     440     .06       0     540     .07       0
     740     .06       0     840     .05       0     940     .06       0
Bank Sta=100.77,202.97
XS Rating Curve= 0 ,0
Exp/Cntr=0.3,0.1

Type RM Length L Ch R = 1 ,46380   ,120.5,120.5,120.5
XS GIS Cut Line= 4
2387275.91904747704528.6412246282387688.00604747704335.745224628
 2388074.7937974704152.4894056292388190.07877793704162.259319234
#Sta/Elev= 30
       0 2376.16      40 2373.13    70.9 2364.89   110.7 2357.86   154.9 2348.12
   163.7 2344.36   172.5  2337.6     178 2334.65  186.022328.095   190.2 2325.43
   194.6 2324.83   225.8 2324.66   243.5  2324.7   265.3 2326.73  270.982328.095
   300.6 2331.06     439  2330.1   570.3 2331.32   689.8 2331.01   715.3 2336.66
   772.4  2338.3   787.2 2339.57     796 2338.51   875.7 2346.77   908.5 2354.34
   956.6 2368.19   964.7 2371.66   980.7 2372.42   988.8 2376.38   998.7 2377.73
#Mann= 10 ,-1,0
       0     .05       0      90      .1       0  186.02    .045       0
  270.98      .1       0     310     .05       0     410     .06       0
     635     .05       0     745     .06       0     845     .05       0
     953     .06       0
Bank Sta=186.02,270.98
XS Rating Curve= 0 ,0
Exp/Cntr=0.3,0.1

Type RM Length L Ch R = 1 ,46259   ,136.8,136.8,136.8
XS GIS Cut Line= 4
2387282.61025919704610.6508705082387404.57772411704605.813396889
2388016.17431577704300.9920924212388193.93499782 704293.58936723
#Sta/Elev= 30
       0  2377.3    41.6 2375.25    53.6  2372.6    81.6    2364   157.4 2353.82
   193.8 2346.77   197.6 2345.58     211 2338.56   219.9 2331.36  228.232327.473
   233.3 2325.05   237.8 2324.62   284.9 2324.47   301.2 2324.73  311.072327.473
   319.1 2329.64   357.9 2328.21   420.5 2329.69   501.5 2328.68     573  2330.4
   666.9 2329.75   747.3    2332   787.5 2334.88     814 2335.37   869.5 2346.38
   905.5 2359.84   937.5 2369.51   953.5 2369.81   961.5 2373.25   983.3 2377.21
#Mann= 8 ,-1,0
       0     .05       0  228.23    .045       0  311.07     .05       0
  402.06     .06       0  512.06      .1       0  622.06     .07       0
  712.06     .05       0  732.06     .06       0
Bank Sta=228.23,311.07
XS Rating Curve= 0 ,0
Exp/Cntr=0.3,0.1

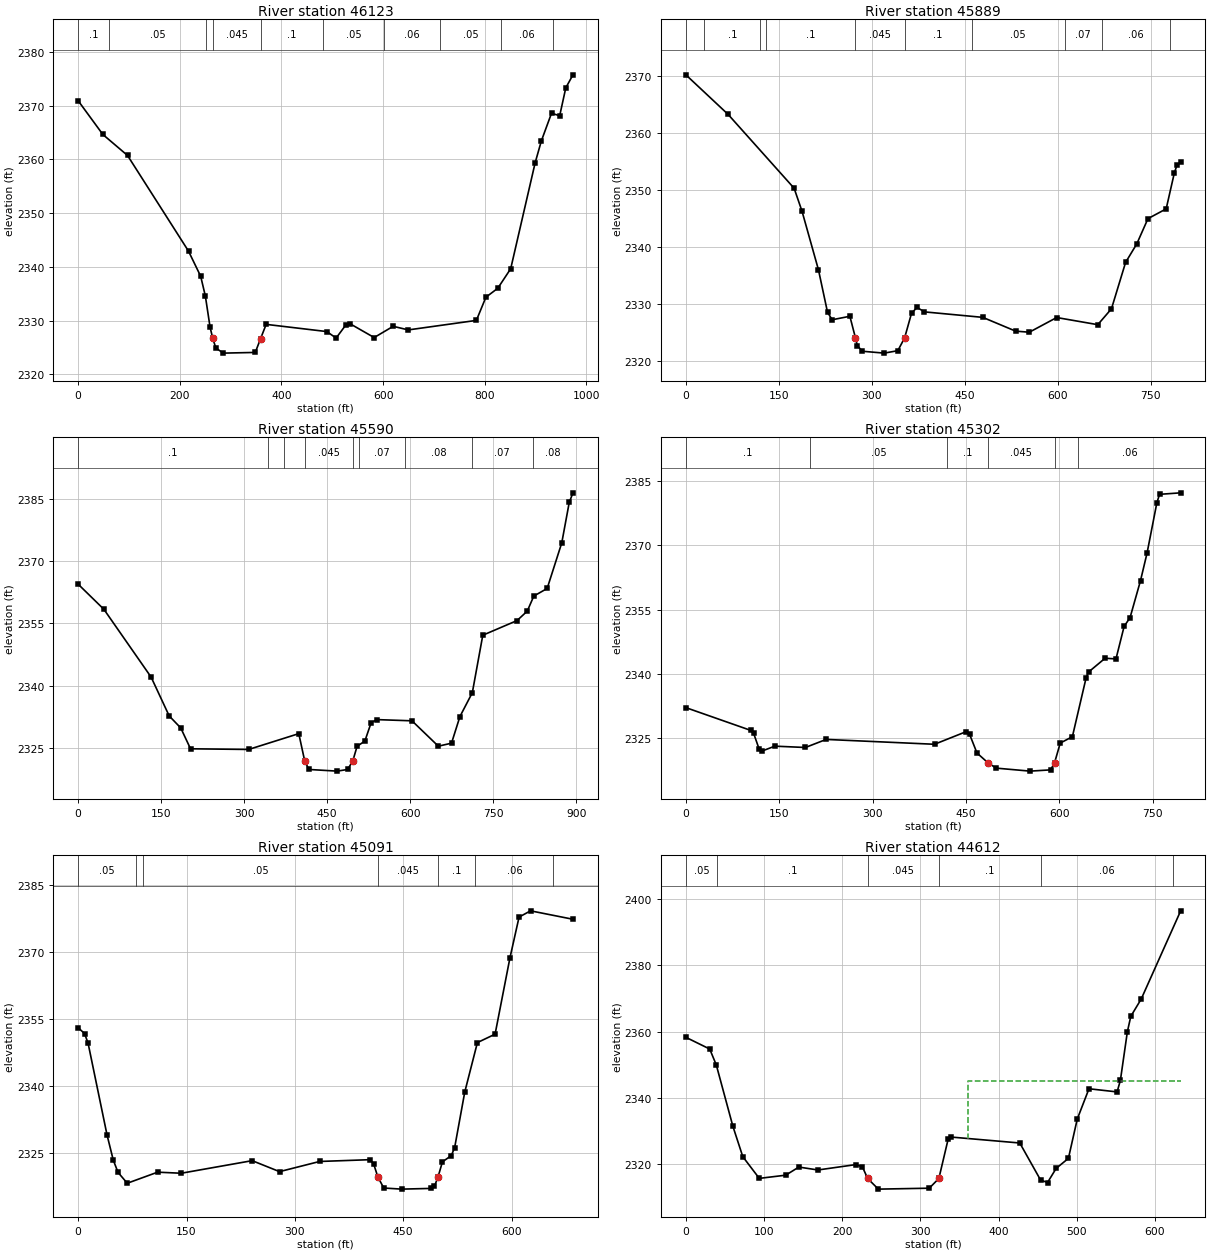
Type RM Length L Ch R = 1 ,46123   ,234,234,234
XS GIS Cut Line= 4
2387299.06265718704697.6505847742387541.35651458704697.650584774
 2388047.4380393704390.8752975852388186.17081249704377.197418538
#Sta/Elev= 30
       0 2370.93    48.6 2364.65    97.1 2360.75   217.1 2342.95   241.1 2338.26
   250.3 2334.57   259.6 2328.77  264.882326.697   270.9 2324.92   285.5 2323.97
   348.5  2324.1   358.9 2326.67   369.9 2329.32   489.3 2327.98   507.5 2326.77
   526.2 2329.15   535.6  2329.4   582.4 2326.87   619.8 2328.96   649.5 2328.29
   783.5 2330.06   802.2 2334.37   825.6 2336.04     851 2339.67   899.1 2359.38
   911.2 2363.42   931.3  2368.6   947.4 2368.14   959.4 2373.33973.5012 2375.75
#Mann= 10 ,-1,0
       0      .1       0      60     .05       0  252.29      .1       0
  264.88    .045       0   358.9      .1       0  482.29     .05       0
  602.29     .06       0  712.29     .05       0  832.29     .06       0
   934.1     .05       0
Bank Sta=264.88,358.9
XS Rating Curve= 0 ,0
Exp/Cntr(USF)=0,0
Exp/Cntr=0.3,0.1

Type RM Length L Ch R = 1 ,45889   ,298.2,298.2,298.2
XS GIS Cut Line= 3
2387421.82684255704958.8689907082387598.54033767704918.588708731
 2388157.2668296704656.117193919
#Sta/Elev= 30
       0 2370.14      68 2363.23   174.7 2350.29   187.5 2346.25     214 2336.01
   228.6 2328.59   236.1 2327.27   264.7 2327.88   273.7 2324.09   276.7 2322.76
   284.7 2321.76   320.1 2321.43   342.1 2321.86  353.08 2324.11   364.2 2328.41
   373.1 2329.43     385 2328.65   479.2 2327.69   532.2 2325.28   554.3 2325.09
   598.5 2327.66   664.8 2326.41   686.9 2329.19   709.7 2337.31   727.8 2340.56
   745.8 2344.97   775.2 2346.68   788.5 2353.03   792.9 2354.39   798.6 2354.81
#Mann= 10 ,-1,0
       0     .05       0      30      .1       0     120     .05       0
     130      .1       0   273.7    .045       0  353.08      .1       0
  461.25     .05       0  611.25     .07       0  671.25     .06       0
  781.25     .07       0
Bank Sta=273.7,353.08
XS Rating Curve= 0 ,0
Exp/Cntr(USF)=0,0
Exp/Cntr=0.3,0.1

Type RM Length L Ch R = 1 ,45590   ,288,288,288
XS GIS Cut Line= 5
2387547.47170619705283.7892126112387715.97483735705246.887581202
 2387894.3342889705110.174222332 2387995.9292141705008.058705593
 2388310.1775344704848.020765528
#Sta/Elev= 30
       0 2364.46    46.5 2358.41   131.8 2342.08   164.5 2332.72   185.3 2329.84
     203 2324.81     308 2324.65   398.6 2328.46  409.22 2321.91   416.8 2319.83
   467.9 2319.43   486.9 2319.83   496.2 2321.91   503.9  2325.4     518 2326.68
   529.3  2331.1   539.7 2331.84   603.1 2331.55   650.7 2325.44   674.5 2326.16
   689.7 2332.58   712.1 2338.33     731 2352.17   792.9  2355.7   811.3 2357.97
   823.2  2361.6   847.3 2363.43   873.7 2374.43   887.2 2384.17   893.9 2386.47
#Mann= 9 ,-1,0
       0      .1       0   342.5     .05       0   372.5      .1       0
  409.22    .045       0   496.2      .1       0  507.22     .07       0
  591.27     .08       0  711.27     .07       0  821.27     .08       0
Bank Sta=409.22,496.2
XS Rating Curve= 0 ,0
Exp/Cntr=0.3,0.1

Type RM Length L Ch R = 1 ,45302   ,211.4,211.4,211.4
XS GIS Cut Line= 2
2387664.80789834705459.1241055732388391.15233785705136.881849764
#Sta/Elev= 30
       0 2332.19   104.3 2326.88   108.7 2326.24   117.5  2322.6   122.2 2322.07
   142.9 2323.21   191.9  2322.9   225.3 2324.78   399.3 2323.65   449.6 2326.56
   455.7 2325.94   467.5 2321.61     485 2319.35   498.2 2318.09   552.7 2317.39
   585.7 2317.68   592.1 2319.35   601.2 2323.93   620.7 2325.42   642.6 2339.06
   646.6 2340.48   673.2  2343.7   690.7 2343.55   703.8 2351.13   713.3 2353.17
   730.1  2361.8   740.6 2368.21   756.4 2379.97   760.7 2381.91   794.6 2382.26
#Mann= 6 ,-1,0
       0      .1       0     200     .05       0     420      .1       0
     485    .045       0   592.1      .1       0     630     .06       0
Bank Sta=485,592.1
XS Rating Curve= 0 ,0
Exp/Cntr(USF)=0,0
Exp/Cntr=0.3,0.1

Type RM Length L Ch R = 1 ,45091   ,478.5,478.5,478.5
XS GIS Cut Line= 3
2387865.95459477705661.7155947752388360.76508702705363.118876026
2388465.74724815705342.009737066
#Sta/Elev= 30
       0 2353.05     8.8 2351.74    13.7 2349.61      40    2329    48.6 2323.38
    55.2 2320.62      68 2318.19     110 2320.67   142.7 2320.43   240.9 2323.25
   278.8 2320.79   334.3 2323.07   404.1 2323.47     409 2322.55  414.97 2319.57
   423.1 2317.12   447.8 2316.87   488.6 2317.03   493.1 2317.46  498.16 2319.57
   504.3 2322.99   516.5 2324.37   521.2 2326.16   535.2 2338.62   552.7 2349.71
   577.2  2351.6   597.7 2368.65   610.4 2377.84   626.3 2379.24     685 2377.35
#Mann= 7 ,-1,0
       0     .05       0      80      .1       0      90     .05       0
  414.97    .045       0  498.16      .1       0     550     .06       0
  657.93      .1       0
Bank Sta=414.97,498.16
XS Rating Curve= 0 ,0
Exp/Cntr=0.3,0.1

Type RM Length L Ch R = 1 ,44612   ,458.3,458.3,458.3
XS GIS Cut Line= 4
2388003.34686687 705911.624837412388136.80652385705865.877901454
2388394.99823155705913.442240099 2388601.6613516705814.062443971
#Sta/Elev= 30
       0 2358.28    30.5 2354.75    38.9 2349.96    60.1  2331.5    72.8 2322.32
    93.9 2315.78   127.7 2316.74   144.5 2319.19   168.9 2318.31   217.7 2319.94
   225.9 2319.21   232.52315.744   246.2 2312.54   311.3 2312.82   323.62315.748
   335.6 2327.73   339.7 2328.22   427.1 2326.44   453.7 2315.28   462.6 2314.53
   473.6 2318.78   489.3 2321.81   500.6 2333.63   515.6 2342.78   551.6 2341.83
   555.8 2345.34   564.7 2359.94   569.1  2364.6   582.5 2369.85   632.9 2396.39
#Mann= 6 ,-1,0
       0     .05       0      40      .1       0   232.5    .045       0
   323.6      .1       0  453.62     .06       0  623.62      .1       0
#XS Ineff= 2 , 0
                         361.337            2345
Permanent Ineff=
       F       F
Bank Sta=232.5,323.6
XS Rating Curve= 0 ,0
Exp/Cntr=0.3,0.1

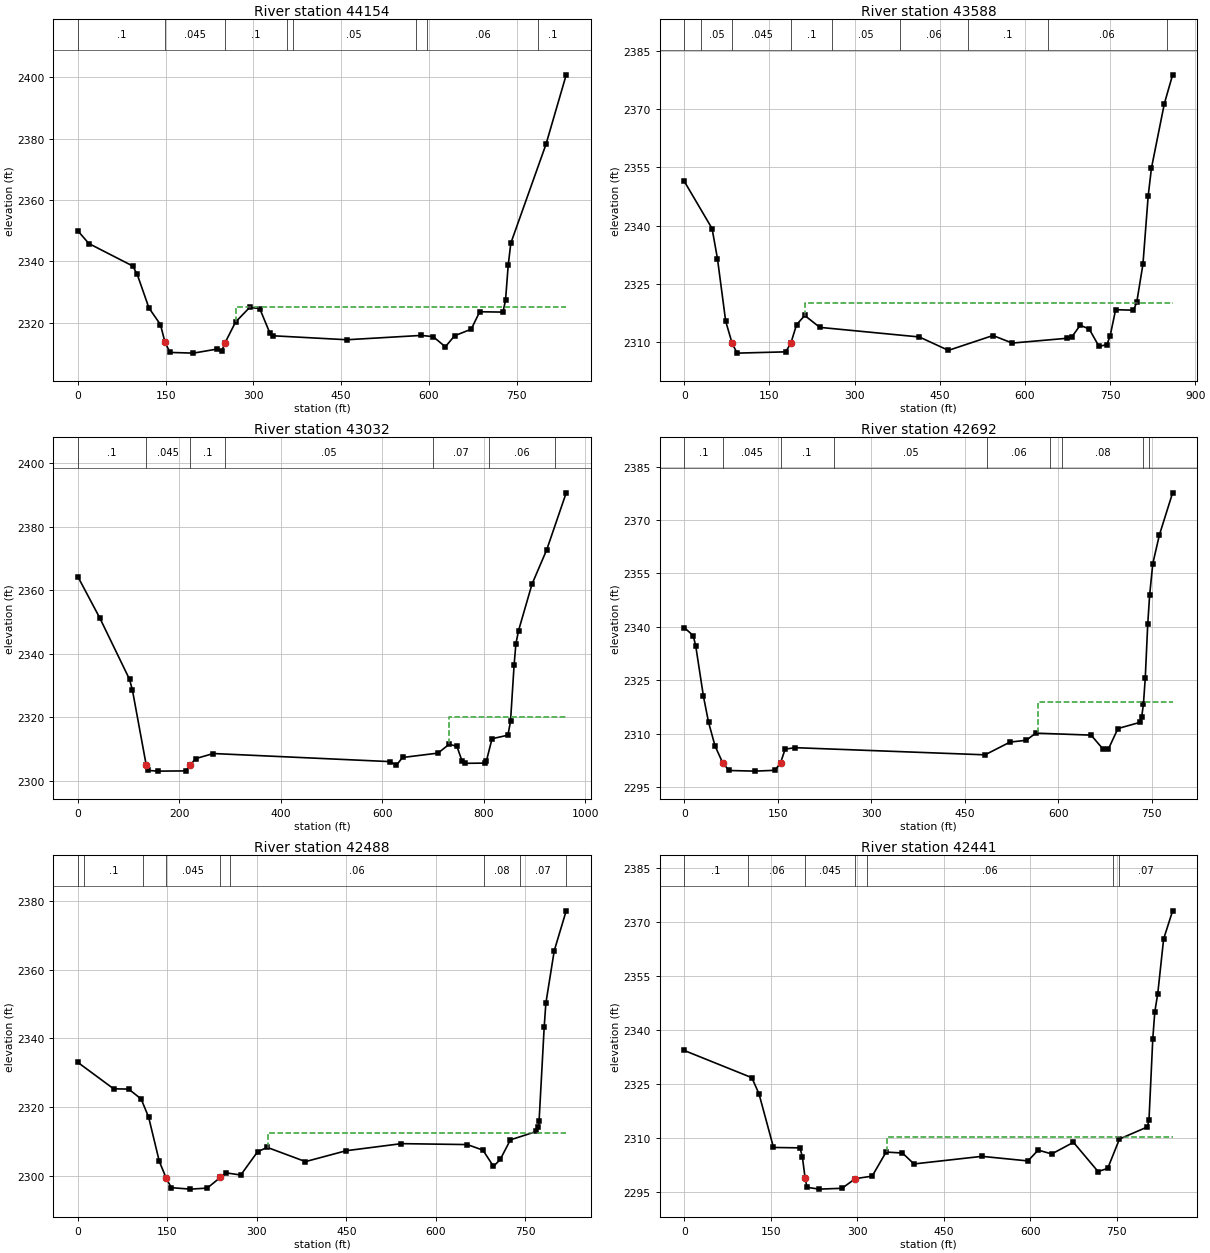
Type RM Length L Ch R = 1 ,44154   ,565.8,565.8,565.8
XS GIS Cut Line= 3
2387990.61915927  706342.72793982388287.87352191706338.671630543
2388773.86413629706108.879096742
#Sta/Elev= 30
       0 2349.93    18.8 2345.79    93.8 2338.47   101.6  2335.7   121.6 2324.78
   141.2 2319.39   149.1 2313.56   157.6 2310.31   197.6 2310.08   237.6 2311.39
   245.6 2310.62  251.85 2313.51   269.6  2320.2   293.6 2324.95   310.9 2324.62
   328.6 2316.48     333 2315.74   459.9 2314.44     587 2315.85   607.3 2315.46
   628.3 2312.14   644.1 2315.74   672.5 2317.88     687 2323.56   726.8 2323.45
   731.2 2327.37   735.7 2338.67   740.2  2345.9   800.3 2378.11   834.9 2400.76
#Mann= 8 ,-1,0
       0      .1       0   149.1    .045       0  251.85      .1       0
  357.28     .06       0  367.28     .05       0  577.28      .1       0
  597.28     .06       0  787.28      .1       0
#XS Ineff= 2 , 0
                           269.9            2325
Permanent Ineff=
       F       F
Bank Sta=149.1,251.85
XS Rating Curve= 0 ,0
Exp/Cntr=0.3,0.1

Type RM Length L Ch R = 1 ,43588   ,556.5,556.5,556.5
XS GIS Cut Line= 2
2388219.35586687706957.4208627032388935.76591996 706481.10483491
#Sta/Elev= 30
       0 2351.45      49 2339.28    58.5 2331.54      73 2315.42    84.4 2309.71
    93.1 2307.21   178.7 2307.54   187.6 2309.71   197.9 2314.55   212.3  2316.9
   238.8 2313.84   414.1 2311.37   465.3 2307.92   543.8 2311.74   577.8  2309.8
   673.5 2311.02   683.1 2311.45   697.5 2314.39   713.4 2313.41   730.7 2308.92
   744.6 2309.42   750.3 2311.69   759.9 2318.39   791.3 2318.26   797.1 2320.31
     808 2330.08   817.3 2347.76     823 2354.84   845.7 2371.43   860.3 2378.85
#Mann= 9 ,-1,0
       0      .1       0      30     .05       0    84.4    .045       0
   187.6      .1       0     260     .05       0     380     .06       0
     500      .1       0     640     .06       0     850      .1       0
#XS Ineff= 2 , 0
                        212.8638            2320
Permanent Ineff=
       F       F
Bank Sta=84.4,187.6
XS Rating Curve= 0 ,0
Exp/Cntr=0.3,0.1

Type RM Length L Ch R = 1 ,43032   ,339.9,339.9,339.9
XS GIS Cut Line= 2
2388511.29102779707456.0127270722389239.23875036  706825.9829915
#Sta/Elev= 30
       0 2364.31    43.5  2351.2   101.9 2331.92   107.6 2328.53  134.852304.848
   138.8 2303.19   157.1 2302.97   212.8 2303.04  221.49 2304.87   232.3 2306.92
   267.2 2308.52   615.6 2305.97   627.8 2304.79     640 2307.27     710 2308.65
   731.7 2311.41   747.1 2310.85   757.7 2306.02   762.3 2305.43   802.3  2305.5
   805.3 2306.12   816.5 2313.19   847.8 2314.31   852.9 2318.67     860 2336.48
   863.5 2343.12   868.7 2347.27   895.2 2361.92   924.3 2372.79   962.7 2390.74
#Mann= 7 ,-1,0
       0      .1       0  134.85    .045       0  221.49      .1       0
     290     .05       0     700     .07       0     810     .06       0
     940      .1       0
#XS Ineff= 2 , 0
                        731.8643            2320
Permanent Ineff=
       F       F
Bank Sta=134.85,221.49
XS Rating Curve= 0 ,0
Exp/Cntr=0.3,0.1

Type RM Length L Ch R = 1 ,42692   ,203.6,203.6,203.6
XS GIS Cut Line= 3
2388915.52787093707623.2809920552389015.18098969707168.003018074
2389265.29077798 706972.60474598
#Sta/Elev= 30
       0 2339.77    14.4 2337.51    18.5 2334.52    30.8 2320.44      39 2313.15
    49.3 2306.56   61.64 2301.75    71.8 2299.61   113.2 2299.43   145.5 2299.66
  154.51 2301.75   161.8 2305.62   178.2 2306.02   482.5 2304.01   522.6 2307.59
   548.6  2308.1   563.8  2310.1   652.6 2309.55   672.1 2305.56   680.5 2305.69
   695.7  2311.4   730.5 2313.11   733.8 2314.66   736.6 2318.35   739.5 2325.58
   743.5 2340.79   746.5 2348.85   751.6 2357.77   762.3 2365.88   783.4 2377.64
#Mann= 9 ,-1,0
       0      .1       0   61.64    .045       0  154.51      .1       0
     240     .05       0  486.06     .06       0  586.06     .05       0
  606.06     .08       0  736.06     .07       0  746.06      .1       0
#XS Ineff= 2 , 0
                          567.22         2318.76
Permanent Ineff=
       F       F
Bank Sta=61.64,154.51
XS Rating Curve= 0 ,0
Exp/Cntr(USF)=0,0
Exp/Cntr=0.3,0.1

Type RM Length L Ch R = 1 ,42488   ,47.2,47.2,47.2
XS GIS Cut Line= 4
2389022.85999576707656.971595195 2389142.9925254707619.987410373
2389105.80665358707176.7044817472389276.18560696706996.912204788
#Sta/Elev= 30
       0 2332.97      60 2325.28    85.1  2325.2     106 2322.34   118.6 2317.03
   136.5 2304.15   147.6 2299.46   156.6  2296.5   188.7 2296.08   216.8 2296.38
  238.73 2299.49   248.9  2300.8     273 2300.19   301.1 2306.95   317.2 2308.24
   381.4 2304.09   449.6 2307.26   542.2 2309.32   652.5 2309.05   678.7 2307.43
   696.4 2302.69   707.7 2304.72   724.7 2310.42   768.3 2312.86   771.7  2314.1
   772.8 2315.99   781.3 2343.16   784.1 2350.16   798.2  2365.5   818.2 2377.09
#Mann= 9 ,-1,0
       0     .06       0      10      .1       0     110     .06       0
   147.6    .045       0  238.73     .07       0   255.7     .06       0
  680.54     .08       0  740.54     .07       0  818.23      .1       0
#XS Ineff= 2 , 0
                          318.41         2312.54
Permanent Ineff=
       F       F
Bank Sta=147.6,238.73
XS Rating Curve= 0 ,0
Exp/Cntr=0.3,0.1

Type RM Length L Ch R = 1 ,42441   ,294.3,294.3,294.3
XS GIS Cut Line= 4
2389025.73429913707688.3815956062389192.17615941707629.295230255
2389136.53227985707195.520972281 2389281.6294128707012.972712857
#Sta/Elev= 30
       0 2334.34   117.2 2326.78   129.7 2322.26   154.8 2307.38   200.9 2307.27
     205 2304.61   209.62298.922     213 2296.31   233.9  2295.8   273.5 2296.03
   296.92298.727   325.9  2299.4   350.1  2306.1   378.4 2305.84   398.5  2302.8
   516.3 2304.91   596.1 2303.64   613.9 2306.65   637.4 2305.58   675.1 2308.81
   717.8 2300.68   734.5 2301.57   754.9 2309.73   803.3 2313.08   806.1 2315.05
   812.7 2337.63   816.2 2345.12   821.3 2350.14   831.5 2365.34   847.1 2373.16
#Mann= 7 ,-1,0
       0      .1       0     110     .06       0   209.6    .045       0
   296.9     .07       0  316.62     .06       0  743.95     .08       0
  753.95     .07       0
#XS Ineff= 2 , 0
                          352.35         2310.33
Permanent Ineff=
       F       F
Bank Sta=209.6,296.9
XS Rating Curve= 0 ,0
Exp/Cntr=0.3,0.1

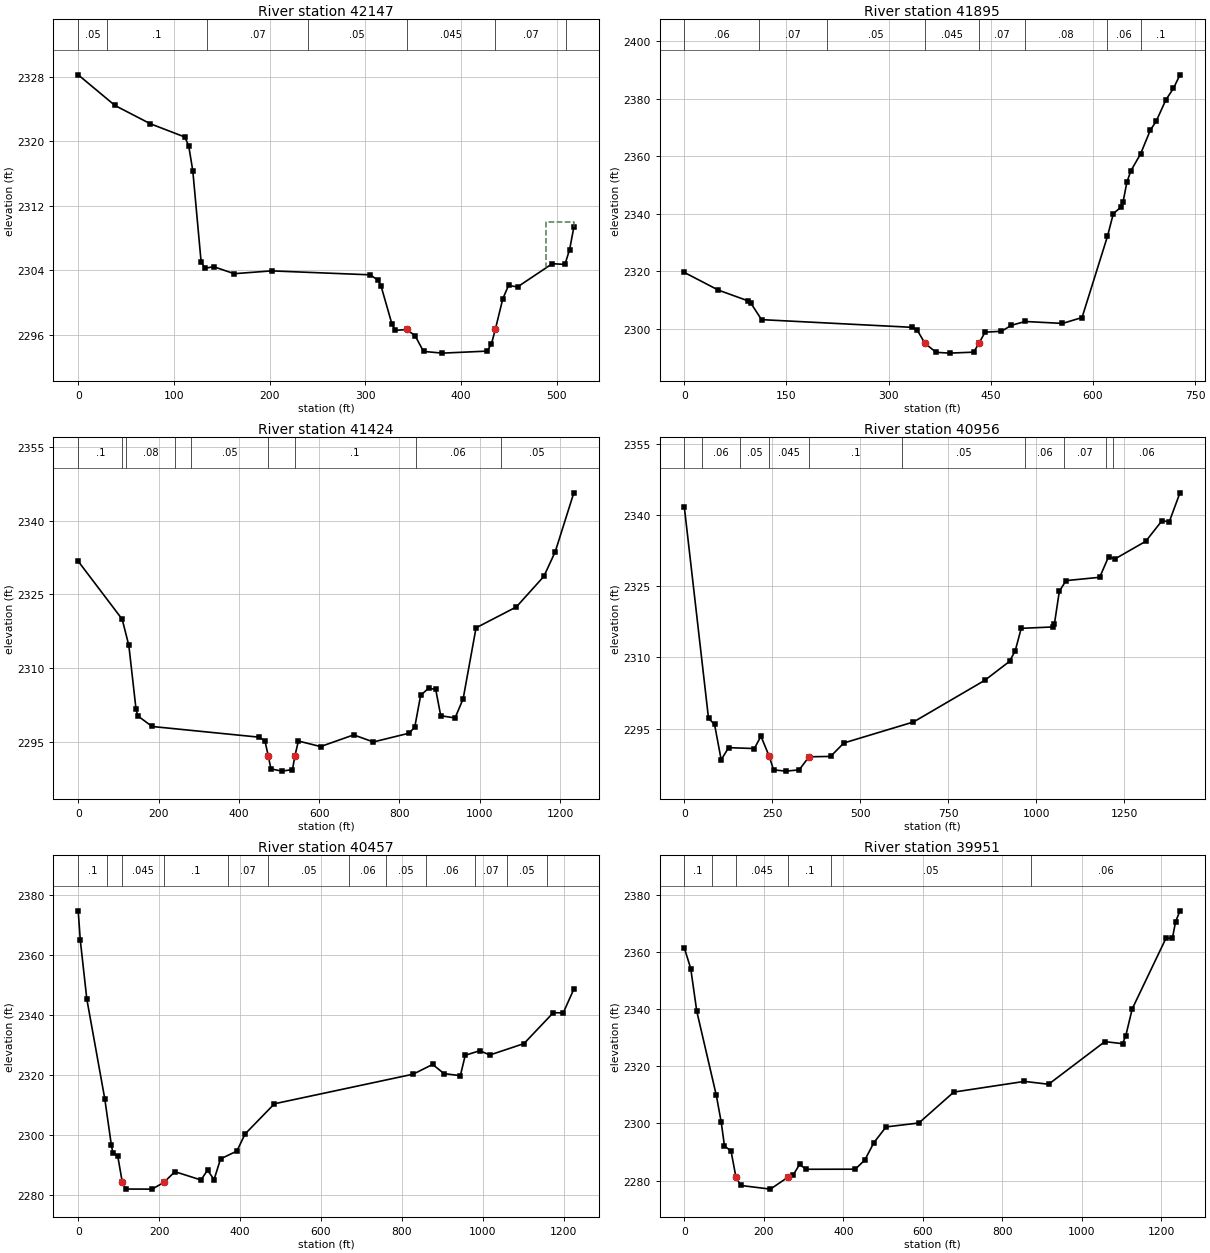
Type RM Length L Ch R = 1 ,42147   ,251.5,251.5,251.5
XS GIS Cut Line= 4
2389097.85388681707775.1163967132389202.45070165707767.820925328
2389317.69535384 707719.982772392389572.05139224707584.806491873
#Sta/Elev= 30
       0 2328.21    38.4 2324.41    75.2 2322.15   111.3  2320.5   115.4 2319.42
   119.7 2316.31   128.4    2305   132.6 2304.22   141.4 2304.42     163 2303.55
     202  2303.9   304.9 2303.41   313.4 2302.73   316.4 2301.99   327.6 2297.35
   331.1 2296.52     343 2296.63   351.9 2295.86   360.7 2293.91   380.5  2293.7
   427.2 2293.95   431.7 2294.87  435.67 2296.63   443.5 2300.44   449.5 2302.09
   458.9 2301.91   495.2 2304.79   508.4  2304.7   513.3 2306.55   517.7 2309.31
#Mann= 7 ,-1,0
       0     .05       0      30      .1       0  134.85     .07       0
  239.63     .05       0     343    .045       0  435.67     .07       0
  509.63     .06       0
#XS Ineff= 2 , 0
                           488.2            2310
Permanent Ineff=
       F       F
Bank Sta=343,435.67
XS Rating Curve= 0 ,0
Exp/Cntr(USF)=0,0
Exp/Cntr=0.3,0.1

Type RM Length L Ch R = 1 ,41895   ,471.1,471.1,471.1
XS GIS Cut Line= 3
2389118.82631394707866.9483038742389619.04589051707884.534148362
2389803.60024409707751.950777557
#Sta/Elev= 30
       0 2319.63    49.9  2313.5    93.4 2309.77    97.4 2309.07   113.4 2303.23
   333.6 2300.57   341.6 2299.75  353.222295.046   369.6 2291.88   389.6  2291.6
   424.9 2291.94  432.722295.046   441.6 2298.88   465.6 2299.18   480.3 2301.27
   500.5 2302.59   555.3 2301.92     584 2303.96   621.3 2332.14     630 2340.09
   641.3 2342.32   644.2 2344.07   649.9 2351.01   655.6 2354.88     670 2360.82
   684.3 2369.06   692.9 2372.16   707.2 2379.62   718.2 2383.55   727.8 2388.27
#Mann= 8 ,-1,0
       0     .06       0     110     .07       0     210     .05       0
  353.22    .045       0  432.72     .07       0     500     .08       0
  620.53     .06       0  670.53      .1       0
Bank Sta=353.22,432.72
XS Rating Curve= 0 ,0
Exp/Cntr=0.3,0.1

Type RM Length L Ch R = 1 ,41424   ,468.2,468.2,468.2
XS GIS Cut Line= 3
2388933.47828615708023.1909816222389652.22262953708534.751974609
2390002.42828195708498.825154011
#Sta/Elev= 30
       0 2331.77   109.5 2319.96   126.1 2314.62   143.9 2301.71   148.3 2300.28
   184.1 2298.12   450.8 2295.94   465.1 2295.16  473.182292.158   479.9 2289.49
     507 2289.03   533.6 2289.34   539.7 2292.16   548.3 2295.16   603.6 2294.03
     686 2296.41   734.9 2294.97   823.7 2296.75     838 2297.96   852.7 2304.45
   872.4 2305.91   890.2 2305.67   902.8 2300.31   938.5 2299.86   958.6 2303.77
   990.7 2318.21    1091 2322.46  1159.6 2328.69  1187.8 2333.69  1234.2  2345.7
#Mann= 9 ,-1,0
       0      .1       0     110     .06       0     120     .08       0
     240     .07       0     280     .05       0  473.18    .045       0
   539.7      .1       0     840     .06       0 1052.21     .05       0
Bank Sta=473.18,539.7
XS Rating Curve= 0 ,0
Exp/Cntr=0.3,0.1

Type RM Length L Ch R = 1 ,40956   ,499.1,499.1,499.1
XS GIS Cut Line= 3
2388787.51859561708563.8732173422388865.60328451708566.156741088
2389995.21202978709268.155804099
#Sta/Elev= 30
       0 2341.62    68.7  2297.2    85.9 2295.91   104.7 2288.47   125.7 2291.03
   198.9 2290.84   217.7 2293.44   241.3 2289.17   253.5 2286.35   288.4 2286.09
   326.2 2286.35   354.3 2289.11   415.5 2289.18   453.2 2292.01     651 2296.43
   853.5 2305.19   924.1 2309.19   940.2 2311.45   957.1 2316.13  1046.6 2316.42
  1051.3 2316.99  1065.4 2323.93  1084.4 2326.17  1180.1 2326.87  1205.4 2331.22
  1223.6 2330.74  1310.8 2334.44  1357.2 2338.79  1377.6 2338.52  1408.1 2344.64
#Mann= 10 ,-1,0
       0      .1       0      50     .06       0  158.12     .05       0
   241.3    .045       0   354.3      .1       0  618.12     .05       0
  968.12     .06       0 1078.12     .07       0 1198.12     .05       0
 1218.12     .06       0
Bank Sta=241.3,354.3
XS Rating Curve= 0 ,0
Exp/Cntr=0.3,0.1

Type RM Length L Ch R = 1 ,40457   ,505.9,505.9,505.9
XS GIS Cut Line= 2
2388763.03324597709142.6555678152389978.50961335709296.264419553
#Sta/Elev= 30
       0 2374.86     5.2 2365.03    21.3 2345.45    65.7 2312.19      82 2296.74
    85.8 2294.11    97.9 2293.01  109.082284.316   118.1 2282.12   182.6 2282.09
  211.662284.318     239 2287.91   303.5 2285.14   319.7 2288.43   335.8 2285.26
   351.9 2292.17   392.2 2294.77   412.4 2300.46     485 2310.54   827.7  2320.4
   876.1 2323.65   904.3  2320.6   944.6 2319.91   956.7 2326.71     993 2328.24
  1017.2 2326.79  1101.8  2330.6  1174.4 2340.92  1198.8 2340.82  1225.1 2348.75
#Mann= 12 ,-1,0
       0      .1       0      70     .06       0  109.08    .045       0
  211.66      .1       0     370     .07       0     470     .05       0
     670     .06       0     760     .05       0     860     .06       0
     980     .07       0    1060     .05       0    1160     .06       0
Bank Sta=109.08,211.66
XS Rating Curve= 0 ,0
Exp/Cntr=0.3,0.1

Type RM Length L Ch R = 1 ,39951   ,419.2,419.2,419.2
XS GIS Cut Line= 3
2388665.70743463709620.2948621472389183.38455682709739.100122186
2389890.99077545709634.209928124
#Sta/Elev= 30
       0 2361.38    16.1  2354.2    31.3 2339.23    80.5 2309.78    92.8 2300.39
     101 2292.08   117.4 2290.37   129.9 2281.12   142.1 2278.28   216.4    2277
   259.8 2281.09   273.4 2281.85   289.8 2285.65   306.2 2283.95   430.1 2283.98
     454 2287.21   476.8 2293.28   507.3 2298.77   589.9 2300.14   677.5 2310.95
   855.4  2314.7   916.1  2313.7  1057.6 2328.62  1102.1  2327.9  1110.2 2330.66
  1126.4 2340.07  1211.3  2364.8  1227.5 2364.83  1235.5 2370.57  1246.5 2374.39
#Mann= 6 ,-1,0
       0      .1       0      70     .06       0   129.9    .045       0
   259.8      .1       0     370     .05       0  871.13     .06       0
Bank Sta=129.9,259.8
XS Rating Curve= 0 ,0
Exp/Cntr=0.3,0.1