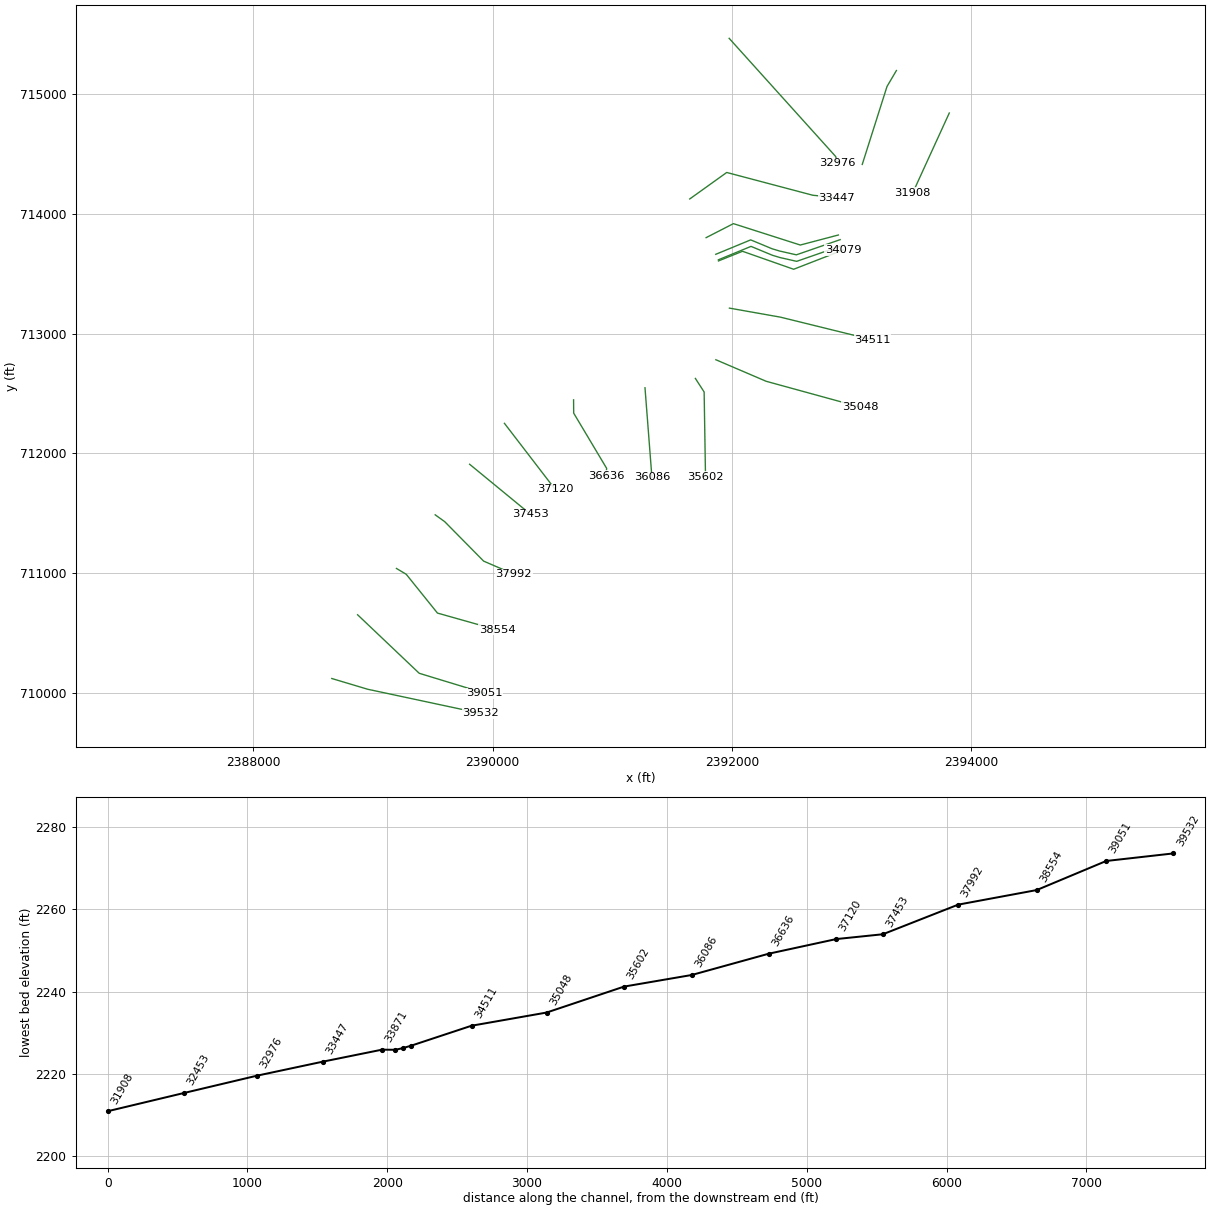
HEC-RAS study DRKFK_2.prj: DRKFK_2

--- DRKFK_2.g01 (geometry) --- (continued)

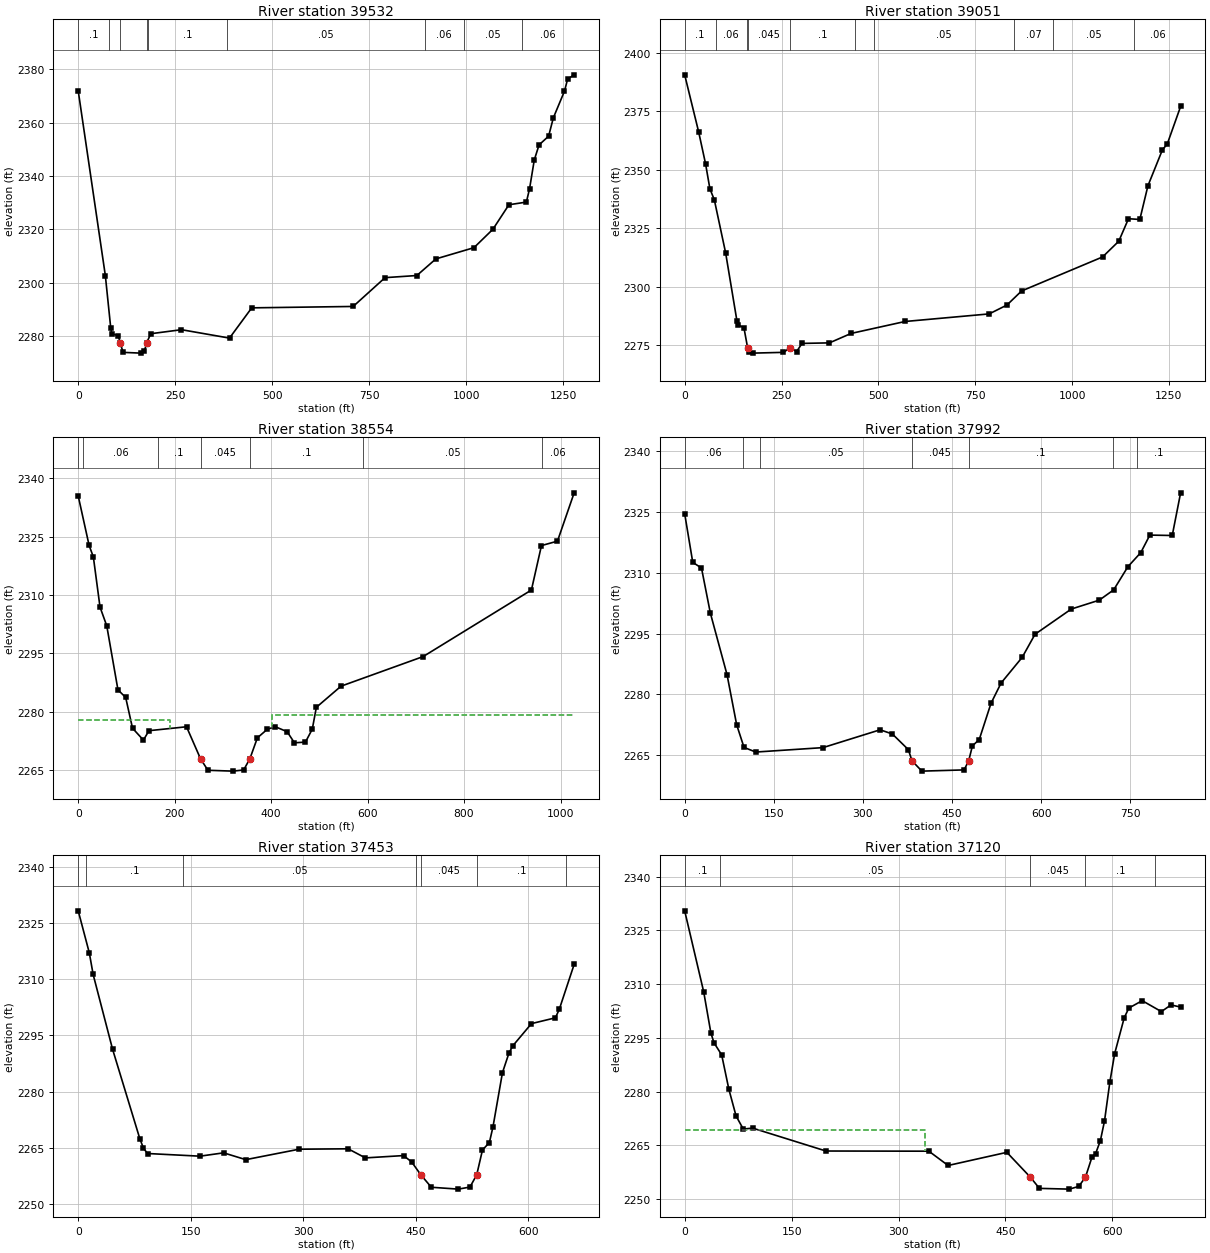
Type RM Length L Ch R = 1 ,39532   ,481,481,481
XS GIS Cut Line= 3
2388657.23509256710117.1977433812388957.04635431710027.431097695
2389900.58294958 709825.73941356
#Sta/Elev= 30
       0 2371.98    69.9 2302.67    83.7 2283.17    86.6 2280.82   103.3  2280.1
  107.792277.488   115.8 2273.84   161.7 2273.56   170.1 2274.21  176.742277.489
   186.8 2280.84   266.1 2282.35   389.8  2279.2   447.1 2290.55   708.4 2291.07
   790.6 2301.88   872.5 2302.68   921.5 2308.91  1019.7 2313.13  1068.5 2320.04
  1109.7 2329.23  1154.7 2330.23  1162.9 2335.23  1175.1 2346.06  1187.4 2351.69
    1212 2354.97  1224.2 2361.85  1252.9 2371.87    1261  2376.4  1277.8 2377.98
#Mann= 9 ,-1,0
       0      .1       0      80     .06       0  107.79    .045       0
  176.74     .06       0     180      .1       0  382.96     .05       0
  892.96     .06       0  992.96     .05       0 1142.96     .06       0
Bank Sta=107.79,176.74
XS Rating Curve= 0 ,0
Exp/Cntr=0.3,0.1

Type RM Length L Ch R = 1 ,39051   ,496.9,496.9,496.9
XS GIS Cut Line= 3
 2388872.7410262710650.0512634612389387.65396867 710160.84567702
2389932.89615721709994.610647397
#Sta/Elev= 30
       0 2390.57    36.1 2366.18      54  2352.5    65.1 2341.89    76.5 2337.22
   105.8 2314.47   134.8 2285.59   138.9  2283.7     153 2282.54  162.362274.116
   167.1 2272.05   175.5 2271.72   254.9 2272.05   272.9 2274.06   288.8 2272.35
     303 2275.87   373.7  2276.1   429.6 2280.13   568.9 2285.23   786.1 2288.47
   831.9 2292.25   869.7 2298.26  1078.8 2312.79  1120.6  2319.5  1145.7 2329.12
    1175  2328.8  1195.9 2343.18  1233.5 2358.63  1245.6 2360.92  1280.3 2377.07
#Mann= 10 ,-1,0
       0      .1       0      80     .06       0     160      .1       0
  162.36    .045       0   272.9      .1       0     440     .06       0
     490     .05       0  850.25     .07       0  950.25     .05       0
 1160.25     .06       0
Bank Sta=162.36,272.9
XS Rating Curve= 0 ,0
Exp/Cntr=0.3,0.1

Type RM Length L Ch R = 1 ,38554   ,561.8,561.8,561.8
XS GIS Cut Line= 4
2389197.36980803711037.3636055282389279.06808497 710988.63969115
2389539.86750612710664.313907437 2390037.4723526710523.925931929
#Sta/Elev= 30
       0  2335.5    22.6 2322.77    31.4  2319.8    45.2  2306.9    59.2 2302.06
    82.4 2285.59    98.4 2283.63   112.6 2275.71   135.2 2272.65   146.7 2275.07
   224.6 2276.08  253.582267.846   268.9 2264.88   320.3 2264.66     343 2264.95
  355.932267.845   371.5 2273.23   392.1 2275.44   408.5  2276.1   433.2 2274.81
   448.3 2271.95   471.1 2272.13   485.3 2275.46   493.8 2281.09   544.9 2286.53
   715.3 2294.16   939.7 2311.29   960.5 2322.73   993.7 2323.87  1028.3 2336.31
#Mann= 7 ,-1,0
       0      .1       0      10     .06       0  165.12      .1       0
  253.58    .045       0  355.93      .1       0   591.3     .05       0
   961.3     .06       0
#XS Ineff= 2 , 0
          189.75 2277.75   402.8            2279
Permanent Ineff=
       F       F
Bank Sta=253.58,355.93
XS Rating Curve= 0 ,0
Exp/Cntr=0.3,0.1

Type RM Length L Ch R = 1 ,37992   ,538.8,538.8,538.8
XS GIS Cut Line= 4
2389521.08739789711485.5550697822389600.36146377711428.637520252
2389925.89749217711098.5081936792390177.18316406710990.020094274
#Sta/Elev= 30
       0 2324.53    13.6 2312.54    28.3 2311.15    43.2 2300.06    71.3 2284.88
    87.5 2272.55    99.9 2266.96   119.7 2265.82   232.8 2266.91     329  2271.3
   349.6 2270.27   376.5 2266.42   382.72263.662   399.3 2261.12   470.4 2261.42
  478.11 2263.66   484.4 2267.34   495.9 2268.91   515.7 2277.83   532.7 2282.83
   568.1 2289.13   589.8 2294.83   650.8 2301.04   697.9 2303.23   722.2 2305.77
   746.2 2311.48   767.9 2314.96   783.1 2319.26   820.8 2319.16   834.9 2329.67
#Mann= 7 ,-1,0
       0     .06       0   97.59      .1       0  127.59     .05       0
   382.7    .045       0  478.11      .1       0  721.23     .06       0
  761.23      .1       0
Bank Sta=382.7,478.11
XS Rating Curve= 0 ,0
Exp/Cntr=0.3,0.1

Type RM Length L Ch R = 1 ,37453   ,333.6,333.6,333.6
XS GIS Cut Line= 2
2389808.77047992711908.2418900592390319.50418143711488.458038448
#Sta/Elev= 30
       0 2328.25    14.8 2317.02    19.9 2311.26    45.8 2291.29    82.1 2267.41
      87 2264.85    92.4 2263.44   162.3 2262.73   193.8 2263.62   223.4  2261.8
   294.4 2264.59   359.8  2264.7   382.8 2262.27   433.7 2262.89   444.5 2261.18
  456.742257.748   470.7 2254.43   506.6 2253.93   522.2 2254.48  531.22 2257.75
   538.9 2264.39   548.1 2266.37   552.9 2270.56   565.5 2285.02     574 2290.15
   579.1 2292.15   604.2 2298.13   636.1 2299.68   641.3 2301.96   661.1 2313.95
#Mann= 7 ,-1,0
       0     .06       0      10      .1       0     140     .05       0
     450      .1       0  456.74    .045       0  531.22      .1       0
     650     .07       0
Bank Sta=456.74,531.22
XS Rating Curve= 0 ,0
Exp/Cntr=0.3,0.1

Type RM Length L Ch R = 1 ,37120   ,483.5,483.5,483.5
XS GIS Cut Line= 2
2390099.56723555712250.3718778142390523.28094931711698.422176301
#Sta/Elev= 30
       0 2330.45    26.7 2307.82    36.8 2296.32    41.2 2293.59    51.9 2290.24
      62 2280.63    72.1 2273.18    82.2 2269.53    95.4 2269.79   198.2  2263.4
   342.6 2263.35   369.6 2259.36     452 2263.03  485.062256.079   497.7 2252.97
   539.6 2252.76   552.8 2253.51  562.25 2256.08   571.3 2261.62   576.4 2262.61
   583.2 2266.28     589 2271.76   596.5 2282.62   603.2 2290.54   616.7 2300.62
   623.2 2303.31   641.9 2305.37   668.8 2302.32   682.3 2304.18   695.8 2303.58
#Mann= 5 ,-1,0
       0      .1       0      50     .05       0  485.06    .045       0
  562.25      .1       0     660     .07       0
#XS Ineff= 2 , 0
          336.61 2269.14
Permanent Ineff=
       F       F
Bank Sta=485.06,562.25
XS Rating Curve= 0 ,0
Exp/Cntr=0.3,0.1

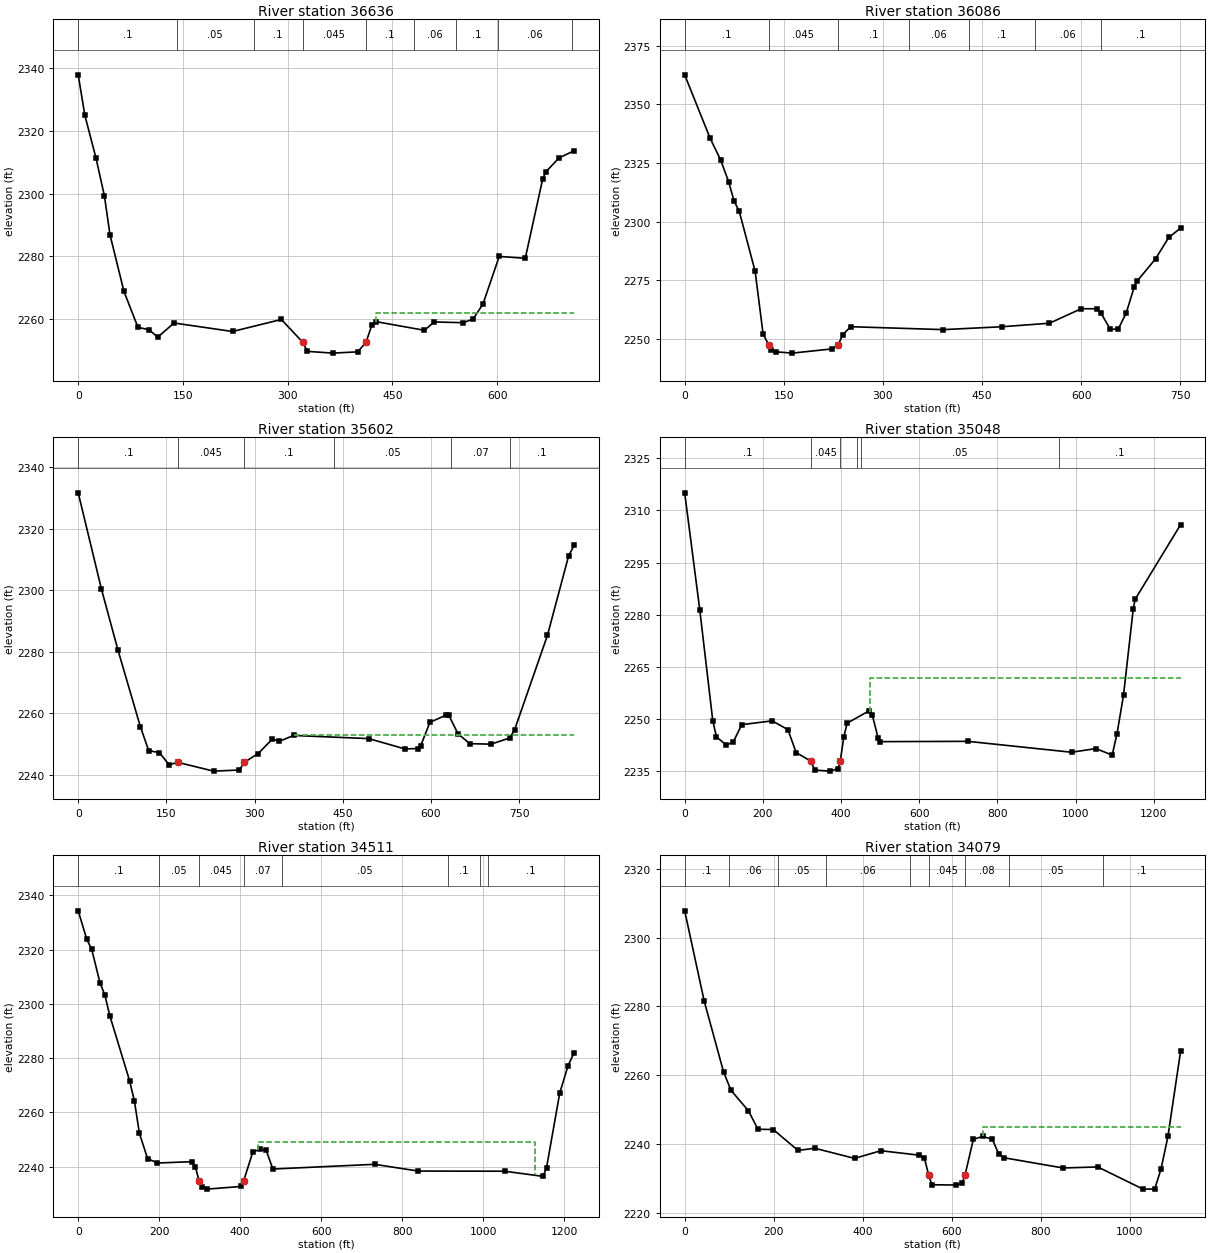
Type RM Length L Ch R = 1 ,36636   ,549.8,549.8,549.8
XS GIS Cut Line= 4
2390677.09213785712446.6556735992390678.19787247712335.539520525
2390953.11446596711874.6419091472390950.57701738711812.265917972
#Sta/Elev= 30
       0 2337.84     9.5 2324.95    25.5 2311.31    37.5  2299.3    45.5  2286.9
    65.5 2268.85    85.5 2257.44   101.5 2256.63   113.9 2254.29   137.2  2258.8
     221 2256.09   290.9 2259.92   321.4  2252.7   328.1 2249.76   364.8  2249.2
   400.2 2249.61     412 2252.59   420.6 2258.17   425.9 2259.25   495.8 2256.47
   509.8 2259.13   551.7 2258.89   565.7  2260.1   579.6 2264.83   602.9 2280.01
   640.2  2279.4     665 2304.54   669.3 2306.84   688.6  2311.4   710.2 2313.65
#Mann= 9 ,-1,0
       0      .1       0  141.12     .05       0  251.12      .1       0
   321.4    .045       0     412      .1       0  481.12     .06       0
  541.12      .1       0  601.12     .06       0  707.78      .1       0
#XS Ineff= 2 , 0
                           426.4            2262
Permanent Ineff=
       F       F
Bank Sta=321.4,412
XS Rating Curve= 0 ,0
Exp/Cntr=0.3,0.1

Type RM Length L Ch R = 1 ,36086   ,484.4,484.4,484.4
XS GIS Cut Line= 2
2391273.85870178712547.5094857062391331.71027768711799.254360099
#Sta/Elev= 30
       0 2362.64    38.4 2335.68    54.5 2326.29    66.5 2317.11    74.6 2308.92
    82.6 2304.44   106.6 2278.91   118.7 2252.13  127.222247.529   130.7  2245.5
   138.7 2244.59   162.8 2244.04     223 2245.84  232.152247.529     239  2251.8
   251.1  2255.3   391.5 2254.06   479.8 2255.28     552 2256.78   600.1 2262.97
   624.2 2262.93     630 2261.11   644.2 2254.12   656.3 2254.41   668.3 2261.23
   680.4 2272.37   684.4 2274.63   712.5 2284.22   732.5 2293.32   750.5 2297.33
#Mann= 7 ,-1,0
       0      .1       0  127.22    .045       0  232.15      .1       0
     340     .06       0     430      .1       0     530     .06       0
     630      .1       0
Bank Sta=127.22,232.15
XS Rating Curve= 0 ,0
Exp/Cntr=0.3,0.1

Type RM Length L Ch R = 1 ,35602   ,553.9,553.9,553.9
XS GIS Cut Line= 3
 2391694.7121227712625.901875255 2391767.9439966712512.510094015
2391779.47793104711803.764977766
#Sta/Elev= 30
       0 2331.73    39.6 2300.36    67.5 2280.69   105.7  2255.7   119.9 2247.91
   138.3 2247.21   154.3 2243.37   170.3 2244.03   230.3 2241.22   274.3 2241.58
  282.55 2244.08   306.3 2246.95   330.3 2251.64   342.3 2250.91   366.3 2252.82
   494.4  2251.8   555.8 2248.44   578.4 2248.57   582.4 2249.33   598.4  2257.1
   626.4 2259.47   630.4 2259.44   646.3 2253.32   666.4 2250.15   702.4 2249.99
   734.4 2252.02   742.4 2254.64   798.4  2285.4   834.4 2311.24   843.8 2314.68
#Mann= 6 ,-1,0
       0      .1       0   170.3    .045       0  282.55      .1       0
  434.98     .05       0  634.98     .07       0  734.98      .1       0
#XS Ineff= 2 , 0
                           366.3            2253
Permanent Ineff=
       F       F
Bank Sta=170.3,282.55
XS Rating Curve= 0 ,0
Exp/Cntr=0.3,0.1

Type RM Length L Ch R = 1 ,35048   ,536.9,536.9,536.9
XS GIS Cut Line= 3
2391866.08500621712781.9832473062392286.06549412712601.948198085
2393069.01394331712386.978340473
#Sta/Elev= 30
       0 2315.08    38.8 2281.21    71.9 2249.43    81.4 2244.75   106.7 2242.45
   124.1 2243.25   145.9 2248.31   224.2  2249.4   264.2 2246.85   285.2 2240.27
  322.31 2237.82     333 2235.22   372.2 2234.92   392.1 2235.64   398.2 2237.86
     407 2244.71   415.7 2248.75   472.3 2252.31   479.9 2251.13   495.1 2244.41
   500.6 2243.41   724.6  2243.5   989.8 2240.36  1052.3 2241.41  1093.8 2239.53
  1106.2 2245.73  1122.8 2256.79  1147.7 2281.65  1152.5 2284.41  1268.9 2305.91
#Mann= 6 ,-1,0
       0      .1       0  322.31    .045       0   398.2      .1       0
     440     .07       0     450     .05       0  956.94      .1       0
#XS Ineff= 2 , 0
                          475.09         2261.86
Permanent Ineff=
       F       F
Bank Sta=322.31,398.2
XS Rating Curve= 0 ,0
Exp/Cntr=0.3,0.1

Type RM Length L Ch R = 1 ,34511   ,432.2,432.2,432.2
XS GIS Cut Line= 3
2391979.36137795713213.6057429992392405.73937093713138.033164668
2393174.76993302712948.490688134
#Sta/Elev= 30
       0 2334.29    21.1 2323.81    33.3 2320.15    53.6 2307.85    65.8 2303.23
      78 2295.66   126.8 2271.73   138.9 2264.12   151.1 2252.32   171.4 2242.96
   195.8 2241.34   281.1 2241.84   289.3 2239.99  298.92 2234.59   305.5 2232.35
   317.7 2231.72     403 2232.71   408.3 2234.61   431.4 2245.43   447.9 2246.36
   464.4    2246   480.8 2239.13   732.2 2240.86   839.8 2238.38  1053.5 2238.32
  1148.2 2236.42  1156.9 2239.64  1189.4 2267.06    1210 2277.23  1225.1 2282.05
#Mann= 8 ,-1,0
       0      .1       0     200     .05       0  298.92    .045       0
   408.3     .07       0  503.02     .05       0  913.02      .1       0
  993.02     .08       0 1013.02      .1       0
#XS Ineff= 1 ,-1
444.6229  1128.3    2249
Permanent Ineff=
       F
Bank Sta=298.92,408.3
XS Rating Curve= 0 ,0
Exp/Cntr=0.3,0.1

Type RM Length L Ch R = 1 ,34079   ,59.8,59.8,59.8
XS GIS Cut Line= 4
2391887.44818693713608.0677645822392088.45438944713688.786790784
2392515.79041051713538.4278204072392930.46462355713699.865872812
#Sta/Elev= 30
       0 2307.79    43.9 2281.52    87.5 2260.91   104.2 2255.57   143.4 2249.64
   164.6 2244.28   199.1  2244.2   254.5 2238.13   292.6 2238.75   381.7 2235.81
   441.1 2238.04   525.9 2236.76   538.6 2235.96  548.33 2230.99   555.5 2228.14
   610.7 2228.06   623.4 2228.56   630.1 2230.97   648.8 2241.36     670 2242.19
   691.5 2241.35     706 2237.04   717.3    2236   850.3 2233.02   928.5 2233.32
    1030 2226.87  1056.4  2226.9  1070.6 2232.74  1086.1 2242.191114.615 2267.02
#Mann= 9 ,-1,0
       0      .1       0     100     .06       0     210     .05       0
  316.61     .06       0  506.61     .05       0  548.33    .045       0
   630.1     .08       0  729.62     .05       0  939.62      .1       0
#XS Ineff= 2 , 0
                        669.9161            2245
Permanent Ineff=
       F       F
Bank Sta=548.33,630.1
XS Rating Curve= 0 ,0
Exp/Cntr(USF)=0,0
Exp/Cntr=0.3,0.1

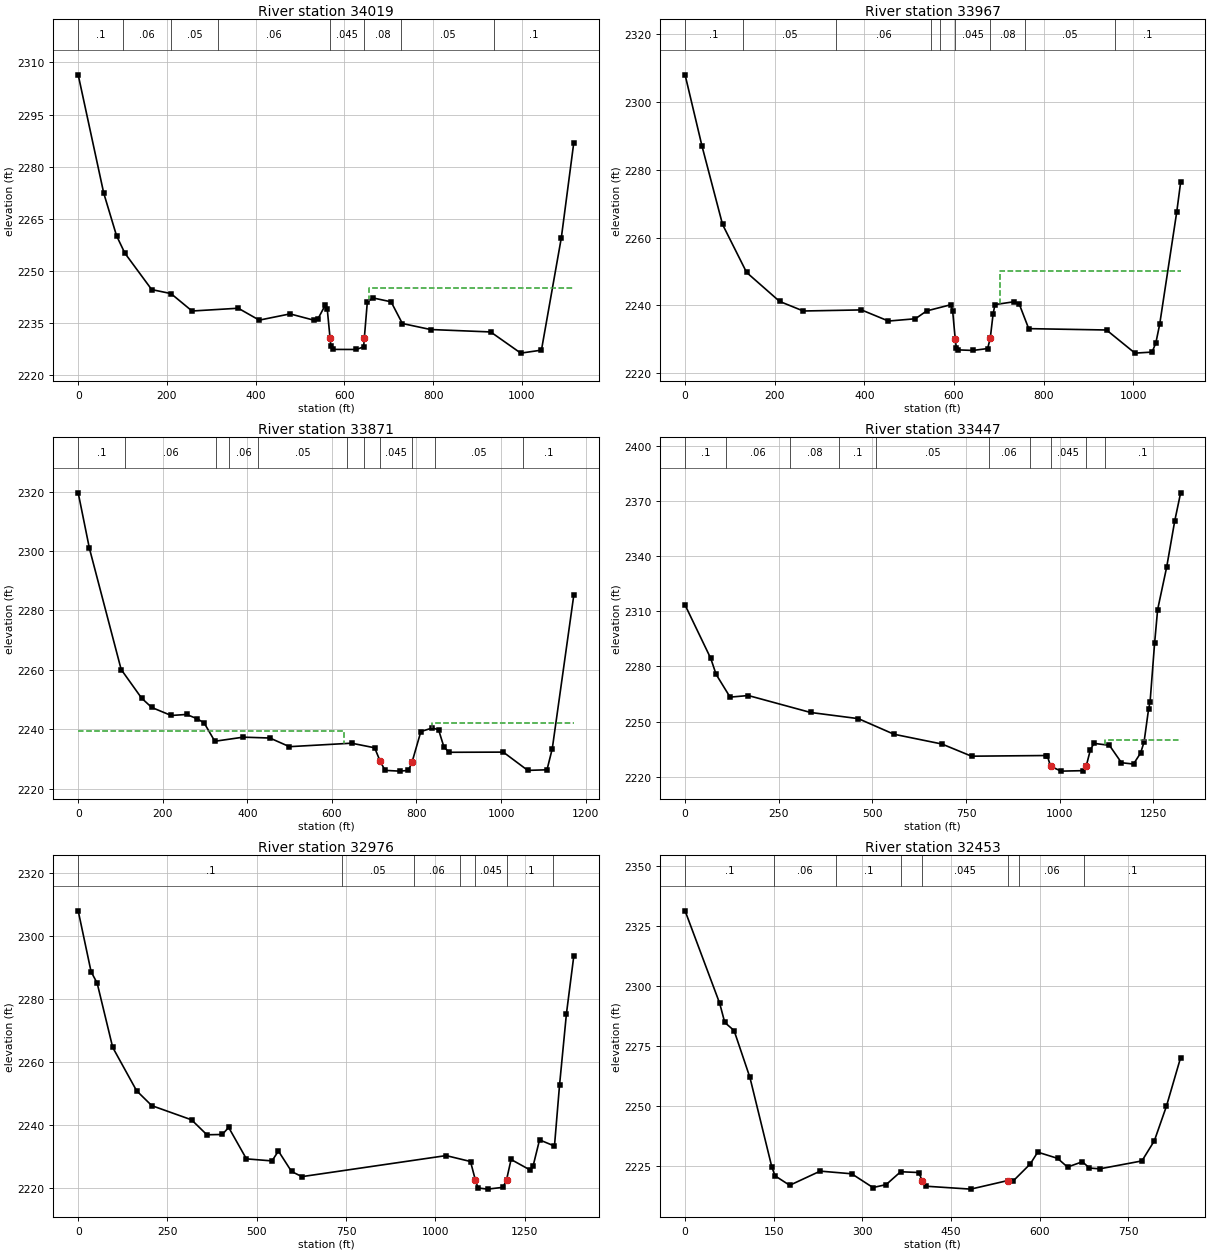
Type RM Length L Ch R = 1 ,34019   ,52.5,52.5,52.5
XS GIS Cut Line= 6
2391886.98042814713617.5799843472392159.64047209713729.718141691
2392338.48851054713655.3300195042392401.79755069713636.337307457
2392541.07743904713604.6827873772392936.95048054713742.376363152
#Sta/Elev= 30
       0 2306.43    57.5 2272.38    86.4 2260.09   105.1 2255.08   165.6 2244.58
     209 2243.43   256.5 2238.41   360.7 2239.21   407.9 2235.78   477.4 2237.58
   532.1 2235.73   540.4  2236.2   557.1 2240.19   561.2 2238.96  567.48  2230.6
   569.4 2228.32   573.5 2227.35   626.8 2227.33   643.2  2228.1   644.7  2230.6
   651.4 2240.92   663.7 2242.19     705 2241.06   730.4 2234.81   793.9 2233.08
   929.4 2232.38   997.2 2226.28  1043.8 2227.14  1088.6 2259.51  1116.6 2286.83
#Mann= 8 ,-1,0
       0      .1       0     100     .06       0     210     .05       0
  314.82     .06       0  567.48    .045       0   644.7     .08       0
  727.47     .05       0  937.47      .1       0
#XS Ineff= 2 , 0
                           654.7            2245
Permanent Ineff=
       F       F
Bank Sta=567.48,644.7
XS Rating Curve= 0 ,0
Exp/Cntr=0.3,0.1

Type RM Length L Ch R = 1 ,33967   ,95.5,95.5,95.5
XS GIS Cut Line= 6
 2391865.2293236713663.6163153432392157.02842973 713784.12781239
2392335.87646818713709.7396902032392399.18550833713690.746978156
2392538.46539668713659.0924580762392904.43365353713786.020311375
#Sta/Elev= 30
       0 2308.05    37.8 2286.99    83.6 2263.87   137.3  2249.7   210.9 2241.15
   263.8 2238.32   393.5 2238.64   453.8 2235.35   513.9 2236.03     539 2238.34
   592.9 2240.17     597 2238.37  602.64 2230.17   605.3 2227.38   609.4 2226.84
   642.2 2226.67     675 2227.23   680.9 2230.24   687.3 2237.48   691.4 2240.21
   733.9 2241.05   745.6 2240.37   766.7 2233.11   940.3 2232.71  1003.8 2225.88
    1042 2226.19  1050.4  2228.9  1058.9 2234.36    1097 2267.55  1105.7 2276.32
#Mann= 9 ,-1,0
       0      .1       0     130     .05       0  335.71     .06       0
  549.42      .1       0  569.42     .06       0  602.64    .045       0
   680.9     .08       0  758.35     .05       0  958.35      .1       0
#XS Ineff= 2 , 0
                          703.54         2250.03
Permanent Ineff=
       F       F
Bank Sta=602.64,680.9
XS Rating Curve= 0 ,0
Exp/Cntr=0.3,0.1

Type RM Length L Ch R = 1 ,33871   ,424.6,424.6,424.6
XS GIS Cut Line= 4
2391784.57099668 713802.743063072392012.48354125713919.864787363
2392571.18582065713741.0167489152392889.31374744713824.901227125
#Sta/Elev= 30
       0 2319.57    26.5  2300.9   101.6 2260.11     150 2250.47   173.8 2247.34
   219.9 2244.64   256.2 2244.98   281.1 2243.56   297.9 2242.11   323.1 2235.96
   390.3 2237.34   453.3 2237.05   499.5 2234.14   646.5 2235.31   701.1 2233.76
  714.17 2229.18   725.8 2226.16   759.9 2225.91   780.9 2226.14   789.9 2229.15
   810.3 2239.22   837.2 2240.43   852.2 2239.85   864.6 2234.14   876.6 2232.25
  1005.2 2232.31  1063.1 2226.16  1108.6 2226.36  1121.1 2233.481171.877 2285.03
#Mann= 11 ,-1,0
       0      .1       0     110     .06       0  326.25     .05       0
  356.25     .06       0  426.25     .05       0  636.25     .06       0
  676.25      .1       0  714.17    .045       0   789.9     .08       0
  842.88     .05       0 1052.88      .1       0
#XS Ineff= 2 , 0
          629.03 2239.53 836.238            2242
Permanent Ineff=
       F       F
Bank Sta=714.17,789.9
XS Rating Curve= 0 ,0
Exp/Cntr(USF)=0,0
Exp/Cntr=0.3,0.1

Type RM Length L Ch R = 1 ,33447   ,470.1,470.1,470.1
XS GIS Cut Line= 4
2391647.66811305714126.1468712232391956.67875054714347.645170986
2392675.64573691714157.2736879582392873.29265964714137.244040159
#Sta/Elev= 30
       0  2313.4    68.5 2284.34    82.8 2275.67   120.1 2263.27   168.8 2264.13
   334.8 2254.92   462.4 2251.56   557.6 2243.06   685.6 2237.74   764.5 2231.12
   963.1 2231.48   967.2 2230.98  975.582225.621  1003.4 2222.99  1062.4 2223.25
 1070.492225.618  1081.9 2234.75  1091.4 2238.09  1132.5 2237.04  1164.7 2227.56
  1196.8 2226.84  1215.8 2232.87    1225 2238.87    1237 2256.71  1241.1 2260.79
  1253.1 2292.61  1261.2 2310.92  1285.3    2334    1307 2359.34  1322.6 2374.46
#Mann= 10 ,-1,0
       0      .1       0     110     .06       0     280     .08       0
   410.2      .1       0   510.2     .05       0   810.2     .06       0
   920.2      .1       0  975.58    .045       0 1070.49     .07       0
  1120.2      .1       0
#XS Ineff= 1 ,-1
 1121.391322.599    2240
Permanent Ineff=
       F
Bank Sta=975.58,1070.49
XS Rating Curve= 0 ,0
Exp/Cntr=0.3,0.1

Type RM Length L Ch R = 1 ,32976   ,523.1,523.1,523.1
XS GIS Cut Line= 3
2391976.97650249715468.9796495472392866.72145956714481.198943202
2392883.96626663714425.670217475
#Sta/Elev= 30
       0 2308.06    36.1 2288.71    53.1 2285.08    96.6 2264.65   163.6 2250.86
     206 2246.13   317.4 2241.62   360.4 2236.87   403.5 2236.96   421.3 2239.21
     471 2229.21   542.7 2228.56   560.6  2231.7   597.3 2225.21   626.3 2223.56
  1030.2 2230.25  1098.5 2228.37 1111.772222.625  1119.5 2219.96  1146.3 2219.59
  1189.5 2220.16 1199.562222.622  1212.1 2229.01  1265.8 2225.65  1273.8 2226.96
  1291.8 2235.25  1333.6 2233.28  1347.8 2252.66  1367.1 2275.35  1387.6 2293.57
#Mann= 7 ,-1,0
       0      .1       0     740     .05       0     940     .06       0
    1070      .1       0 1111.77    .045       0 1199.56      .1       0
 1329.42     .06       0
Bank Sta=1111.77,1199.56
XS Rating Curve= 0 ,0
Exp/Cntr=0.3,0.1

Type RM Length L Ch R = 1 ,32453   ,544.8,544.8,544.8
XS GIS Cut Line= 3
2393374.23305411 715199.689369982393295.60375221715066.114488745
2393088.87601567714414.734546281
#Sta/Elev= 30
       0  2331.3    58.6 2292.73    67.1 2284.81    82.9 2281.43   109.7 2261.89
   146.8 2224.56   152.3  2220.9     177 2216.98   228.6 2222.88   281.9 2221.77
   317.8 2216.04   340.1 2217.25   364.7 2222.62   395.2  2222.3  401.18 2218.95
   407.8 2216.59   483.3 2215.38   546.3 2218.97   554.7 2218.68     584 2225.87
   596.6 2230.78   630.2  2228.2     647 2224.57   672.2 2226.78   684.1 2224.16
   701.5 2223.83   772.9 2227.13   793.9  2235.5   814.3 2249.86   838.4  2270.2
#Mann= 8 ,-1,0
       0      .1       0     150     .06       0     255      .1       0
     365     .05       0  401.18    .045       0   546.3      .1       0
     565     .06       0     675      .1       0
Bank Sta=401.18,546.3
XS Rating Curve= 0 ,0
Exp/Cntr=0.3,0.1

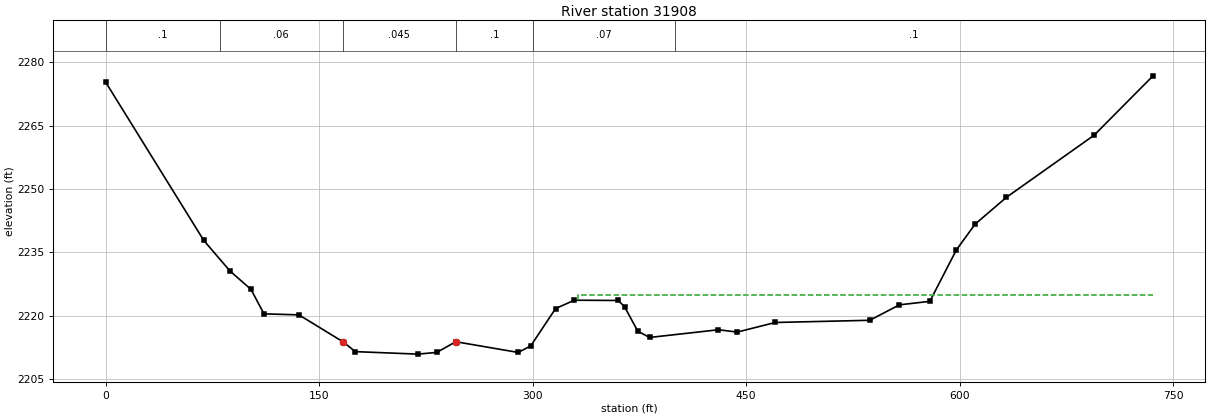
Type RM Length L Ch R = 1 ,31908   ,514.7,514.7,514.7
XS GIS Cut Line= 2
2393816.03260382714844.696588042     2393510.061714175.546188439
#Sta/Elev= 30
       0 2275.25    68.9 2237.85    87.4 2230.59   102.1 2226.26   111.2 2220.48
   135.8 2220.24  166.69 2213.88   175.4 2211.55   219.4 2210.96   232.6 2211.37
  245.99 2213.89   289.8 2211.36   298.6  2212.9   316.1 2221.74   329.3 2223.71
   360.1 2223.64   364.5 2222.18   373.8 2216.39   382.1  2214.9   430.5 2216.72
   443.7 2216.17   470.4 2218.44   536.8 2218.96   557.6 2222.61     579 2223.44
   597.6 2235.58   610.8 2241.69   632.8 2248.03   694.4 2262.71   735.8 2276.75
#Mann= 6 ,-1,0
       0      .1       0      80     .06       0  166.69    .045       0
  245.99      .1       0     300     .07       0     400      .1       0
#XS Ineff= 2 , 0
                        332.0106            2225
Permanent Ineff=
       F       F
Bank Sta=166.69,245.99
XS Rating Curve= 0 ,0
Exp/Cntr=0.3,0.1