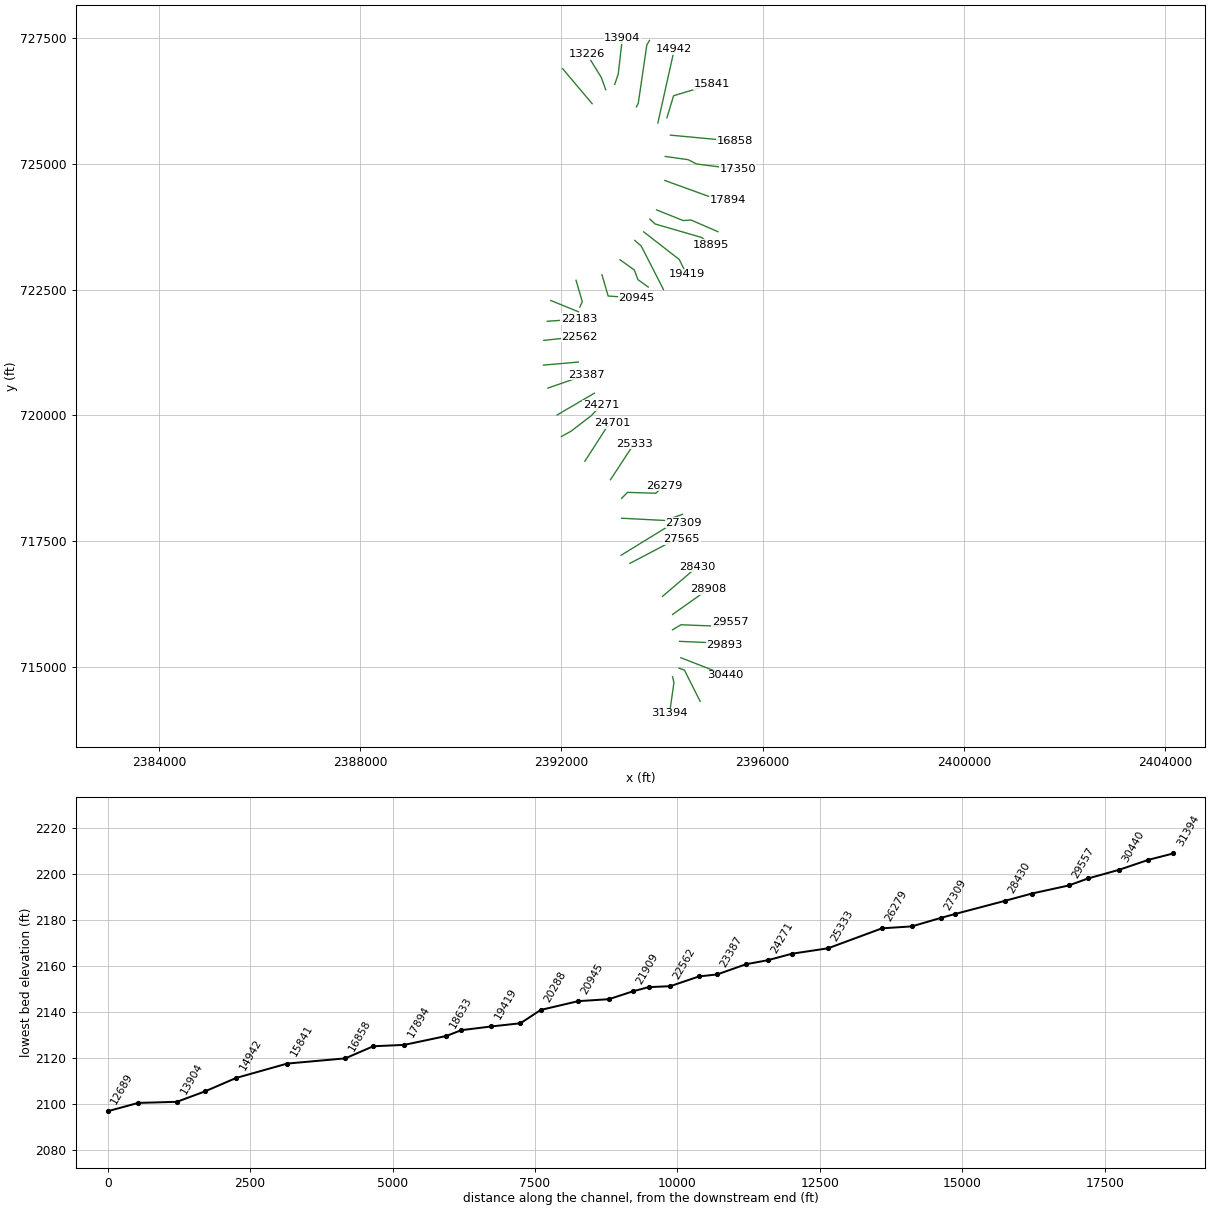
HEC-RAS study DRKFK_2.prj: DRKFK_2

--- DRKFK_2.g01 (geometry) --- (continued)

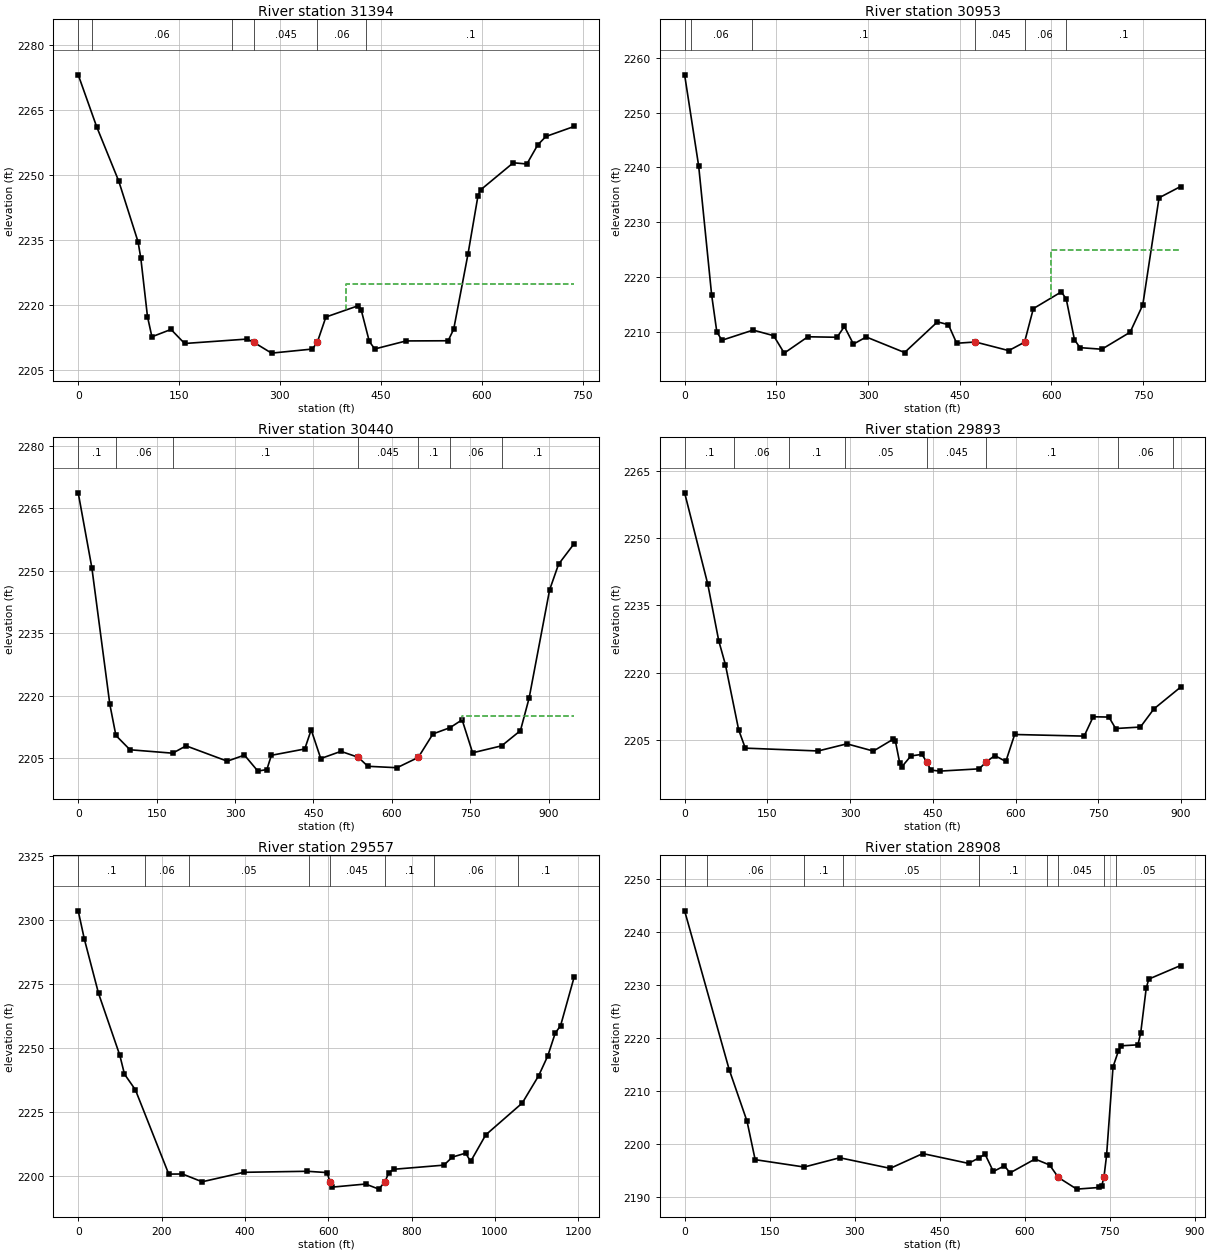
Type RM Length L Ch R = 1 ,31394   ,441.1,441.1,441.1
XS GIS Cut Line= 3
2394210.86210575 714795.822206242394238.10503039714680.458756078
2394151.20086796714067.506758132
#Sta/Elev= 30
       0 2273.11    27.4 2261.16    60.3  2248.6      89 2234.62    93.1 2230.85
     103 2217.39   109.6 2212.74     138 2214.43   158.2 2211.19   251.1 2212.21
   261.1 2211.46   287.5 2208.97   348.1 2209.91  355.49 2211.45   368.3 2217.29
   416.7 2219.91   420.8 2218.94   432.9 2211.65     441 2209.93   487.6 2211.78
   550.1 2211.82   558.4  2214.5   579.6 2231.77   594.5 2245.24   598.6 2246.62
     647 2252.84   667.2 2252.56   683.4 2256.97   695.5  2258.9   737.6 2261.22
#Mann= 6 ,-1,0
       0      .1       0      20     .06       0  228.54      .1       0
   261.1    .045       0  355.49     .06       0  428.54      .1       0
#XS Ineff= 2 , 0
                        397.8747            2225
Permanent Ineff=
       F       F
Bank Sta=261.1,355.49
XS Rating Curve= 0 ,0
Exp/Cntr=0.3,0.1

Type RM Length L Ch R = 1 ,30953   ,512.8,512.8,512.8
XS GIS Cut Line= 3
2394338.43957172      714966.378 2394445.7729711714928.957372797
2394760.07151621714306.123060778
#Sta/Elev= 30
       0 2256.87      23 2240.24    44.2 2216.76    52.7 2210.01    61.1 2208.51
     112 2210.36   145.6 2209.34   162.9 2206.16   201.6 2209.14   249.3 2209.05
   261.3 2211.02   276.1 2207.81   297.1  2209.1   359.8 2206.27   413.6 2211.86
   431.5 2211.34     445 2207.96   475.6 2208.19   530.1 2206.62     556 2208.15
   570.4 2214.27   616.2 2217.32   624.2 2216.03   637.6 2208.63   646.6 2207.16
   682.4 2206.87   728.7 2209.97   749.4 2214.94     776 2234.46   811.3 2236.52
#Mann= 6 ,-1,0
       0      .1       0      10     .06       0     110      .1       0
   475.6    .045       0     556     .06       0  623.67      .1       0
#XS Ineff= 2 , 0
                        599.3875            2225
Permanent Ineff=
       F       F
Bank Sta=475.6,556
XS Rating Curve= 0 ,0
Exp/Cntr=0.3,0.1

Type RM Length L Ch R = 1 ,30440   ,546.4,546.4,546.4
XS GIS Cut Line= 2
2394375.85288997715174.2661165832395260.00426299714829.272217707
#Sta/Elev= 30
       0 2268.69    26.1 2250.69    60.5 2217.89    72.1 2210.41    99.1 2206.97
   180.7 2206.15   206.4 2207.91   285.2 2204.23   318.1 2205.69   343.8 2201.84
     361 2202.23   369.6 2205.64   433.5 2207.16   445.8 2211.76   464.1 2204.86
   502.7 2206.59   535.9 2205.16   554.2    2203   610.1 2202.66  650.732205.138
   678.8 2210.78   711.5 2212.28   734.6 2214.17   754.7 2206.24   810.3 2207.92
   846.2 2211.57   862.8 2219.38     902 2245.37   919.2 2251.55   949.1  2256.5
#Mann= 7 ,-1,0
       0      .1       0    72.1     .06       0   180.7      .1       0
   535.9    .045       0  650.73      .1       0   711.5     .06       0
   810.3      .1       0
#XS Ineff= 2 , 0
                           734.6            2215
Permanent Ineff=
       F       F
Bank Sta=535.9,650.73
XS Rating Curve= 0 ,0
Exp/Cntr=0.3,0.1

Type RM Length L Ch R = 1 ,29893   ,336.6,336.6,336.6
XS GIS Cut Line= 3
2394350.29575652715500.4150065712394965.27856222715473.955141741
2395243.73371636715419.588686792
#Sta/Elev= 30
       0 2260.06    41.9 2239.76    61.9 2227.09    73.9 2221.81      98 2207.26
     110 2203.19   242.1 2202.56   294.2 2204.15   342.2 2202.54   378.2 2205.18
   382.2 2204.73   390.2 2199.77   394.2 2199.09   410.3 2201.46   430.3  2201.8
   438.7 2200.16   446.3 2198.31   462.3 2198.07   534.1 2198.58  547.26 2200.17
   562.4 2201.53   582.4 2200.23   598.4 2206.23   724.4 2205.87   740.8 2210.18
   769.3 2210.11   781.5 2207.56   826.4 2207.89   850.8 2211.92   899.3 2216.78
#Mann= 8 ,-1,0
       0      .1       0      90     .06       0     190      .1       0
     290     .05       0   438.7    .045       0  547.26      .1       0
  785.55     .06       0  885.55      .1       0
Bank Sta=438.7,547.26
XS Rating Curve= 0 ,0
Exp/Cntr=0.3,0.1

Type RM Length L Ch R = 1 ,29557   ,648.5,648.5,648.5
XS GIS Cut Line= 4
 2394210.3551232715730.783801477 2394377.6065651715830.525116782
2395157.68758808715799.7398903472395354.01580784715887.598080039
#Sta/Elev= 30
       0 2303.75    14.7 2292.71    48.7 2271.54    99.9 2247.28     111 2239.96
   137.2 2233.85   217.3 2200.91   250.2 2200.95   297.4 2197.91   397.5 2201.61
   549.6 2202.01   597.6  2201.5  603.95 2197.94   609.6 2195.82   689.7 2197.03
   721.7 2195.04   736.1 2197.95   745.7 2201.51   757.7  2202.8   877.8 2204.41
   897.8 2207.54   929.9  2209.1   941.9 2205.85   978.1 2216.22  1065.8 2228.67
  1105.2 2239.35  1127.1  2247.1  1144.9 2255.97  1157.8  2258.9  1190.5 2277.96
#Mann= 8 ,-1,0
       0      .1       0     160     .06       0  264.73     .05       0
  554.73      .1       0  603.95    .045       0   736.1      .1       0
  854.73     .06       0 1055.42      .1       0
Bank Sta=603.95,736.1
XS Rating Curve= 0 ,0
Exp/Cntr=0.3,0.1

Type RM Length L Ch R = 1 ,28908   ,478.1,478.1,478.1
XS GIS Cut Line= 2
2394212.05473081716035.8104985812394925.64078794 716541.92078146
#Sta/Elev= 30
       0 2244.04    78.6 2214.08   110.1 2204.32   124.4 2197.08     211 2195.69
   273.6 2197.44   362.6 2195.44     420 2198.23   500.7 2196.38     520 2197.46
   529.8 2198.13   544.5 2194.85   564.1 2195.92   573.9 2194.58     618  2197.2
   643.7 2196.08   659.2 2193.72   691.6 2191.52   730.8 2191.83   735.7 2192.14
  739.52 2193.73   744.2 2197.88   755.6 2214.59   765.2 2217.63   770.1 2218.57
   799.5 2218.75   804.4 2220.99   814.2  2229.5   818.7 2231.16   874.8 2233.72
#Mann= 9 ,-1,0
       0      .1       0      40     .06       0     210      .1       0
     280     .05       0     520      .1       0     640     .06       0
   659.2    .045       0  739.52     .08       0     760     .05       0
Bank Sta=659.2,739.52
XS Rating Curve= 0 ,0
Exp/Cntr=0.3,0.1

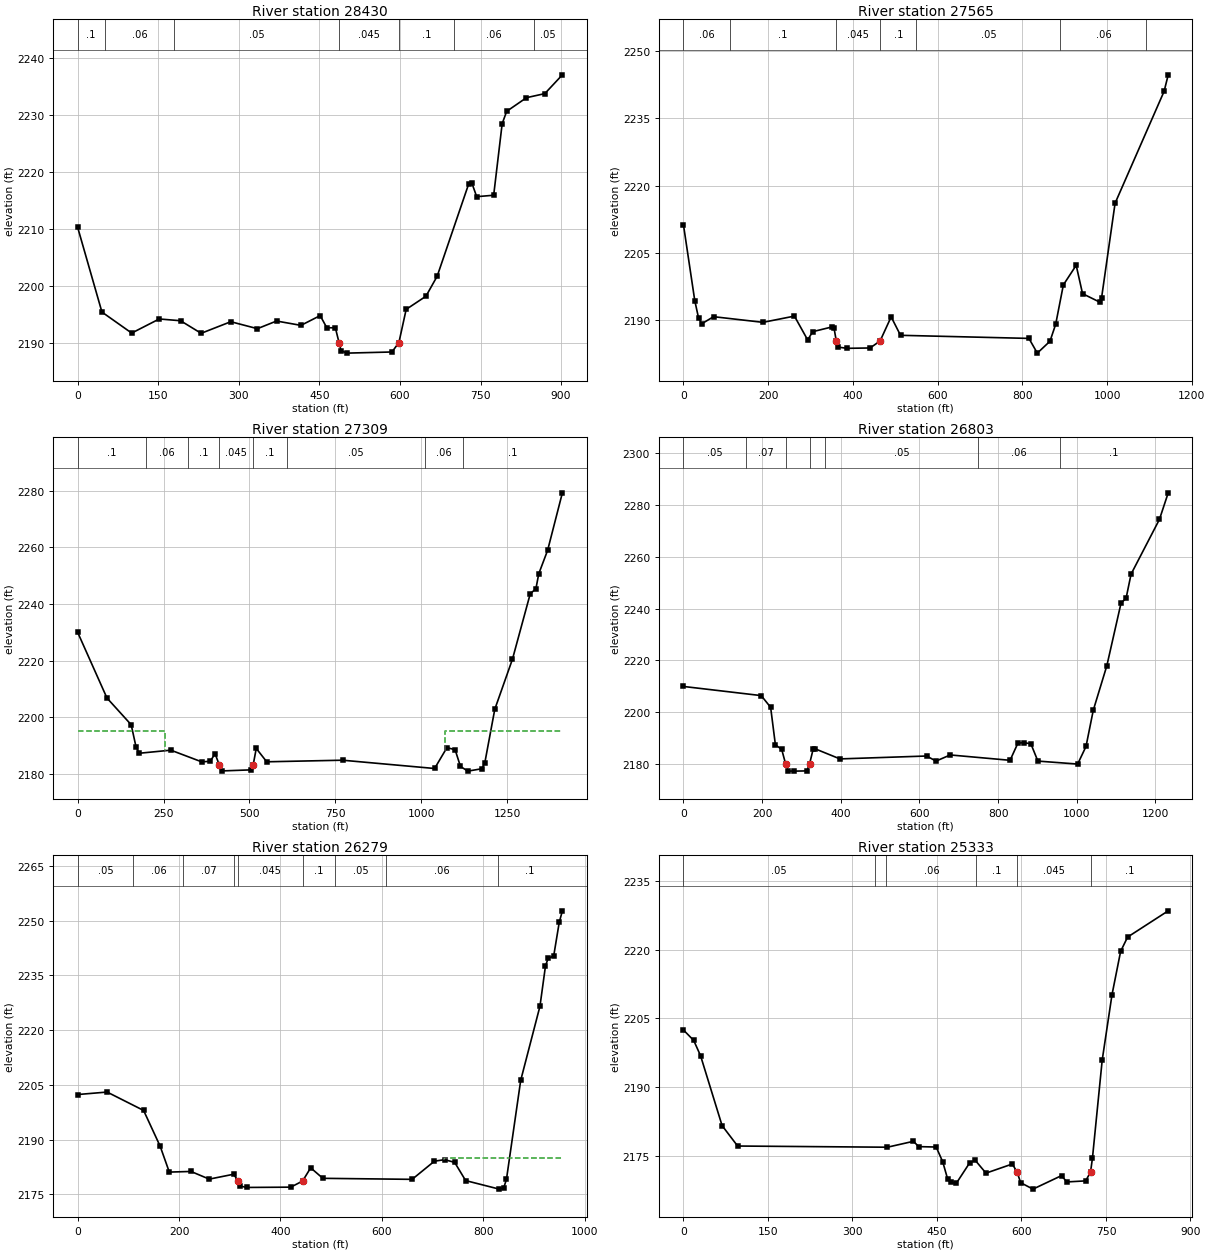
Type RM Length L Ch R = 1 ,28430   ,864.9,864.9,864.9
XS GIS Cut Line= 2
2394011.42858832716395.7964087352394697.41765982716982.167922731
#Sta/Elev= 30
       0 2210.33    45.2  2195.5   100.6 2191.82   151.9 2194.29   191.6 2193.98
   229.9 2191.78   285.1 2193.81   334.6 2192.59   370.3 2193.93   415.7 2193.17
   451.5 2194.88   463.8 2192.76   479.8 2192.74   486.7 2190.12   490.4 2188.76
   500.8 2188.31   585.1 2188.51  598.05 2190.16   611.6 2195.97   648.4 2198.27
   669.3 2201.77   727.8 2217.88   733.5 2218.18   742.9  2215.7   774.5 2215.95
   790.3 2228.47   798.7 2230.64   835.6 2233.03   869.7 2233.74   902.4 2237.03
#Mann= 7 ,-1,0
       0      .1       0      50     .06       0     180     .05       0
   486.7    .045       0  598.05      .1       0     700     .06       0
     850     .05       0
Bank Sta=486.7,598.05
XS Rating Curve= 0 ,0
Exp/Cntr=0.3,0.1

Type RM Length L Ch R = 1 ,27565   ,256.8,256.8,256.8
XS GIS Cut Line= 3
2393361.98928592717051.4990827692394197.09419939717489.723962544
2394393.77047085717533.252266151
#Sta/Elev= 30
       0 2211.19    26.6 2194.36    35.5 2190.51    43.1  2189.2      71 2190.78
   187.7 2189.52   261.9 2190.91   293.2  2185.6   305.1 2187.44   350.3 2188.49
   355.4 2188.25  360.84 2185.33   364.3 2184.01   386.4 2183.73   440.6 2183.81
  464.22 2185.37   490.3 2190.74   512.4 2186.63   815.6 2185.94   835.4 2182.66
   865.3 2185.31   878.8  2189.1   896.9 2197.86   927.2 2202.23   942.2 2195.91
   983.1 2194.01   987.2 2195.02    1019 2216.05  1134.7 2240.98  1144.5 2244.67
#Mann= 7 ,-1,0
       0     .06       0     110      .1       0  360.84    .045       0
  464.22      .1       0     550     .05       0     890     .06       0
  1093.1      .1       0
Bank Sta=360.84,464.22
XS Rating Curve= 0 ,0
Exp/Cntr=0.3,0.1

Type RM Length L Ch R = 1 ,27309   ,505.5,505.5,505.5
XS GIS Cut Line= 3
2393187.49351837717212.8270441352394116.34312876717784.207658168
2394426.87981992 717862.62594858
#Sta/Elev= 30
       0 2229.99    85.3 2206.77   155.8 2197.32   169.9 2189.49   179.3 2187.24
   271.2 2188.33   361.3 2184.19   385.9 2184.41     400 2187.07  412.12 2183.15
   419.4 2180.99   503.3 2181.36  510.94 2183.15   519.8 2188.94   550.3 2184.22
     771 2184.78  1038.9 2181.85  1074.8 2189.23  1098.6 2188.49  1114.2 2182.57
  1135.7 2180.92    1177 2181.78  1185.2 2183.96  1214.1 2202.79  1265.6 2220.52
  1317.3 2243.63  1333.8  2245.4    1342 2250.66  1367.9    2259  1410.8  2279.3
#Mann= 8 ,-1,0
       0      .1       0     200     .06       0     320      .1       0
  412.12    .045       0  510.94      .1       0     610     .05       0
    1010     .06       0 1120.52      .1       0
#XS Ineff= 2 , 0
         254.268    21951069.678            2195
Permanent Ineff=
       F       F
Bank Sta=412.12,510.94
XS Rating Curve= 0 ,0
Exp/Cntr=0.3,0.1

Type RM Length L Ch R = 1 ,26803   ,524.2,524.2,524.2
XS GIS Cut Line= 3
2393198.83366327717949.693216197  2394064.109799 717904.84008421
2394409.20478391718027.589995629
#Sta/Elev= 30
       0 2209.96   197.6 2206.43   221.6  2201.9   233.7  2187.4   249.7 2185.66
  259.85 2179.96   265.7 2177.29   281.7 2177.25   313.8 2177.34  320.63 2180.04
   329.8  2185.8   333.8 2185.93   397.9 2181.97   618.2 2183.09   642.2 2181.13
   678.3  2183.5   830.5 2181.43   850.5 2188.09   866.5 2188.25   883.5 2187.78
   901.2 2181.13  1002.4 2179.98  1023.6 2186.77  1042.1 2200.77  1076.6 2217.97
  1112.7 2242.18  1125.5 2244.02  1138.2 2253.35  1210.4 2274.52  1232.7 2284.77
#Mann= 7 ,-1,0
       0     .05       0     160     .07       0  259.85    .045       0
  320.63      .1       0     360     .05       0     750     .06       0
  956.44      .1       0
#XS Ineff= 2 , 0
                        856.1115            2185
Permanent Ineff=
       F       F
Bank Sta=259.85,320.63
XS Rating Curve= 0 ,0
Exp/Cntr=0.3,0.1

Type RM Length L Ch R = 1 ,26279   ,945.5,945.5,945.5
XS GIS Cut Line= 4
2393197.97768679718345.1607580932393317.11237771718464.354339102
 2393877.3526997718446.9507040712394044.74623972718600.517183513
#Sta/Elev= 30
       0 2202.33    58.1 2203.01   130.1 2197.97   162.8 2188.15   180.8 2181.08
   223.6 2181.25   259.6 2179.15   307.7 2180.49  316.692178.619   319.7 2177.28
   333.6 2176.87   420.4 2176.95   443.7 2178.62   459.7 2182.25   483.7 2179.37
   659.8 2179.09   703.8 2184.07   723.9 2184.48   743.7 2183.74   765.4 2178.75
   831.7 2176.41   840.2 2176.64   845.9  2179.1     874 2206.22     912 2226.54
   922.9 2237.59     928 2239.61   939.1 2240.31     950  2249.5   956.2 2252.67
#Mann= 9 ,-1,0
       0     .05       0     110     .06       0  208.52     .07       0
  308.52      .1       0  316.69    .045       0   443.7      .1       0
  508.52     .05       0  608.52     .06       0  829.03      .1       0
#XS Ineff= 1 ,-1
 721.745 956.198    2185
Permanent Ineff=
       F
Bank Sta=316.69,443.7
XS Rating Curve= 0 ,0
Exp/Cntr=0.3,0.1

Type RM Length L Ch R = 1 ,25333   ,632.7,632.7,632.7
XS GIS Cut Line= 2
2392976.50293103718715.8327385482393447.63116586719435.855174002
#Sta/Elev= 30
       0 2202.47    18.1 2200.21    30.3 2196.86    68.5 2181.61    96.1 2177.15
   361.9 2176.89   408.2 2178.18   417.5 2177.02   448.6 2176.93   460.2  2173.7
   468.8    2170   474.3 2169.22   484.4 2169.03   508.3 2173.53   517.9 2174.03
     537 2171.23   583.8 2173.23  592.49 2171.38   598.5 2169.15   620.4 2167.74
   671.1 2170.69   680.4 2169.31   713.9 2169.54   722.6 2171.45     726 2174.53
   743.3 2195.92   760.7 2210.19     776 2219.65   788.4 2222.77   860.5  2228.5
#Mann= 6 ,-1,0
       0     .05       0     340     .07       0     360     .06       0
     520      .1       0  592.49    .045       0   722.6      .1       0
Bank Sta=592.49,722.6
XS Rating Curve= 0 ,0
Exp/Cntr=0.3,0.1

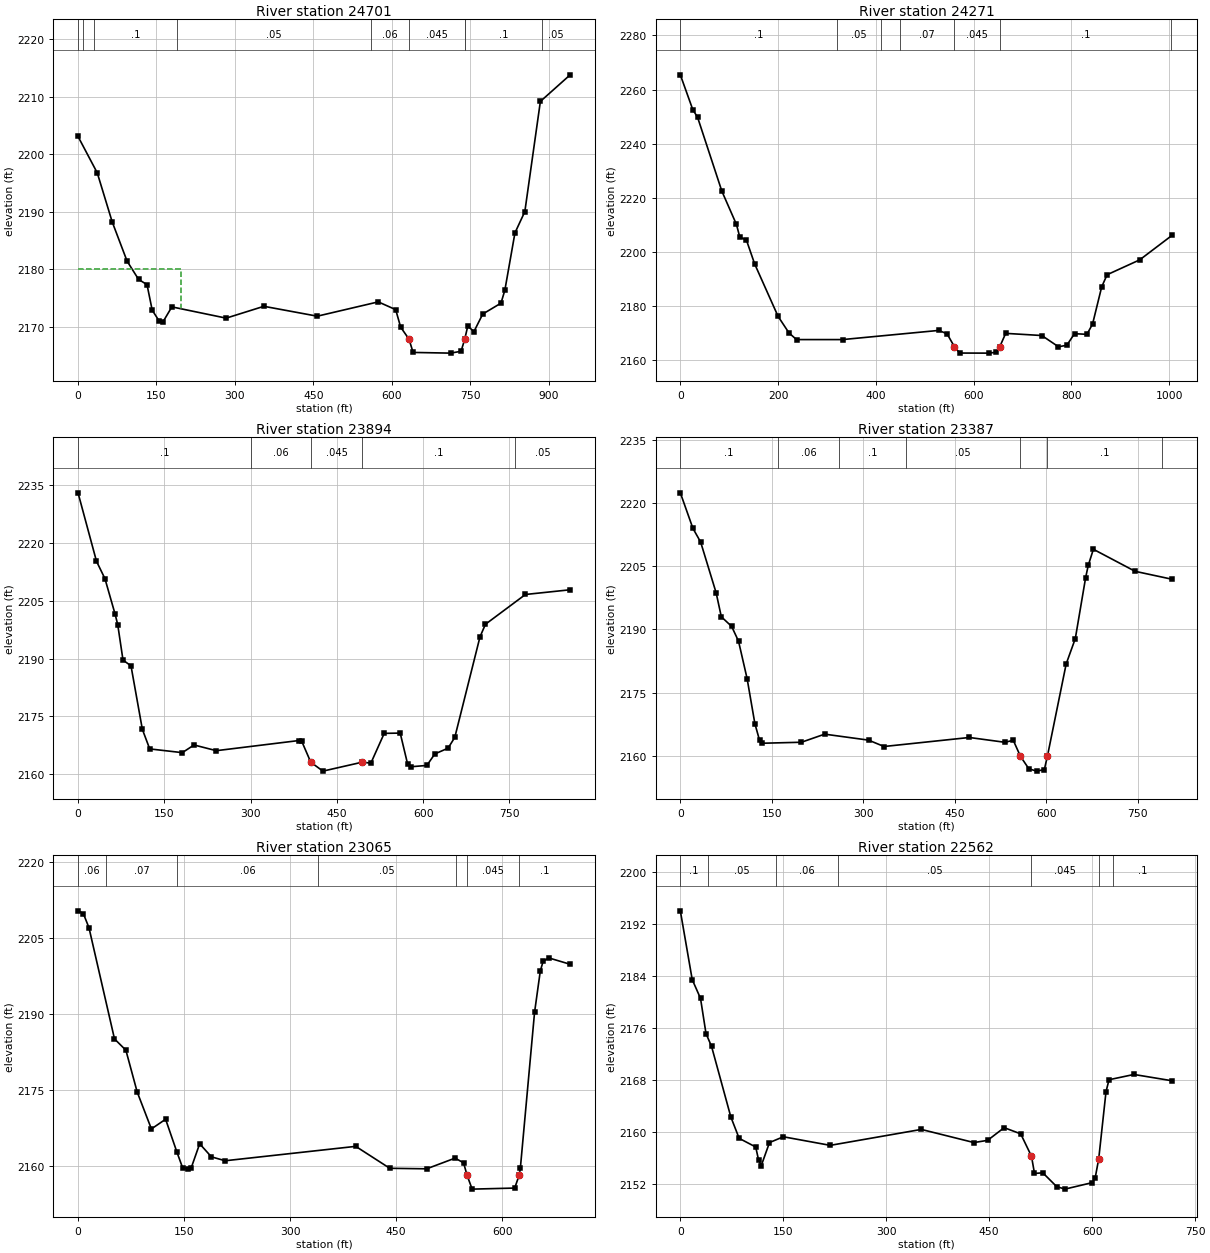
Type RM Length L Ch R = 1 ,24701   ,429.6,429.6,429.6
XS GIS Cut Line= 3
 2392467.1142712719082.2462758182392908.84348459719769.785782574
2393013.71277011719835.422396772
#Sta/Elev= 30
       0 2203.09    36.8 2196.75    65.3 2188.23    93.8 2181.39   115.8 2178.21
   131.9  2177.3   141.8 2172.86   155.6  2170.9   162.1 2170.77   179.4 2173.43
   283.2 2171.47   355.3 2173.53   457.4 2171.81     574  2174.3   607.3 2172.95
   616.8  2169.9   632.7 2167.82   640.6  2165.5   712.1 2165.38   732.3  2165.7
  739.32 2167.82   745.2 2170.12   756.8 2169.11   773.7 2172.18   808.6 2174.08
     816 2176.33   835.3 2186.31   854.2 2190.01   883.9 2209.19   940.9 2213.82
#Mann= 9 ,-1,0
       0      .1       0      10     .05       0      30      .1       0
     190     .05       0     560     .06       0   632.7    .045       0
  739.32     .06       0     740      .1       0  887.21     .05       0
#XS Ineff= 2 , 0
        197.0334    2180
Permanent Ineff=
       F       F
Bank Sta=632.7,739.32
XS Rating Curve= 0 ,0
Exp/Cntr=0.3,0.1

Type RM Length L Ch R = 1 ,24271   ,377.4,377.4,377.4
XS GIS Cut Line= 4
2392001.97454599 719575.360346392392193.87962415719681.969988884
 2392593.2467072719989.668779555 2392789.5907367 720193.55752018
#Sta/Elev= 30
       0 2265.45    25.4 2252.61    35.3 2249.73    84.9 2222.44   114.7 2210.15
   121.5 2205.52   135.3 2204.28     152 2195.53     200  2176.1   222.4 2169.97
   237.7 2167.54   331.8 2167.54   528.6 2170.93   545.6 2169.68   560.7 2164.87
   571.4 2162.56   631.3 2162.53   646.6 2162.87  653.34 2164.88   665.5 2169.84
   739.4 2169.04   773.5 2164.88   790.5 2165.44   806.3 2169.72   831.7 2169.48
   843.2 2173.28   861.8 2186.99   872.9 2191.52   939.6 2197.02  1006.7 2206.21
#Mann= 7 ,-1,0
       0      .1       0  319.53     .05       0  409.53     .06       0
  449.53     .07       0   560.7    .045       0  653.34      .1       0
 1003.68     .05       0
Bank Sta=560.7,653.34
XS Rating Curve= 0 ,0
Exp/Cntr=0.3,0.1

Type RM Length L Ch R = 1 ,23894   ,506.2,506.2,506.2
XS GIS Cut Line= 2
 2391916.6186108720004.781025857 2392655.3211678720436.516032361
#Sta/Elev= 30
       0 2232.95    32.1 2215.21    46.8  2210.7    64.3 2201.58      69 2198.81
    78.2 2189.59    92.1  2188.1   111.8 2171.66   124.6 2166.57   181.3  2165.6
   201.7 2167.59   240.4 2166.11     384 2168.74   388.9 2168.55   404.6 2163.13
   425.7 2160.81   494.1 2163.13   509.1 2162.88   532.3  2170.6   560.1 2170.67
   573.1 2162.56   578.9 2161.95   606.4 2162.28   620.3 2165.27   643.3 2166.76
     655 2169.56   698.8 2195.62   708.3 2198.88   777.8  2206.6   855.6 2207.82
#Mann= 5 ,-1,0
       0      .1       0     300     .06       0   404.6    .045       0
   494.1      .1       0     760     .05       0
Bank Sta=404.6,494.1
XS Rating Curve= 0 ,0
Exp/Cntr(USF)=0,0
Exp/Cntr=0.3,0.1

Type RM Length L Ch R = 1 ,23387   ,322.5,322.5,322.5
XS GIS Cut Line= 2
2391732.74162094720539.1593663282392494.60961939720804.662134939
#Sta/Elev= 30
       0 2222.39    20.6 2213.97    33.3 2210.71    58.7 2198.67    67.2 2192.99
    84.1 2190.71    95.4  2187.2   109.5  2178.3   122.2 2167.64   129.9 2163.67
   133.1 2162.99   198.5 2163.23   236.6 2165.15   308.6 2163.73   333.9 2162.22
   473.8 2164.36     532 2163.22   545.8 2163.69  557.51  2159.9   571.3 2156.94
     584 2156.38   596.7 2156.75   601.7 2159.88   632.5  2181.8   647.5 2187.83
   664.4 2202.27   668.7 2205.18   677.1    2209   745.6 2203.77   806.8 2201.87
#Mann= 7 ,-1,0
       0      .1       0     160     .06       0     260      .1       0
     370     .05       0  557.51    .045       0   601.7      .1       0
     790     .05       0
Bank Sta=557.51,601.7
XS Rating Curve= 0 ,0
Exp/Cntr=0.3,0.1

Type RM Length L Ch R = 1 ,23065   ,502.9,502.9,502.9
XS GIS Cut Line= 3
2391644.74124719720996.2621148012392098.03424719721035.629114801
2392338.34413061721057.409270313
#Sta/Elev= 30
       0 2210.41     7.5 2209.88    15.5 2207.07    51.6 2185.13    67.7 2182.91
    83.7 2174.66   103.8 2167.37   123.9 2169.28     140 2162.76     148 2159.69
     156 2159.45     160 2159.63   172.1 2164.44   188.7 2161.86   208.2 2161.09
   392.9 2163.93   441.1  2159.6   493.3  2159.5   533.5 2161.61   545.5 2160.67
   550.5 2158.18   557.6 2155.49   617.8  2155.7   624.1 2158.22   625.8 2159.62
   645.9 2190.38     654 2198.52     658 2200.43     666 2201.12   696.3 2199.86
#Mann= 7 ,-1,0
       0     .06       0      40     .07       0     140     .06       0
     340     .05       0     535      .1       0   550.5    .045       0
   624.1      .1       0
Bank Sta=550.5,624.1
XS Rating Curve= 0 ,0
Exp/Cntr=0.3,0.1

Type RM Length L Ch R = 1 ,22562   ,378.9,378.9,378.9
XS GIS Cut Line= 2
2391650.93114031721488.6117849972392364.13483345721562.863128393
#Sta/Elev= 30
       0 2194.04    17.3 2183.47    29.4 2180.58    37.4 2175.17    45.5 2173.19
    73.6 2162.34    85.7 2159.06   109.8 2157.73   113.9 2155.78   117.9 2154.86
   129.9 2158.41   150.1  2159.3   218.4 2157.98   351.1 2160.43   427.8 2158.41
   447.7 2158.75   471.8  2160.7   495.9 2159.75   511.6 2156.31     516 2153.66
   528.1 2153.76   548.2 2151.65   560.3 2151.25   600.5 2152.26   604.5 2153.02
  609.57  2155.9   620.2 2166.24   624.6 2168.07   660.9 2168.88717.0584  2167.9
#Mann= 7 ,-1,0
       0      .1       0      40     .05       0     140     .06       0
     230     .05       0   511.6    .045       0  609.57     .05       0
     630      .1       0
Bank Sta=511.6,609.57
XS Rating Curve= 0 ,0
Exp/Cntr(USF)=0,0
Exp/Cntr=0.3,0.1

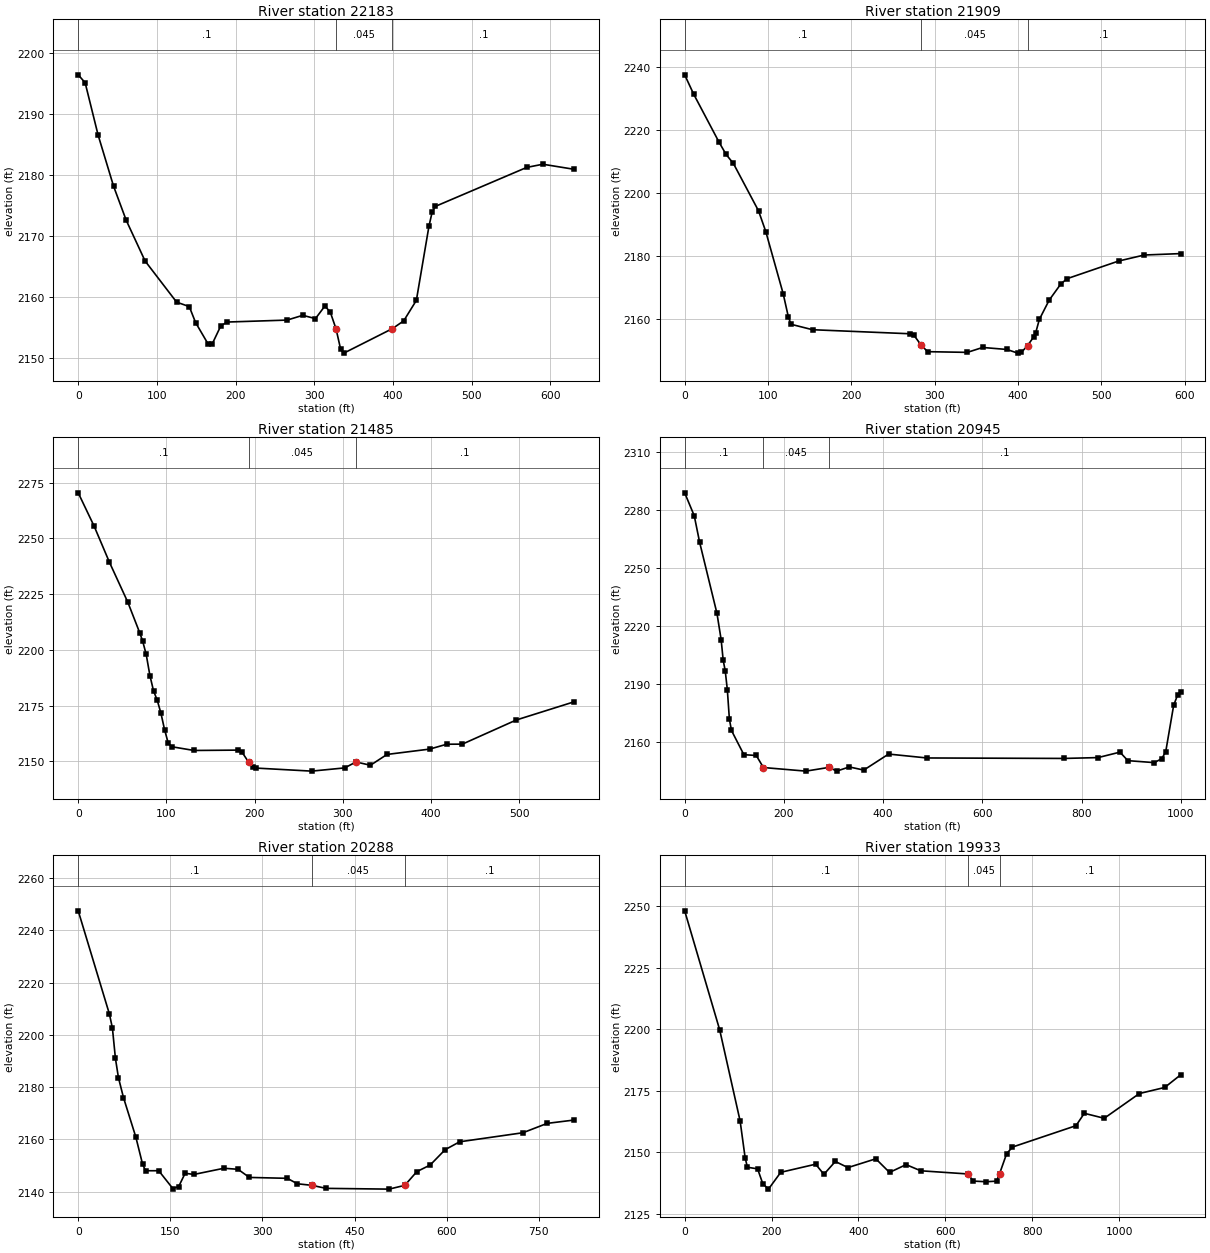
Type RM Length L Ch R = 1 ,22183   ,274.1,274.1,274.1
XS GIS Cut Line= 2
2391719.36507786721867.7622202572392348.30733267721912.387118768
#Sta/Elev= 30
       0 2196.42     8.8 2195.13    25.2  2186.6    44.9  2178.2      61 2172.61
      85 2165.94   125.1  2159.2   141.2 2158.47   149.2 2155.86   165.2 2152.33
   170.6 2152.42   181.3 2155.32   189.3 2155.94   265.5 2156.26   285.5 2157.04
   301.6  2156.5   313.6 2158.56   320.4 2157.59   327.8 2154.81   333.6  2151.5
   337.7 2150.85  399.542154.869   413.8 2156.13   429.9 2159.49   445.9 2171.63
   449.9  2173.9   453.9 2174.87   570.2 2181.26   590.7 2181.78   630.5 2180.95
#Mann= 3 ,-1,0
       0      .1       0   327.8    .045       0  399.54      .1       0
Bank Sta=327.8,399.54
XS Rating Curve= 0 ,0
Exp/Cntr=0.3,0.1

Type RM Length L Ch R = 1 ,21909   ,423.8,423.8,423.8
XS GIS Cut Line= 2
2391790.10675591722281.1126716982392341.19826356722056.668049652
#Sta/Elev= 30
       0 2237.37    10.7 2231.28    41.1 2216.06    49.7 2212.09    58.4 2209.26
    88.6  2194.2    97.3 2187.62   118.2 2167.87   124.3 2160.65   127.5  2158.2
   153.4 2156.47     270 2155.19   274.7 2154.84  284.032151.462   291.6  2149.5
   339.1 2149.28   357.5 2150.84   386.6  2150.2   399.6 2149.04   403.9 2149.26
  411.442151.461   418.9 2154.25   421.2 2155.55   425.5 2159.74   437.3 2165.86
   451.4 2171.03   458.8 2172.67   520.5 2178.26   551.3 2180.18     595 2180.63
#Mann= 3 ,-1,0
       0      .1       0  284.03    .045       0  411.44      .1       0
Bank Sta=284.03,411.44
XS Rating Curve= 0 ,0
Exp/Cntr=0.3,0.1

Type RM Length L Ch R = 1 ,21485   ,540.2,540.2,540.2
XS GIS Cut Line= 3
2392291.60416231722683.1633672432392416.25316231722257.729367243
2392366.29711703722149.677659177
#Sta/Elev= 30
       0 2270.49    18.2  2255.4    35.4 2239.34    56.3 2221.36    69.8 2207.64
      73 2204.07    77.1 2197.96    81.3 2188.52    85.4 2181.65    89.6 2177.43
    93.8  2171.6    97.9 2164.26   102.1 2158.16   106.3 2156.54   131.3 2154.88
   181.3 2155.04   185.5 2154.26  193.192149.674     198 2147.44   202.1 2146.97
   264.7 2145.61   302.2 2147.06     315 2149.72   331.4 2148.25   350.2  2153.1
   398.6  2155.5   417.9 2157.68   435.6 2157.72   496.8 2168.56   562.4 2176.72
#Mann= 3 ,-1,0
       0      .1       0  193.19    .045       0     315      .1       0
Bank Sta=193.19,315
XS Rating Curve= 0 ,0
Exp/Cntr=0.3,0.1

Type RM Length L Ch R = 1 ,20945   ,656.9,656.9,656.9
XS GIS Cut Line= 3
2392807.73850524722791.7067020222392930.65355066722370.624170257
2393490.14137303722330.589068589
#Sta/Elev= 30
       0 2288.79    19.3 2276.91    30.1 2263.23    65.1 2226.34    73.5 2212.79
    77.6 2202.18    81.8 2196.53      86  2186.8    90.1 2171.66    94.3  2165.8
   119.3 2153.27   144.3 2152.84  158.67 2146.61   244.3 2144.75   290.2 2146.66
   306.8 2144.79   331.8 2146.92     361 2145.29     411 2153.58   488.3 2151.56
     765 2151.32   833.2 2151.76   877.3 2154.58   893.3 2150.17   946.7 2149.15
   961.5 2151.21   969.5 2154.69   985.6 2178.85   993.6  2184.2   999.6 2185.84
#Mann= 3 ,-1,0
       0      .1       0  158.67    .045       0   290.2      .1       0
Bank Sta=158.67,290.2
XS Rating Curve= 0 ,0
Exp/Cntr=0.3,0.1

Type RM Length L Ch R = 1 ,20288   ,355,355,355
XS GIS Cut Line= 4
2393166.79165808723090.6179057412393451.45636328722888.295564711
2393522.75205242722696.1932911752393728.76601871722548.589260421
#Sta/Elev= 30
       0 2247.53    50.8    2208    55.7  2202.6    60.6 2190.99    65.5 2183.63
    73.7    2176    93.8 2160.88   104.8 2150.49   109.7 2147.96   131.1 2147.97
   154.1 2141.14   163.6  2141.9   174.1 2146.99   188.5 2146.55   237.2 2148.91
   260.2 2148.52   278.7  2145.4   340.5 2145.06   356.8 2142.97   380.4 2142.38
   403.8 2141.21   506.2 2140.92   531.8 2142.37   551.4 2147.62   573.1 2150.15
   597.5 2156.03   621.1 2159.05   724.2 2162.52   763.7 2166.11   807.6 2167.39
#Mann= 3 ,-1,0
       0      .1       0   380.4    .045       0   531.8      .1       0
Bank Sta=380.4,531.8
XS Rating Curve= 0 ,0
Exp/Cntr=0.3,0.1

Type RM Length L Ch R = 1 ,19933   ,513.9,513.9,513.9
XS GIS Cut Line= 3
2393459.58920879723477.3405325072393588.30856029723364.441396819
     2394029.746      722500.575
#Sta/Elev= 30
       0    2248    80.6  2199.7   127.6 2162.76   139.1 2147.87   144.4 2144.01
   167.8 2143.36   179.7 2137.37   192.8 2135.14   221.1 2141.96   301.4 2145.25
   320.4 2141.14   346.7 2146.36   375.7 2143.87   439.9 2147.44   471.4 2141.91
   509.5 2145.08   543.2 2142.58     651  2141.3   664.5  2138.4   693.4 2138.14
   717.6 2138.37   724.5 2141.32   740.9  2149.5   754.3  2152.2   900.5 2160.87
   919.7 2165.89   965.5 2163.87  1046.3  2173.9  1104.7 2176.37  1141.3 2181.48
#Mann= 3 ,-1,0
       0      .1       0     651    .045       0   724.5      .1       0
Bank Sta=651,724.5
XS Rating Curve= 0 ,0
Exp/Cntr=0.3,0.1

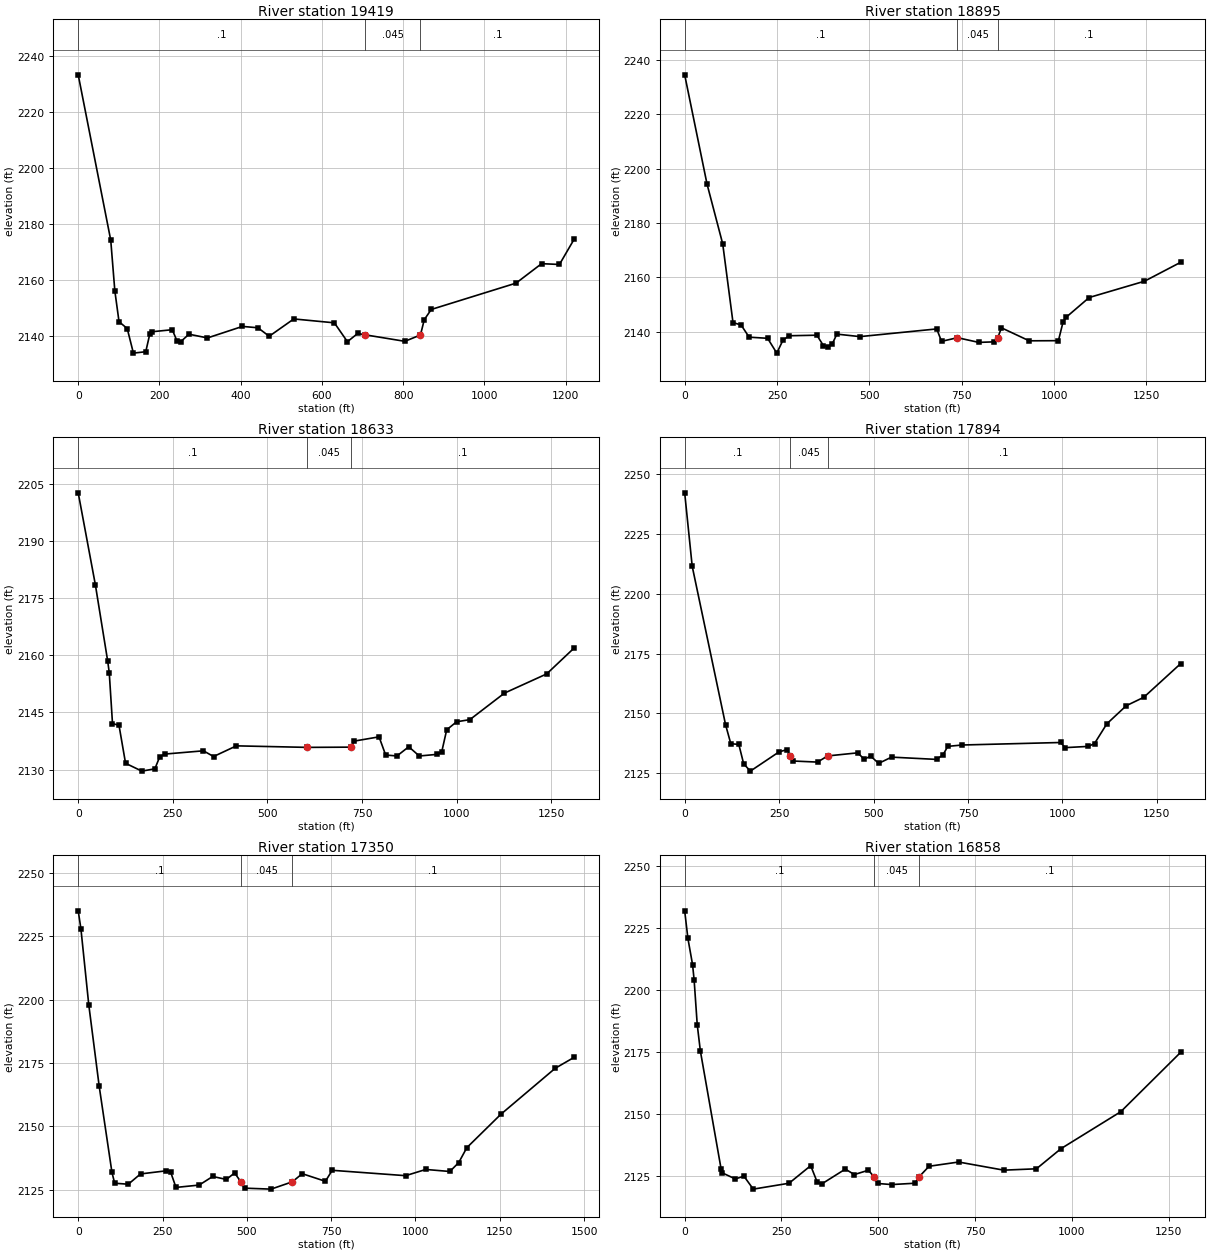
Type RM Length L Ch R = 1 ,19419   ,524.3,524.3,524.3
XS GIS Cut Line= 3
2393636.94057189723646.993509308 2394344.2678608723096.796104397
2394486.85267979722804.683421095
#Sta/Elev= 30
       0 2233.22    80.1 2174.11    90.2 2155.97   100.5 2144.99   120.7 2142.53
   135.9 2133.75   166.3 2134.25   176.4 2140.66   181.5 2141.39   231.6 2142.12
     243 2138.19   252.4 2137.84   272.7 2140.51   318.3 2139.18   404.4  2143.3
   442.6 2142.81   470.3 2139.78   530.9 2145.97   630.7 2144.58   662.9 2137.84
   688.2 2140.78   706.6 2140.29   804.3 2137.97  842.822140.242   852.1 2145.71
   869.4 2149.36  1078.1 2158.77    1141 2165.72    1185 2165.44  1221.2 2174.48
#Mann= 3 ,-1,0
       0      .1       0   706.6    .045       0  842.82      .1       0
Bank Sta=706.6,842.82
XS Rating Curve= 0 ,0
Exp/Cntr=0.3,0.1

Type RM Length L Ch R = 1 ,18895   ,262,262,262
XS GIS Cut Line= 4
2393762.19938279723900.7960615062393862.10174717723804.081759095
2394788.71760561723535.483845697  2394973.556884  723384.5727529
#Sta/Elev= 30
       0 2234.47    60.5 2194.31     103 2172.28   130.8 2143.37   152.7 2142.48
   174.5 2138.01   224.5 2137.59   249.3 2132.14   266.1 2136.92   282.8 2138.53
   357.8 2138.73   375.5 2134.92   386.9 2134.44   399.4 2135.48   411.9 2139.13
   474.4 2138.21   682.3 2141.04   695.2 2136.47  738.37 2137.81     796 2136.09
   836.7 2136.28   847.5 2137.83   857.5 2141.44   932.5 2136.67  1011.6 2136.72
  1024.1 2143.51  1032.4 2145.31  1094.9 2152.59  1244.4 2158.57  1342.4 2165.53
#Mann= 3 ,-1,0
       0      .1       0  738.37    .045       0   847.5      .1       0
Bank Sta=738.37,847.5
XS Rating Curve= 0 ,0
Exp/Cntr=0.3,0.1

Type RM Length L Ch R = 1 ,18633   ,739.2,739.2,739.2
XS GIS Cut Line= 4
2393892.03435686724084.0084589712394423.40871543723871.568461587
2394578.32433897723882.4743411562395112.99365586 723650.00441105
#Sta/Elev= 30
       0 2202.62    45.4 2178.46    77.7 2158.61      82 2155.48    90.6 2142.11
   107.8 2141.63   125.1 2131.68   168.2 2129.62   202.6 2130.23   215.5  2133.4
   228.5 2134.09   330.9 2134.95   357.7 2133.45     418 2136.25   605.1 2135.85
  719.77 2135.91   729.6  2137.5     795 2138.61   812.5 2133.84   842.4  2133.6
   873.5 2136.01   901.4 2133.59   948.8 2134.02   960.8 2134.74   973.8 2140.46
    1000 2142.57  1034.9 2143.12  1126.5 2150.09    1238 2155.12  1310.6 2161.92
#Mann= 3 ,-1,0
       0      .1       0   605.1    .045       0  719.77      .1       0
Bank Sta=605.1,719.77
XS Rating Curve= 0 ,0
Exp/Cntr=0.3,0.1

Type RM Length L Ch R = 1 ,17894   ,544,544,544
XS GIS Cut Line= 3
2394057.42532699724668.998240793   2394915.63216724357.929214593
2395307.67867541724279.163378334
#Sta/Elev= 30
       0  2242.3    19.9 2211.54   108.2  2145.2   122.1 2137.23   143.3 2136.94
   156.1 2128.83   173.8 2125.75   249.7  2133.8     271 2134.76   279.9 2132.08
     288 2129.98   351.8 2129.53  378.19 2132.11   458.2 2133.41   475.2  2130.7
   492.2 2132.04   513.5    2129   547.5 2131.61   666.7 2130.66   683.7 2132.56
   696.4 2136.12   734.7 2136.69     995 2137.74  1007.2 2135.59  1068.4 2136.11
  1084.8 2137.32  1117.4 2145.56  1168.7 2153.13  1215.3 2156.68  1312.7 2170.75
#Mann= 3 ,-1,0
       0      .1       0   279.9    .045       0  378.19      .1       0
Bank Sta=279.9,378.19
XS Rating Curve= 0 ,0
Exp/Cntr=0.3,0.1

Type RM Length L Ch R = 1 ,17350   ,491.6,491.6,491.6
XS GIS Cut Line= 4
2394065.13875815725147.1787597412394521.50294114725082.936721393
2394685.87911334724997.7779815782395503.78448149 724891.87021488
#Sta/Elev= 30
       0 2235.01       8 2227.93    31.3 2197.93    62.3 2165.67     100 2131.79
   108.1 2127.48   148.5 2127.09   184.8 2131.15   261.6 2132.39   273.7 2132.03
   289.9 2125.82   358.6 2126.75   398.9 2130.15   439.3 2128.97   463.9 2131.55
   482.1 2128.05   493.8 2125.53     572 2125.15  634.78 2128.03   664.4 2131.24
     733 2128.24   753.2 2132.58     971 2130.46  1030.7 2132.92    1102 2132.11
  1128.3 2135.61  1152.5 2141.52  1253.3 2154.69  1414.6 2172.86  1470.7 2177.18
#Mann= 3 ,0,0
       0      .1       0   482.1    .045       0  634.78      .1       0
Bank Sta=482.1,634.78
XS Rating Curve= 0 ,0
Exp/Cntr=0.3,0.1

Type RM Length L Ch R = 1 ,16858   ,1016.7,1016.7,1016.7
XS GIS Cut Line= 2
 2394167.8749798725571.3072816972395442.85009957725451.570296533
#Sta/Elev= 30
       0  2232.1     8.3    2221    20.4 2210.36    24.4 2204.21    32.4  2186.2
    40.5  2175.6      94 2128.05    96.7 2126.46   130.8 2123.99     153  2125.1
   177.1 2119.88   269.5 2122.25   325.4 2129.34   341.8 2122.87   353.9 2121.97
   414.8 2127.95   438.2 2125.75   474.4 2127.51   490.1 2124.64   498.5 2122.15
   534.5 2121.72   594.9 2122.26  604.02 2124.64   631.1  2129.1   707.4 2130.81
   823.9 2127.53   908.3 2128.08   971.8 2136.21  1126.1  2151.1  1280.6 2175.02
#Mann= 3 ,-1,0
       0      .1       0   490.1    .045       0  604.02      .1       0
Bank Sta=490.1,604.02
XS Rating Curve= 0 ,0
Exp/Cntr=0.3,0.1

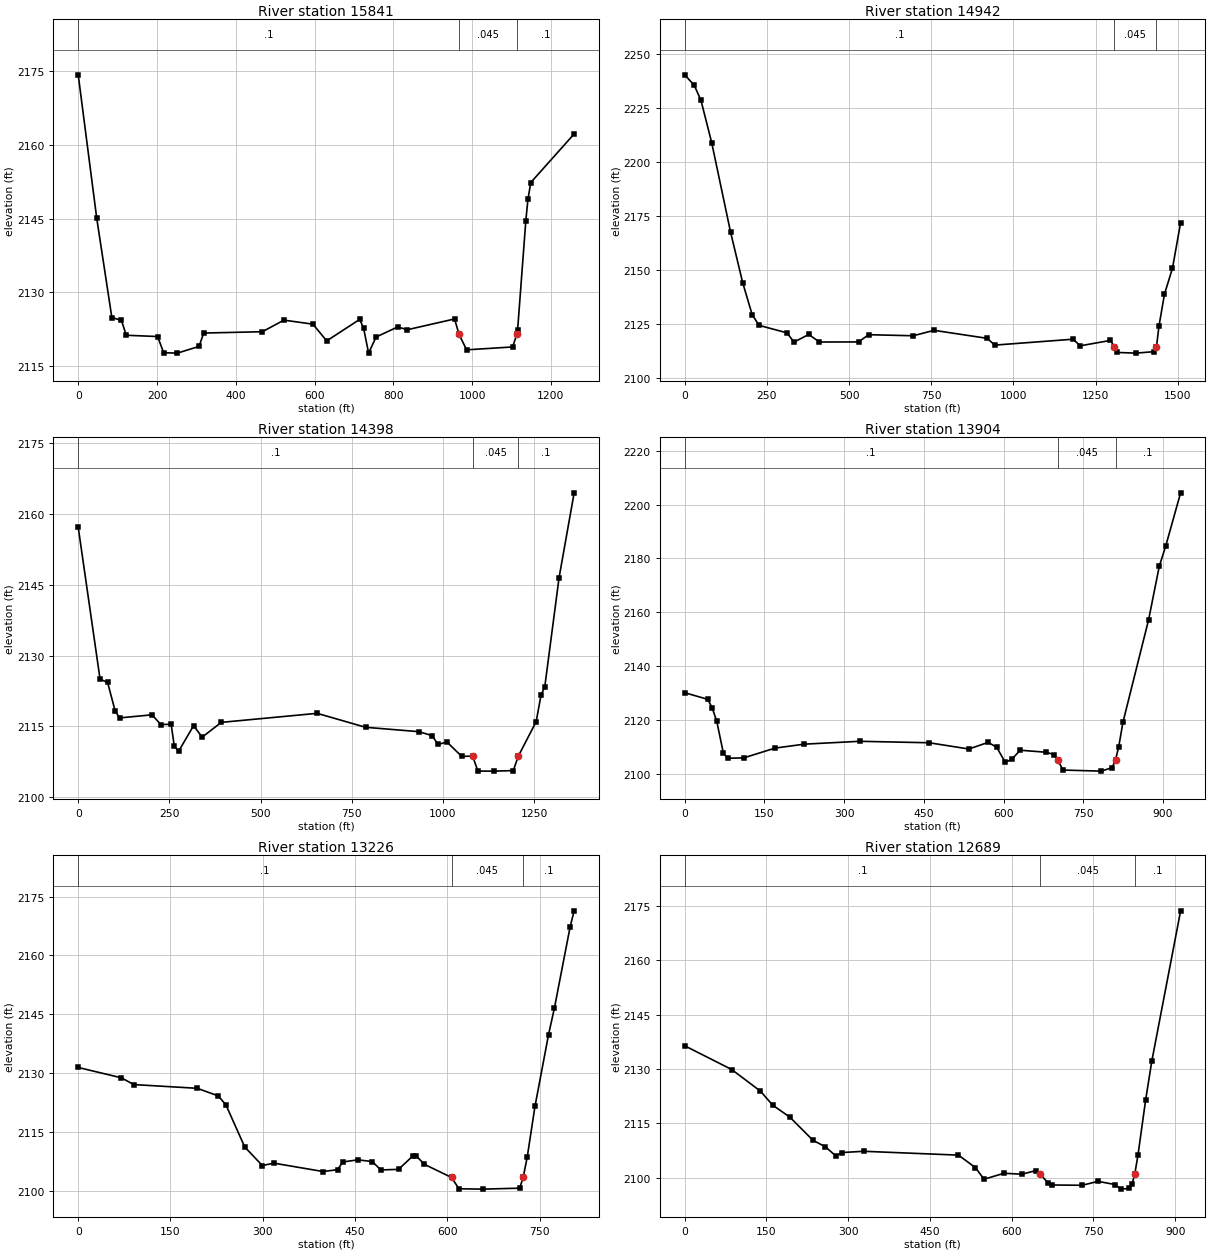
Type RM Length L Ch R = 1 ,15841   ,899.6,899.6,899.6
XS GIS Cut Line= 3
2394098.74604451725916.2504100332394231.04261883726355.085880496
2394997.58735797      726585.809
#Sta/Elev= 30
       0 2174.32    46.9 2145.16    85.4 2124.88   109.6 2124.31   122.1 2121.27
   201.5 2121.01     217 2117.71   251.6 2117.63   306.8    2119   318.5 2121.72
   467.4 2121.99   522.2 2124.35   595.8 2123.53   630.8 2120.12   714.3 2124.49
   724.2 2122.81   737.1 2117.65   756.3 2120.92   810.9 2122.96   835.5  2122.4
   955.4 2124.59  966.55 2121.48   985.9  2118.3  1102.8 2118.89 1113.382121.466
  1115.4 2122.38  1136.2 2144.59  1141.6 2148.98  1148.8 2152.38  1258.9 2162.28
#Mann= 3 ,0,0
       0      .1       0  966.55    .045       0 1113.38      .1       0
Bank Sta=966.55,1113.38
XS Rating Curve= 0 ,0
Exp/Cntr=0.3,0.1

Type RM Length L Ch R = 1 ,14942   ,543.6,543.6,543.6
XS GIS Cut Line= 2
2393918.52686824725812.9070402542394246.52402925 727285.44083072
#Sta/Elev= 30
       0 2240.36      29 2235.53    49.5 2228.55    82.2  2208.9   139.6 2167.43
   176.5 2143.99   205.2 2129.24   226.2 2124.24   311.7 2120.73   332.2 2116.44
   377.3 2120.01   410.1 2116.51   528.9 2116.55   559.5  2119.9   695.4 2119.41
   758.4 2121.93   919.9 2118.22   943.4 2115.08  1181.3 2117.81  1203.4 2114.76
  1295.3 2117.25 1306.66 2114.32  1315.7 2111.67  1373.1 2111.36  1426.4 2112.03
 1435.23 2114.32  1442.8 2123.94  1459.5 2138.71  1483.8 2150.69  1508.6 2171.85
#Mann= 3 ,-1,0
       0      .1       0 1306.66    .045       0 1435.23      .1       0
Bank Sta=1306.66,1435.23
XS Rating Curve= 0 ,0
Exp/Cntr(USF)=0,0
Exp/Cntr=0.3,0.1

Type RM Length L Ch R = 1 ,14398   ,494.5,494.5,494.5
XS GIS Cut Line= 4
2393491.83842214726133.133076096 2393530.0488501726209.781990415
2393698.71837465727364.372049289 2393752.8836637727456.795305855
#Sta/Elev= 30
       0 2157.17    59.9 2124.99    80.5 2124.35   101.1 2118.32   113.3 2116.81
   202.3 2117.47   226.5 2115.41   254.8 2115.47   263.3 2110.87     275 2109.71
   316.3 2115.18   339.7 2112.74   392.3 2115.87     655 2117.78   787.8 2114.83
     934  2113.9   970.3 2113.06   986.4 2111.19  1010.8 2111.72  1051.2 2108.68
  1081.3 2108.72  1095.7 2105.56  1140.1 2105.55  1192.7 2105.66 1206.54 2108.72
  1255.4 2116.02  1268.8 2121.62  1279.1 2123.42  1318.3 2146.52  1359.6 2164.45
#Mann= 3 ,-1,0
       0      .1       0  1081.3    .045       0 1206.54      .1       0
Bank Sta=1081.3,1206.54
XS Rating Curve= 0 ,0
Exp/Cntr=0.3,0.1

Type RM Length L Ch R = 1 ,13904   ,677.5,677.5,677.5
XS GIS Cut Line= 3
2393061.00752116726580.0326406142393131.03803643726789.198605811
2393212.69555169727497.048269429
#Sta/Elev= 30
       0 2130.13    43.4 2127.67    51.8 2124.46    60.3 2119.56    72.9 2107.59
    81.4 2105.78   110.9 2105.91   169.9 2109.55   225.2 2111.02   329.3 2112.08
   459.9 2111.54   534.6 2109.22   570.9 2111.67     587 2109.88   603.1 2104.28
   615.2 2105.35   631.3 2108.77   680.1 2108.01   695.7  2107.1   701.7 2105.22
   711.8  2101.4   783.7    2101   804.4  2102.3  810.59 2105.27   816.5 2109.84
   824.5 2119.08   872.9 2157.26   892.9 2177.06   905.1 2184.64   933.1 2204.38
#Mann= 3 ,-1,0
       0      .1       0   701.7    .045       0  810.59      .1       0
Bank Sta=701.7,810.59
XS Rating Curve= 0 ,0
Exp/Cntr=0.3,0.1

Type RM Length L Ch R = 1 ,13226   ,537.7,537.7,537.7
XS GIS Cut Line= 3
 2392882.2620932726475.3600583982392793.33815425726719.933502433
2392506.74144831727184.613971096
#Sta/Elev= 30
       0 2131.49      70 2128.87    90.4 2127.14   193.5 2126.19   227.8 2124.25
   240.3 2121.91   270.7 2111.25   299.3 2106.54   318.1 2107.14     398 2105.01
   421.5 2105.47   430.1 2107.44   454.4 2107.98   477.9 2107.56     492 2105.41
   520.7 2105.56   543.7 2108.93   549.8 2108.96   562.5 2106.86  606.922103.499
   618.9 2100.62   657.3 2100.53   717.6 2100.77  723.322103.495     730 2108.77
   742.5 2121.59   764.6 2139.88     774 2146.53   799.7 2167.31   806.2 2171.36
#Mann= 3 ,-1,0
       0      .1       0  606.92    .045       0  723.32      .1       0
Bank Sta=606.92,723.32
XS Rating Curve= 0 ,0
Exp/Cntr=0.3,0.1

Type RM Length L Ch R = 1 ,12689   ,381.5,381.5,381.5
XS GIS Cut Line= 3
2392611.73206095726196.9917562232392318.67906095726545.051756223
2392025.62706095726893.110756223
#Sta/Elev= 30
       0 2136.42    86.3 2129.87   138.9 2123.93   161.6 2120.04   192.9 2116.76
   235.5 2110.36   258.2 2108.58   277.4 2106.05   287.8 2106.98   328.5 2107.34
   502.4 2106.28   533.6 2102.82   549.3 2099.64   585.9 2101.28   618.7 2101.03
   644.2    2102   652.7    2101   666.9 2098.56   674.8 2098.05   729.4 2097.97
   758.4 2099.05   789.8 2098.17   800.3 2096.91     816 2097.11   821.2 2098.46
   825.9  2101.1   831.7 2106.24   845.8 2121.47   857.1 2132.17     910 2173.61
#Mann= 3 ,-1,0
       0      .1       0   652.7    .045       0   825.9      .1       0
Bank Sta=652.7,825.9
XS Rating Curve= 0 ,0
Exp/Cntr=0.3,0.1