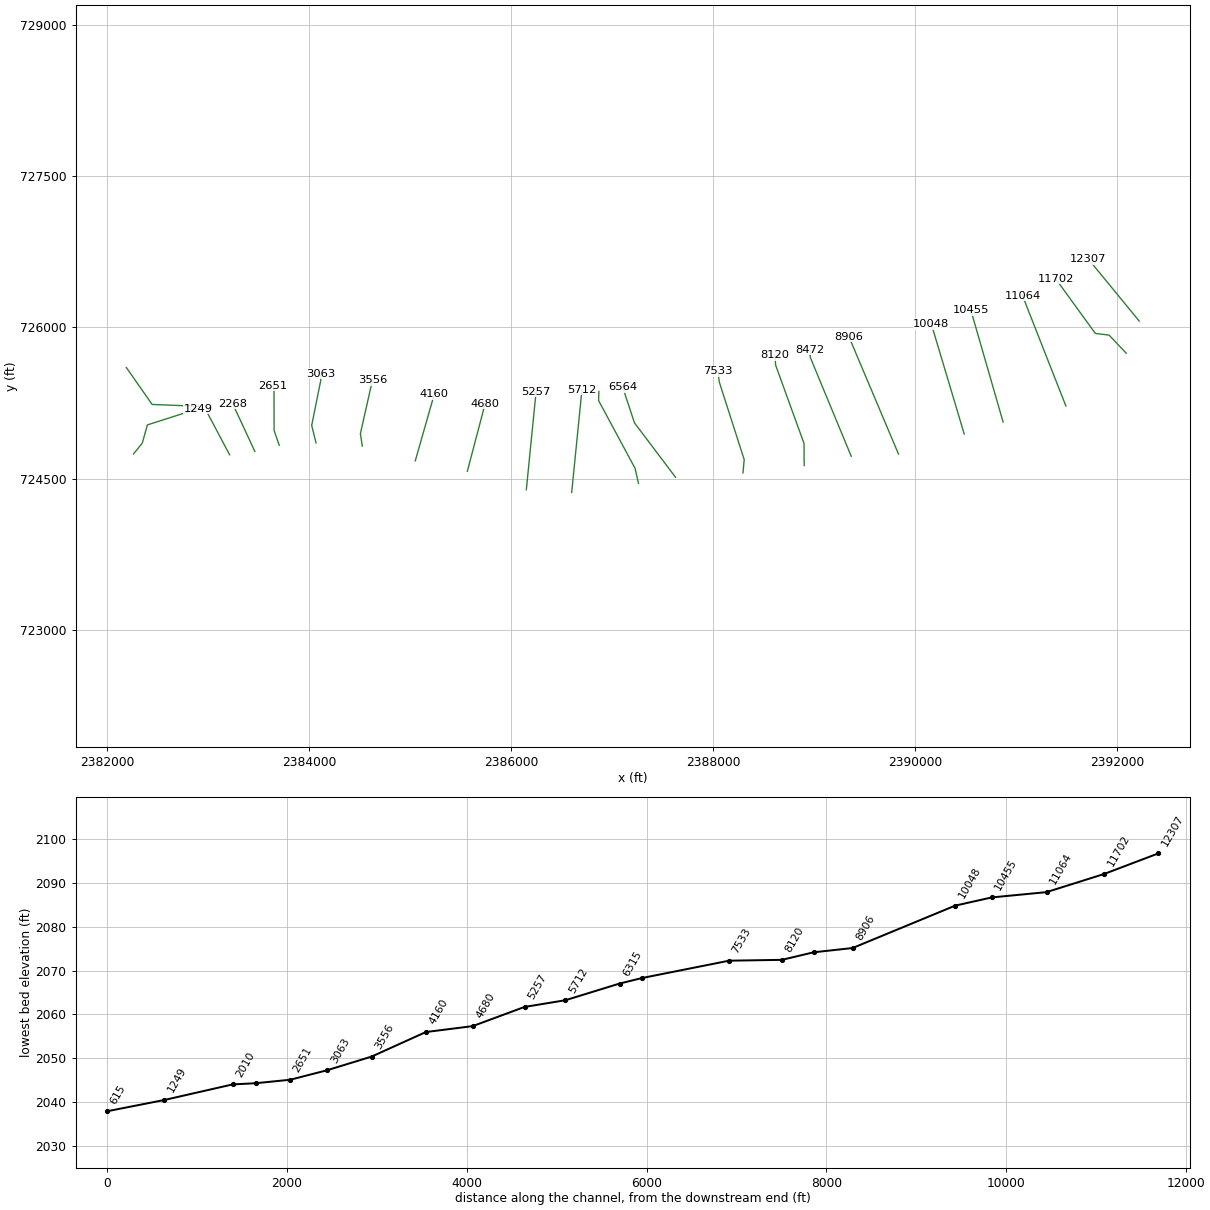
HEC-RAS study DRKFK_2.prj: DRKFK_2

--- DRKFK_2.g01 (geometry) --- (continued)

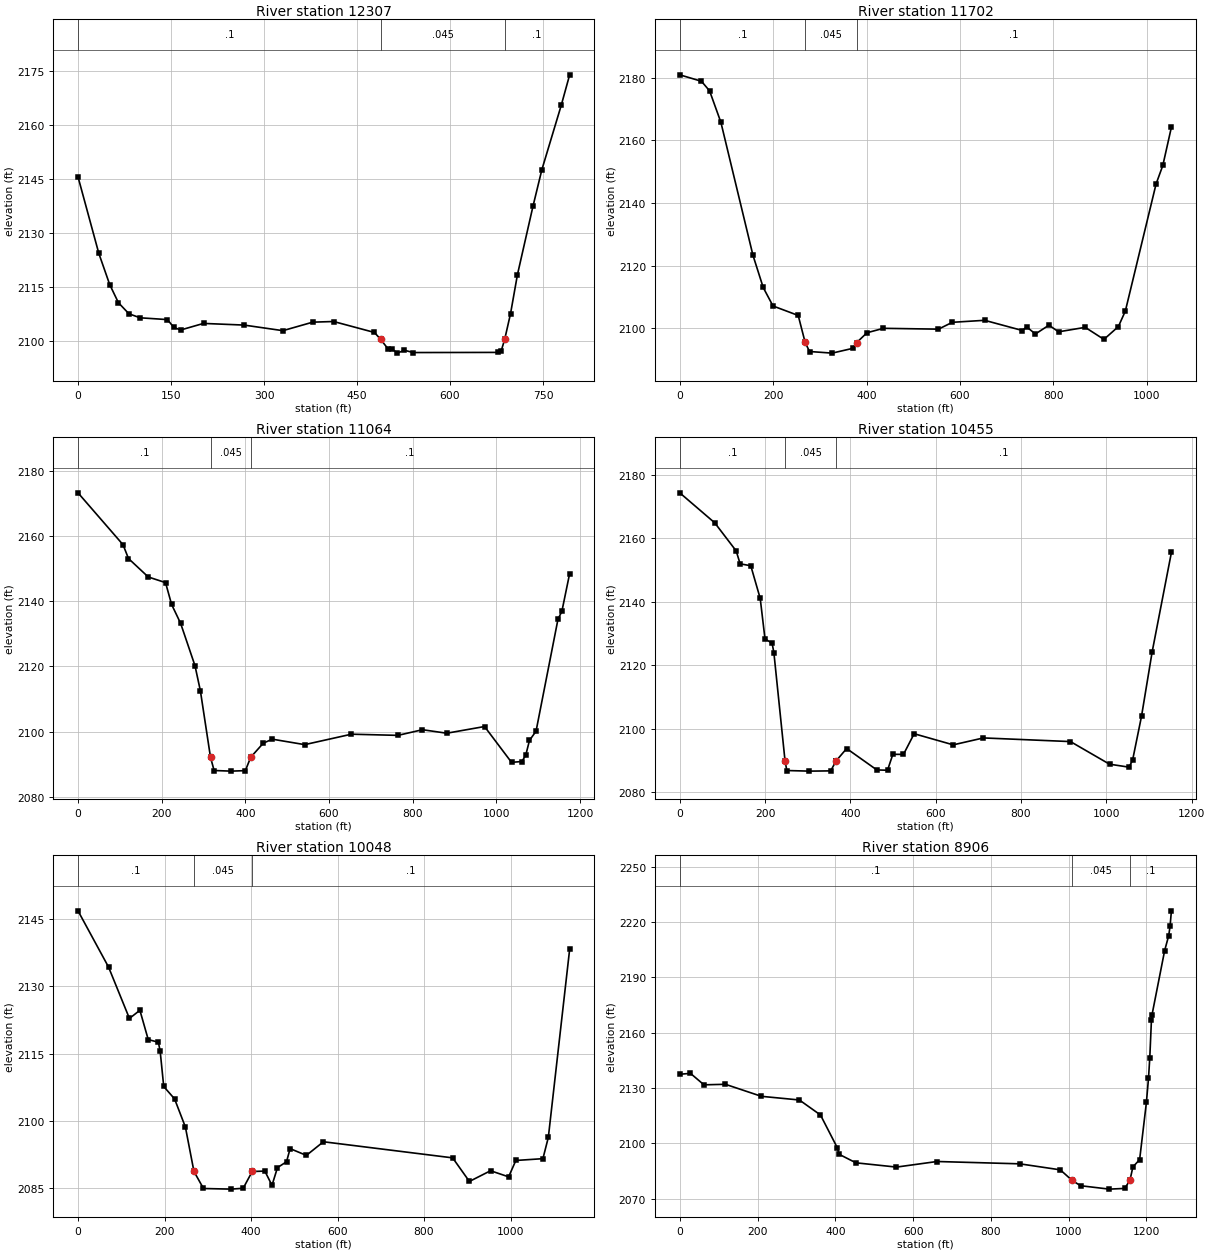
Type RM Length L Ch R = 1 ,12307   ,604.7,604.7,604.7
XS GIS Cut Line= 2
2392221.49741429726061.6701271522391718.82106508726674.846161955
#Sta/Elev= 30
       0 2145.64    33.6 2124.39    51.1 2115.77    65.2 2110.72    82.1 2107.66
   100.1 2106.54   144.2 2106.04   154.5 2103.88   165.4 2103.15   202.4 2104.98
   267.8 2104.52   330.4 2102.97   378.6 2105.33   412.2 2105.51   478.1 2102.47
   487.9 2100.59   500.5 2097.81   506.8 2097.85     515 2096.74   526.4 2097.54
   540.6  2096.9   677.2 2096.94   682.7 2097.46  688.23 2100.63   697.6 2107.73
   708.7 2118.51   733.8 2137.51   748.1 2147.63   779.4 2165.52   792.9 2173.93
#Mann= 3 ,0,0
       0      .1       0   487.9    .045       0  688.23      .1       0
Bank Sta=487.9,688.23
XS Rating Curve= 0 ,0
Exp/Cntr=0.3,0.1

Type RM Length L Ch R = 1 ,11702   ,638.6,638.6,638.6
XS GIS Cut Line= 4
 2392092.8093647725743.4664281492391922.89609919725922.677935862
 2391786.9036057725939.4578249612391394.30789276726481.002456115
#Sta/Elev= 30
       0 2180.98    46.5 2178.92    63.9 2175.85    88.1  2165.8   156.7 2123.34
   178.7 2113.01   199.7  2107.1   253.7 2104.07   268.52095.469   277.9 2092.55
   326.3 2092.03   370.6 2093.56     379 2095.41   400.9 2098.54   436.3 2099.96
   554.1 2099.69   583.7 2101.88   652.9 2102.52   733.7 2099.26     743 2100.42
   761.6 2098.14   790.7 2100.97   811.2 2098.84   868.3 2100.27   908.4 2096.42
   939.4 2100.53   954.3  2105.5  1020.1 2146.11  1034.5 2152.01  1052.9 2164.24
#Mann= 3 ,-1,0
       0      .1       0   268.5    .045       0     379      .1       0
Bank Sta=268.5,379
XS Rating Curve= 0 ,0
Exp/Cntr=0.3,0.1

Type RM Length L Ch R = 1 ,11064   ,609.2,609.2,609.2
XS GIS Cut Line= 2
2391495.17541779725220.9340771722391065.39125336726314.526111974
#Sta/Elev= 30
       0  2173.2   107.7 2157.28   120.6 2153.07   167.9 2147.41   209.2 2145.68
   223.7 2138.99   245.2 2133.21   279.6 2120.21   292.5 2112.51  316.68 2092.13
   325.3 2088.09   365.6  2087.9     400 2088.05   412.8 2092.16   442.9 2096.48
   464.4 2097.69   541.8 2096.02   653.5 2099.22   764.6 2098.86   823.2 2100.59
   881.3 2099.52   971.6 2101.57  1036.1 2090.59  1060.8 2090.85    1070 2092.76
    1079 2097.32  1094.7 2100.15  1147.1 2134.45  1156.4 2136.87    1175 2148.47
#Mann= 3 ,-1,0
       0      .1       0  316.68    .045       0   412.8      .1       0
Bank Sta=316.68,412.8
XS Rating Curve= 0 ,0
Exp/Cntr=0.3,0.1

Type RM Length L Ch R = 1 ,10455   ,407,407,407
XS GIS Cut Line= 2
2390873.67834272725061.2350427582390554.62794101726168.543572473
#Sta/Elev= 30
       0 2174.37      82 2164.92   132.2 2156.08   141.5 2152.01   166.5 2151.39
   188.6 2141.09   199.8 2128.34   216.4    2127   220.6 2124.05   246.8 2089.87
     251 2086.88   303.8 2086.69   353.8 2086.77   366.3 2089.87   366.3 2089.89
   391.2 2093.81     462 2087.06     487 2086.97   499.5 2091.99   524.4 2091.96
   549.4 2098.47     641 2094.97   711.8 2097.15   915.8    2096  1007.3 2088.88
  1053.1 2087.94  1061.4 2090.14  1082.3 2103.95  1107.2 2124.21  1152.4 2155.58
#Mann= 3 ,-1,0
       0      .1       0   246.8    .045       0   366.3      .1       0
Bank Sta=246.8,366.3
XS Rating Curve= 0 ,0
Exp/Cntr=0.3,0.1

Type RM Length L Ch R = 1 ,10048   ,1141.1,1141.1,1141.1
XS GIS Cut Line= 2
2390488.38021224724943.2638967822390162.99092929726032.411996931
#Sta/Elev= 30
       0 2146.86    70.6 2134.33   118.9 2122.87   143.1 2124.69   162.4 2118.15
   185.7 2117.58   189.9 2115.64   198.2  2107.7   223.3 2104.93   248.3 2098.66
  268.08 2088.76   290.1 2084.96   353.8 2084.82   381.9 2085.01   402.8 2088.75
     432 2088.84   448.5 2085.67   461.2 2089.62   482.1 2090.92   490.4 2093.85
     528 2092.34   567.4 2095.38   866.2 2091.79   904.9 2086.53   953.8 2088.92
   995.6 2087.56  1012.3 2091.21  1074.9 2091.61  1087.4 2096.36  1136.7 2138.29
#Mann= 3 ,-1,0
       0      .1       0  268.08    .045       0   402.8      .1       0
Bank Sta=268.08,402.8
XS Rating Curve= 0 ,0
Exp/Cntr(USF)=0,0
Exp/Cntr=0.3,0.1

Type RM Length L Ch R = 1 ,8906    ,434.7,434.7,434.7
XS GIS Cut Line= 2
 2389837.7944339724743.8209585942389346.18606946725908.438489996
#Sta/Elev= 30
       0 2137.43    27.5 2137.92    62.3  2131.7   117.3 2131.99   209.9 2125.47
   307.6 2123.48   361.8 2115.35   405.3  2097.5   409.6 2094.05     453 2089.41
   557.2 2087.09   661.4 2090.12   874.2 2088.86   978.4  2085.6  1008.8 2079.87
  1030.5 2076.99  1104.3 2075.14  1144.1 2075.52 1157.52 2079.97  1165.1 2087.18
  1182.4 2091.14  1199.8 2122.13  1205.2 2135.23  1208.5 2146.37  1212.8 2167.07
  1214.3 2169.73  1246.7 2204.49  1257.1 2212.57  1260.6 2217.59  1264.1 2226.06
#Mann= 3 ,-1,0
       0      .1       0  1008.8    .045       0 1157.52      .1       0
Bank Sta=1008.8,1157.52
XS Rating Curve= 0 ,0
Exp/Cntr=0.3,0.1

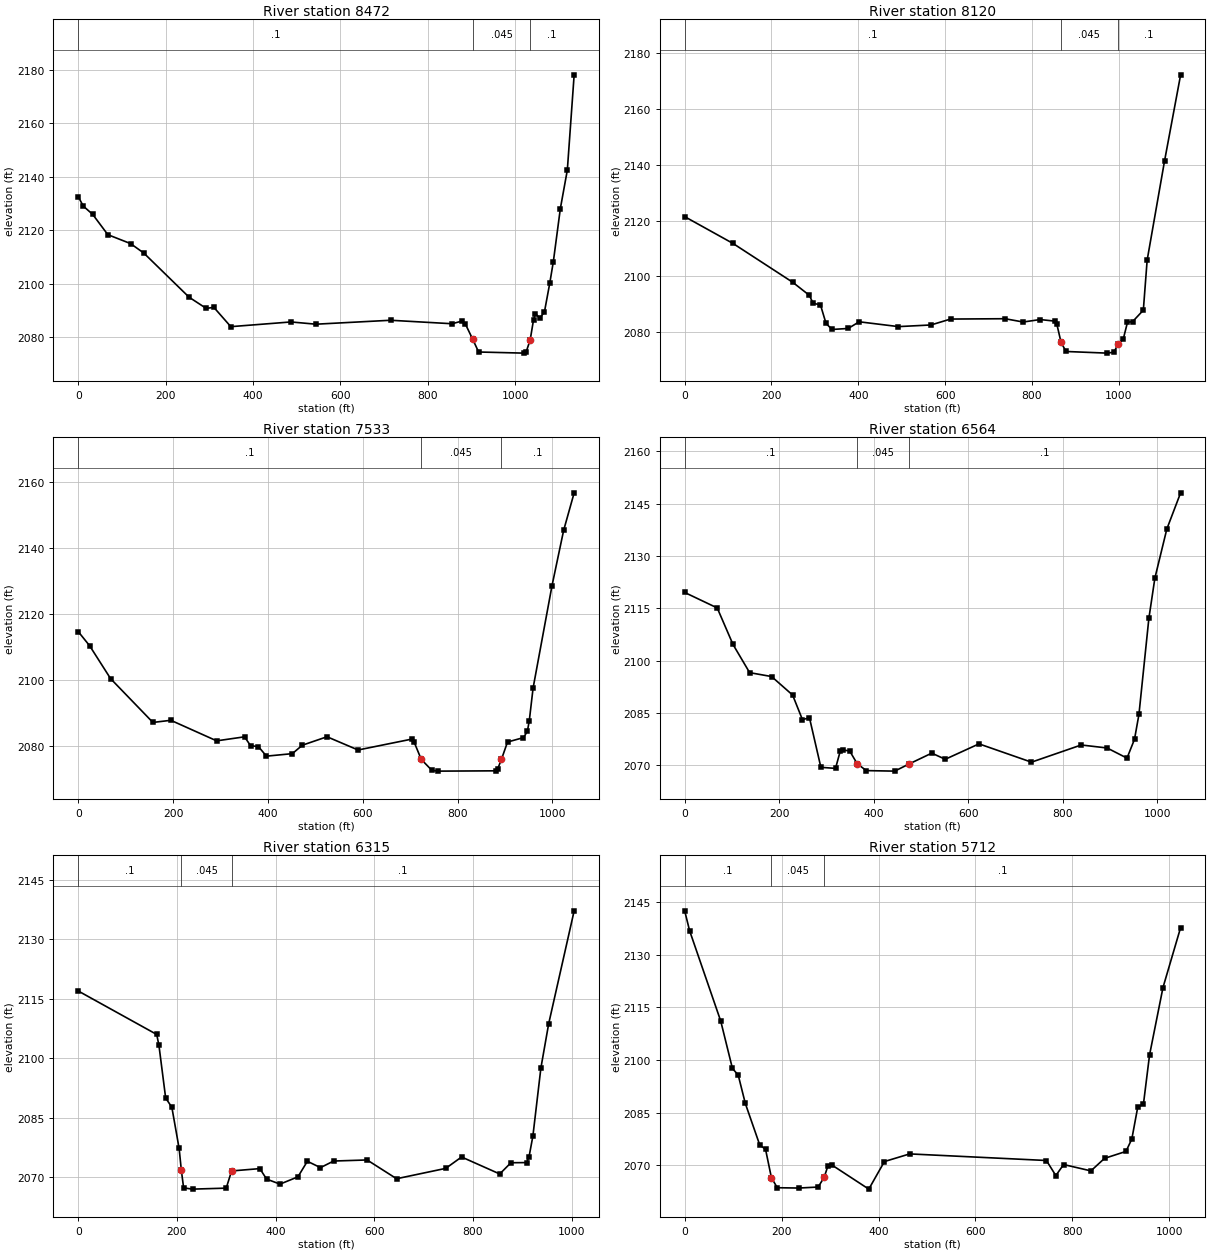
Type RM Length L Ch R = 1 ,8472    ,352.2,352.2,352.2
XS GIS Cut Line= 3
2389369.45123356724722.4869993872388964.26633148725701.609296722
2388960.10019286725776.748890111
#Sta/Elev= 30
       0 2132.64    11.6  2129.1    33.2 2125.99    67.8 2118.42   119.8 2115.09
   150.1 2111.55   253.7 2095.06     293 2090.87   310.3 2091.28   349.2 2084.05
   486.8 2085.81     544 2084.97   714.7 2086.44   855.7 2085.14   877.4 2086.11
     886 2085.03     903 2079.26   916.3 2074.58  1020.2 2074.16  1024.6  2074.4
 1034.24 2079.06  1041.9 2086.57  1046.2 2088.93  1056.3 2087.21  1066.9 2089.56
  1079.2 2100.39  1087.3 2108.37  1103.3 2128.16  1119.3 2142.57  1134.9 2178.15
#Mann= 3 ,-1,0
       0      .1       0     903    .045       0 1034.24      .1       0
Bank Sta=903,1034.24
XS Rating Curve= 0 ,0
Exp/Cntr=0.3,0.1

Type RM Length L Ch R = 1 ,8120    ,587,587,587
XS GIS Cut Line= 4
2388903.68508345724629.9805937732388902.19596016724849.105962927
2388620.43465121725626.814379498 2388614.9250165725722.997370944
#Sta/Elev= 30
       0 2121.39   111.2 2111.79     249 2097.84   287.3 2093.16   295.8 2090.31
   312.8 2089.76   325.6 2083.12   339.4 2080.93   376.6 2081.28   402.1 2083.68
   492.5 2081.95   567.4 2082.54   612.6 2084.66   738.2 2084.78   779.8  2083.6
   819.1 2084.48   853.1 2083.91   857.4 2082.85   867.2 2076.26   878.6 2073.03
   973.4 2072.44   989.3 2072.79   997.8 2075.54  1010.5 2077.51  1020.2 2083.52
  1031.8 2083.71  1056.7 2087.84  1065.5 2105.79  1105.6  2141.4  1142.6 2172.25
#Mann= 3 ,-1,0
       0      .1       0   867.2    .045       0   997.8      .1       0
Bank Sta=867.2,997.8
XS Rating Curve= 0 ,0
Exp/Cntr=0.3,0.1

Type RM Length L Ch R = 1 ,7533    ,968.3,968.3,968.3
XS GIS Cut Line= 4
2388297.81639121724557.4499320462388309.65575092724689.256116473
2388062.11288981725460.8292881042388050.49844964725563.204771243
#Sta/Elev= 30
       0 2114.64      24 2110.35    68.3 2100.34   157.5 2087.04   195.3 2087.69
   291.9 2081.45   350.7 2082.67   363.3    2080   380.1 2079.68   396.9  2076.8
   451.5 2077.56   472.5 2080.12   524.6 2082.69   590.1 2078.67   702.8 2081.96
   707.8 2081.24  723.26 2075.83   745.6  2072.5   758.2 2072.25     880 2072.34
   884.2 2072.83  892.422075.829   905.2 2081.09   938.8 2082.43     947 2084.32
   951.1 2087.56   959.1 2097.47   998.9 2128.51  1023.5 2145.36  1045.7 2156.79
#Mann= 3 ,-1,0
       0      .1       0  723.26    .045       0  892.42      .1       0
Bank Sta=723.26,892.42
XS Rating Curve= 0 ,0
Exp/Cntr=0.3,0.1

Type RM Length L Ch R = 1 ,6564    ,249.3,249.3,249.3
XS GIS Cut Line= 3
2387629.78093002724514.2495177512387223.20121926725053.270437476
2387105.52452199725408.926491732
#Sta/Elev= 30
       0 2119.54    68.9  2115.1   102.3 2104.62   137.5 2096.54     184 2095.42
   228.5 2090.11   249.2 2083.08   264.2 2083.57   288.3 2069.38   319.3 2069.08
   329.3 2074.03   334.4 2074.39   349.4 2074.05   365.1 2070.42   384.5 2068.44
   444.6 2068.29   474.5 2070.31     523 2073.45   551.6 2071.69     623 2076.11
   734.1 2070.86   839.4 2075.79   894.2 2074.93   936.3 2072.02   952.2 2077.43
   961.6 2084.58   982.6 2112.11   995.3 2123.65  1020.6 2137.73  1049.8 2148.12
#Mann= 3 ,-1,0
       0      .1       0   365.1    .045       0   474.5      .1       0
Bank Sta=365.1,474.5
XS Rating Curve= 0 ,0
Exp/Cntr(USF)=0,0
Exp/Cntr=0.3,0.1

Type RM Length L Ch R = 1 ,6315    ,603.4,603.4,603.4
XS GIS Cut Line= 4
2387262.95972138724454.7718213962387228.67690244724603.617890704
2386867.67651988725274.424184877 2386870.6062472725364.801424726
#Sta/Elev= 30
       0 2116.97   159.1 2106.01   163.6 2103.23   177.2 2089.98   189.7 2087.68
   204.5 2077.27     209 2071.73   213.6 2067.34   231.7 2067.03   299.9 2067.28
   310.8 2071.61     368  2072.2   381.7 2069.56   408.9 2068.29   445.2 2070.13
   464.3 2074.05   490.9 2072.45   517.5 2074.11   585.4 2074.38   645.1 2069.65
   744.7 2072.26   776.8 2075.13   854.1 2070.85   876.8 2073.68   908.6 2073.72
   913.5 2075.19   921.3 2080.41   937.5 2097.56   953.3 2108.73  1004.9 2137.17
#Mann= 3 ,0,0
       0      .1       0     209    .045       0   310.8      .1       0
Bank Sta=209,310.8
XS Rating Curve= 0 ,0
Exp/Cntr=0.3,0.1

Type RM Length L Ch R = 1 ,5712    ,454.4,454.4,454.4
XS GIS Cut Line= 2
2386601.34082376724363.1307907392386702.96317436725381.405016181
#Sta/Elev= 30
       0 2142.55    10.1 2136.91    74.4 2111.12    98.5 2097.64   110.5 2095.71
   125.1 2087.65   154.8 2075.84   166.9 2074.54   178.9 2066.52     191 2063.62
   235.2 2063.53   275.4 2063.81  287.88 2066.61   295.5 2069.81   303.5 2070.12
   379.9 2063.22   412.1 2071.08   464.3 2073.26   746.4 2071.38   765.8 2067.08
   781.9 2070.23   838.2 2068.42   866.3 2071.99   910.5 2073.97   922.6 2077.49
   934.7  2086.5   946.7 2087.58   959.2 2101.47   986.9 2120.68  1023.3 2137.78
#Mann= 3 ,0,0
       0      .1       0   178.9    .045       0  287.88      .1       0
Bank Sta=178.9,287.88
XS Rating Curve= 0 ,0
Exp/Cntr=0.3,0.1

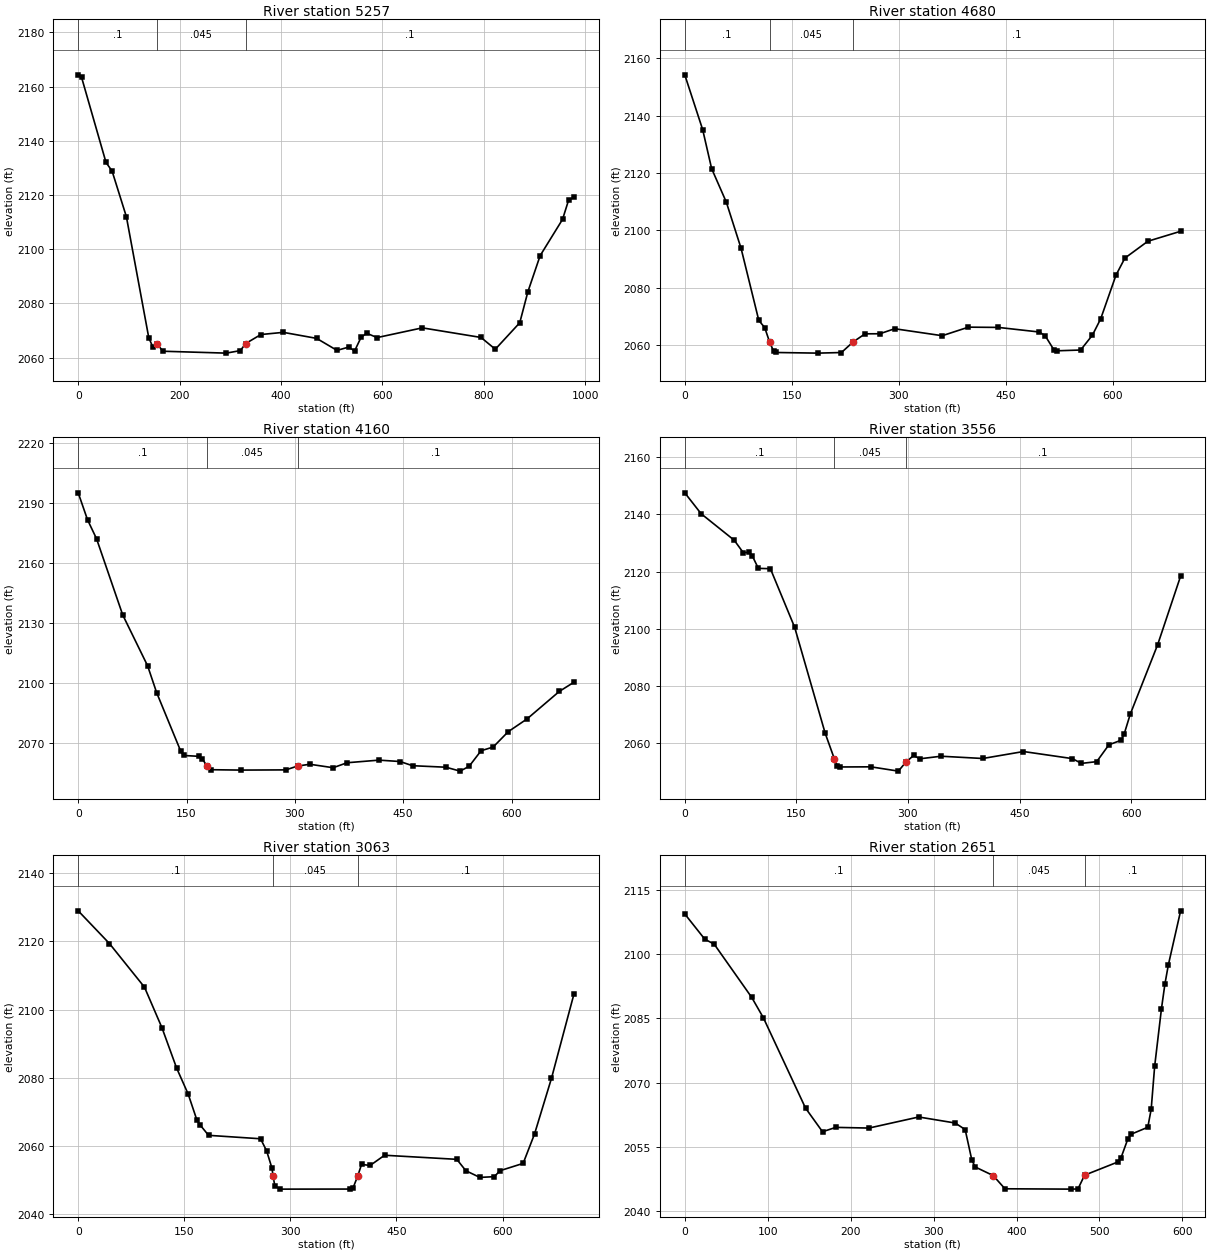
Type RM Length L Ch R = 1 ,5257    ,576.8,576.8,576.8
XS GIS Cut Line= 2
2386152.12976108724390.6819557252386249.17978553725363.787010012
#Sta/Elev= 30
       0 2164.33     6.5 2163.49    54.8 2132.02    66.8 2128.84      95 2112.01
   139.2 2067.34   147.2 2063.94   155.3 2065.23   166.8 2062.39   291.9 2061.69
   319.8 2062.62  330.29 2065.23   360.3 2068.55   404.5 2069.35   470.2 2067.13
   510.4  2062.7   533.1  2063.9   545.2 2062.53   557.9 2067.53   568.9 2069.03
   589.4 2067.42   678.6 2071.01   794.4 2067.47   822.6 2063.13   870.8 2072.89
   886.8  2084.3     911 2097.64   955.2 2111.02   967.3 2118.23   977.9 2119.09
#Mann= 3 ,-1,0
       0      .1       0   155.3    .045       0  330.29      .1       0
Bank Sta=155.3,330.29
XS Rating Curve= 0 ,0
Exp/Cntr=0.3,0.1

Type RM Length L Ch R = 1 ,4680    ,520.4,520.4,520.4
XS GIS Cut Line= 2
2385567.94657447 724572.863191812385744.67249574 725244.74302895
#Sta/Elev= 30
       0 2154.17    25.1 2135.07    37.6 2121.55    58.2 2109.86    78.9 2093.76
   103.7  2068.7     112  2066.2  118.79 2061.21   124.4 2058.01   128.5 2057.53
   186.4 2057.31   219.5 2057.52   235.8 2061.19   252.6 2064.03   273.3 2064.05
     294  2065.8   360.7 2063.37   397.4 2066.35   439.3 2066.26   496.7 2064.66
   504.9 2063.37   517.3  2058.4   521.1 2058.12   554.6 2058.39   571.1 2063.56
   582.7 2069.24   604.2 2084.48   616.6 2090.38   648.8 2096.25   694.7 2099.72
#Mann= 3 ,0,0
       0      .1       0  118.79    .045       0   235.8      .1       0
Bank Sta=118.79,235.8
XS Rating Curve= 0 ,0
Exp/Cntr=0.3,0.1

Type RM Length L Ch R = 1 ,4160    ,604.3,604.3,604.3
XS GIS Cut Line= 2
2385052.41703854724676.7550311232385240.84660382725336.931224251
#Sta/Elev= 30
       0 2194.93    12.9 2181.47    25.4 2171.99    61.6 2133.98    96.1 2108.54
   108.6 2095.15   141.9 2065.96     146 2063.77   166.8 2063.36   171.7 2062.17
   178.1 2058.59   183.5 2056.67   225.1 2056.48   287.5 2056.58   303.7  2058.5
   320.7 2059.39   352.9 2057.66   372.3 2060.15   416.4 2061.45   445.5 2060.76
   462.9 2058.67   509.2 2057.91   528.7 2055.96   541.2 2058.36   557.8 2066.15
   574.5 2067.99   595.3 2075.64   621.5 2082.05     666 2095.74   686.5 2100.39
#Mann= 3 ,0,0
       0      .1       0   178.1    .045       0   303.7      .1       0
Bank Sta=178.1,303.7
XS Rating Curve= 0 ,0
Exp/Cntr=0.3,0.1

Type RM Length L Ch R = 1 ,3556    ,492.6,492.6,492.6
XS GIS Cut Line= 3
2384527.69581764724823.4309428052384508.94237753724946.489934942
2384628.03185577725475.274252801
#Sta/Elev= 30
       0 2147.47      22 2140.17    66.5 2130.92    78.6  2126.6    86.7 2126.69
    90.8 2125.44    98.9 2121.11   115.1 2120.99   147.7 2100.54   188.7 2063.59
     201 2054.68   205.1 2052.22   209.2  2051.8   250.2 2051.85   287.1 2050.35
   296.8 2053.37   307.6 2055.82   315.8 2054.65   344.5 2055.55   400.5 2054.76
   455.3 2057.19   520.9 2054.72   533.2 2053.05   553.7 2053.66   570.1 2059.54
   586.5 2061.13   590.6 2063.29   598.8 2070.22   635.7 2094.52   666.5 2118.42
#Mann= 3 ,-1,0
       0      .1       0     201    .045       0   296.8      .1       0
Bank Sta=201,296.8
XS Rating Curve= 0 ,0
Exp/Cntr=0.3,0.1

Type RM Length L Ch R = 1 ,3063    ,411.7,411.7,411.7
XS GIS Cut Line= 4
2384070.12629588724854.3352445062384026.58680653 725028.02789357
2384116.31474395725472.7663659952384117.73840198725541.101271866
#Sta/Elev= 30
       0 2128.99    44.2 2119.37    93.7 2106.57   118.4 2094.66   139.1 2082.83
   155.5 2075.16   167.9 2067.48     172 2066.19   184.3 2063.05   257.8 2062.04
   266.3 2058.55   274.1 2053.32  275.41 2051.06   278.2 2048.11   285.9 2047.25
   384.3 2047.27   388.4 2047.49   395.3 2051.14   400.6  2054.5   412.8 2054.21
   433.2  2057.2   535.3    2056   548.1 2052.66   567.9 2050.69   588.3 2050.91
   596.5 2052.67   629.1 2054.81   645.2 2063.43   669.2 2079.82   701.1 2104.67
#Mann= 3 ,-1,0
       0      .1       0  275.41    .045       0   395.3      .1       0
Bank Sta=275.41,395.3
XS Rating Curve= 0 ,0
Exp/Cntr=0.3,0.1

Type RM Length L Ch R = 1 ,2651    ,383.7,383.7,383.7
XS GIS Cut Line= 4
2383705.38679867 724831.666755162383654.67100795724977.312102855
2383653.37060306725376.5364041252383641.66695905  725419.4497655
#Sta/Elev= 30
       0 2109.42    24.1 2103.52    35.5 2102.35    80.7 2089.91    94.8 2085.13
   145.6 2064.02   166.1 2058.49   182.1 2059.51   222.1 2059.35   282.1 2061.94
   326.1 2060.53   338.1    2059   346.1  2051.9   350.1 2050.26   371.9 2048.24
   386.1 2045.15   466.1 2045.07   474.1 2045.11   482.1 2048.33   522.1 2051.41
   526.1 2052.44   534.1 2056.72   538.1  2057.9   558.3 2059.54   562.4 2063.75
   566.6 2073.82   574.8 2087.28     579 2093.09   583.1 2097.51   597.9 2110.15
#Mann= 3 ,-1,0
       0      .1       0   371.9    .045       0   482.1      .1       0
Bank Sta=371.9,482.1
XS Rating Curve= 0 ,0
Exp/Cntr(USF)=0,0
Exp/Cntr=0.3,0.1

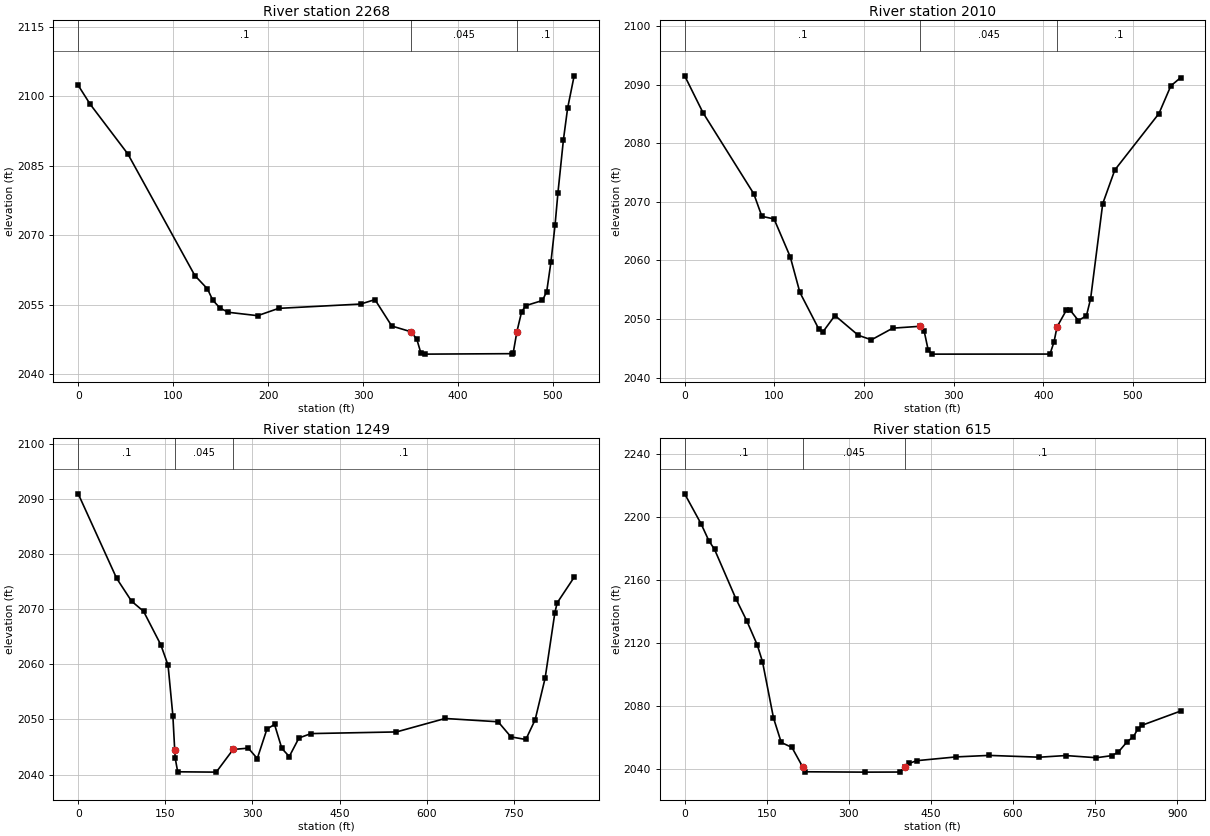
Type RM Length L Ch R = 1 ,2268    ,257.9,257.9,257.9
XS GIS Cut Line= 2
2383463.88142395724769.7797608792383243.73065769725243.453317859
#Sta/Elev= 30
       0 2102.36    12.6 2098.28    52.3 2087.53   122.8 2061.27   136.1 2058.38
   141.7 2055.95   149.3 2054.24   158.1 2053.32     189 2052.59   211.1 2054.17
   297.4  2055.1   312.5 2056.06   330.2 2050.36   350.5 2049.11   356.6  2047.5
     361 2044.42   365.4 2044.28     457 2044.38   458.1 2044.53  462.03 2049.15
   466.9 2053.38   471.3 2054.76   488.9 2055.87   493.4  2057.8   497.8 2064.09
   502.2  2072.2   505.2 2079.09     511 2090.61   515.4 2097.41   522.3 2104.42
#Mann= 3 ,-1,0
       0      .1       0   350.5    .045       0  462.03      .1       0
Bank Sta=350.5,462.03
XS Rating Curve= 0 ,0
Exp/Cntr(USF)=0,0
Exp/Cntr=0.3,0.1

Type RM Length L Ch R = 1 ,2010    ,760.3,760.3,760.3
XS GIS Cut Line= 3
2383213.76798697724737.0739186342382991.41767099725156.898772007
2383026.13567098725226.942998766
#Sta/Elev= 30
       0 2091.48    20.5 2085.17    77.1 2071.35    86.1 2067.51    99.7 2067.06
   117.8 2060.58   128.5 2054.53   149.5 2048.31     154 2047.75   167.6 2050.59
   193.6 2047.22   208.3 2046.44   232.1 2048.43   262.6 2048.75   267.2 2047.89
   271.7 2044.64   276.2    2044   407.5 2044.01     412  2046.1  415.32 2048.64
   425.6 2051.46   430.1 2051.48   439.2 2049.72   448.2 2050.57   452.8 2053.45
   466.3 2069.66   479.8 2075.42     529 2085.04   542.3 2089.77   553.2 2091.17
#Mann= 3 ,-1,0
       0      .1       0   262.6    .045       0  415.32      .1       0
Bank Sta=262.6,415.32
XS Rating Curve= 0 ,0
Exp/Cntr(USF)=0,0
Exp/Cntr=0.3,0.1

Type RM Length L Ch R = 1 ,1249    ,634.2,634.2,634.2
XS GIS Cut Line= 4
2382262.70028503724745.6709075612382348.97585569724852.468462063
2382399.78028898 725033.229513132382903.77248936725194.073253209
#Sta/Elev= 30
       0 2090.91    66.2 2075.58    91.9 2071.44   112.5 2069.61   142.2 2063.54
   154.7 2059.84     163  2050.7  166.18 2044.44   167.1 2042.95   171.3  2040.5
   237.7 2040.44   266.8 2044.55   292.9 2044.79   308.4 2042.91     325 2048.24
   338.1 2049.09   350.7 2044.73   363.5 2043.27   380.1 2046.63     401 2047.43
   548.1 2047.73     632 2050.17   723.2 2049.57   745.3 2046.83   770.9 2046.36
   786.9 2049.93   804.1 2057.48   820.9 2069.36   824.8 2071.13   854.1 2075.78
#Mann= 3 ,-1,0
       0      .1       0  166.18    .045       0   266.8      .1       0
Bank Sta=166.18,266.8
XS Rating Curve= 0 ,0
Exp/Cntr=0.3,0.1

Type RM Length L Ch R = 1 ,615     ,294.2,294.2,294.2
XS GIS Cut Line= 3
2382190.91084951725601.8922397652382446.39181784725235.775332184
2382905.94874853 725217.29612261
#Sta/Elev= 30
       0 2214.61    30.1 2195.48    44.1 2184.88    54.5 2179.38    93.5 2148.08
   113.5 2133.93   132.6 2118.71   142.2 2108.02   162.3 2072.32   176.5 2056.71
     196 2053.58  215.882041.044   220.4  2038.1   328.9 2037.88   393.6 2037.94
  401.922041.043   410.6 2043.45   423.7 2045.14   496.3 2047.55   556.3  2048.5
   648.4 2047.36   696.4 2048.41   752.5 2047.02   780.5 2048.35   792.5  2050.6
   808.5 2057.13   820.1 2060.36   828.5 2065.47   836.5 2067.73906.3722 2076.66
#Mann= 3 ,-1,0
       0      .1       0  215.88    .045       0  401.92      .1       0
Bank Sta=215.88,401.92
XS Rating Curve= 0 ,0
Exp/Cntr(USF)=0,0
Exp/Cntr=0.3,0.1