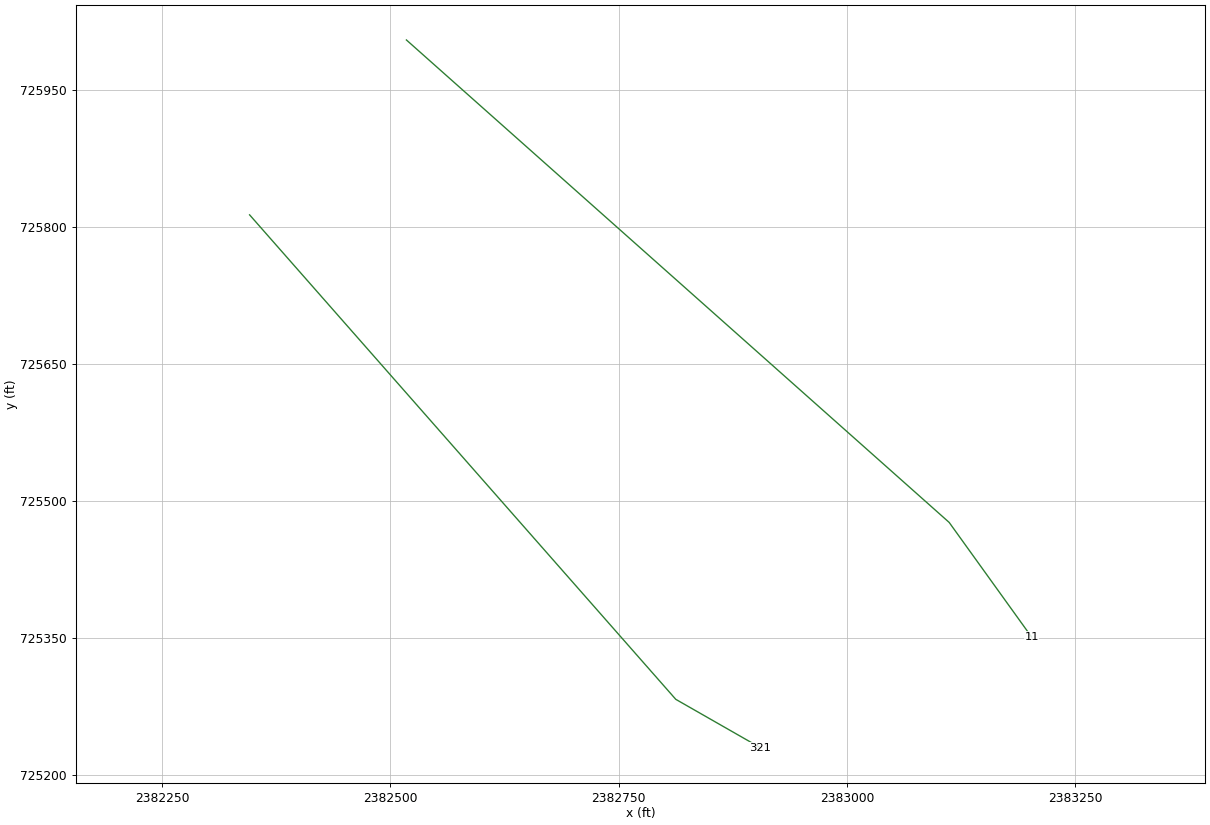
HEC-RAS study DRKFK_2.prj: DRKFK_2

--- DRKFK_2.g01 (geometry) --- (continued)

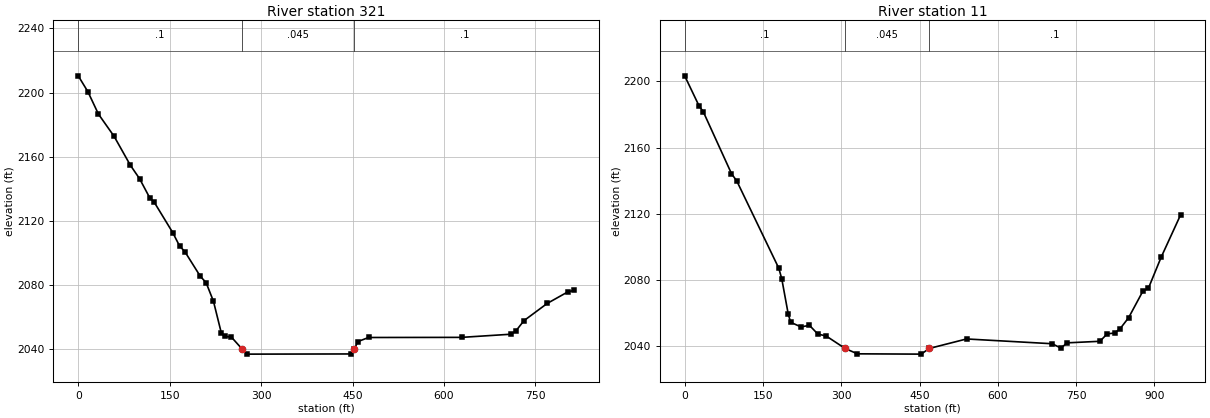
Type RM Length L Ch R = 1 ,321     ,309.8,309.8,309.8
XS GIS Cut Line= 3
2382345.67614289725813.4126782242382812.55252811725282.671127102
2382905.04690632725229.817196699
#Sta/Elev= 30
       0 2210.43    15.9 2200.52    33.1 2186.61    58.9 2172.68    85.5  2154.7
   100.7 2146.25   117.5 2134.23   124.9 2131.47     155  2112.7   166.3  2104.3
   174.8 2100.87   200.3 2085.41   209.7 2081.51   221.8 2069.88   234.7 2050.11
     240 2047.97   251.3  2047.5  268.752040.105   277.3  2036.9   446.9 2037.01
  453.03 2040.11   458.5  2044.7   476.2 2047.27   628.9 2047.35   709.9 2049.32
   717.9  2051.4   731.1 2057.77   769.2 2068.51   803.2 2075.75813.3969 2076.65
#Mann= 3 ,-1,0
       0      .1       0  268.75    .045       0  453.03      .1       0
Bank Sta=268.75,453.03
XS Rating Curve= 0 ,0
Exp/Cntr(USF)=0,0
Exp/Cntr=0.3,0.1

Type RM Length L Ch R = 1 ,11      ,,,
XS GIS Cut Line= 3
 2382517.4514167726005.0081759322383112.05813373 725476.46887191
2383202.35026483725350.940787204
#Sta/Elev= 30
       0 2203.39    27.3  2185.4    35.8 2181.59    89.6 2144.41     100 2139.79
   180.3 2087.25     186 2080.87   198.4 2059.59     203  2054.6   222.8 2051.82
   239.1 2052.74   255.2 2047.47     271 2046.34  307.412038.792   330.9 2035.56
   453.2 2035.38  468.452038.793   540.1 2044.54   704.2 2041.65   720.8 2039.03
   732.8 2042.19   795.6 2043.13   809.5 2047.63   823.8  2048.1   834.1 2050.66
   850.6  2057.4   878.4  2073.7   888.3 2075.02   912.9 2093.89950.1855 2119.49
#Mann= 3 ,-1,0
       0      .1       0  307.41    .045       0  468.45      .1       0
Bank Sta=307.41,468.45
XS Rating Curve= 0 ,0
Exp/Cntr(USF)=0,0
Exp/Cntr=0.3,0.1
LCMann Table=0

Chan Stop Cuts=-1
Use User Specified Reach Order=0
Composite Channel Slope=5